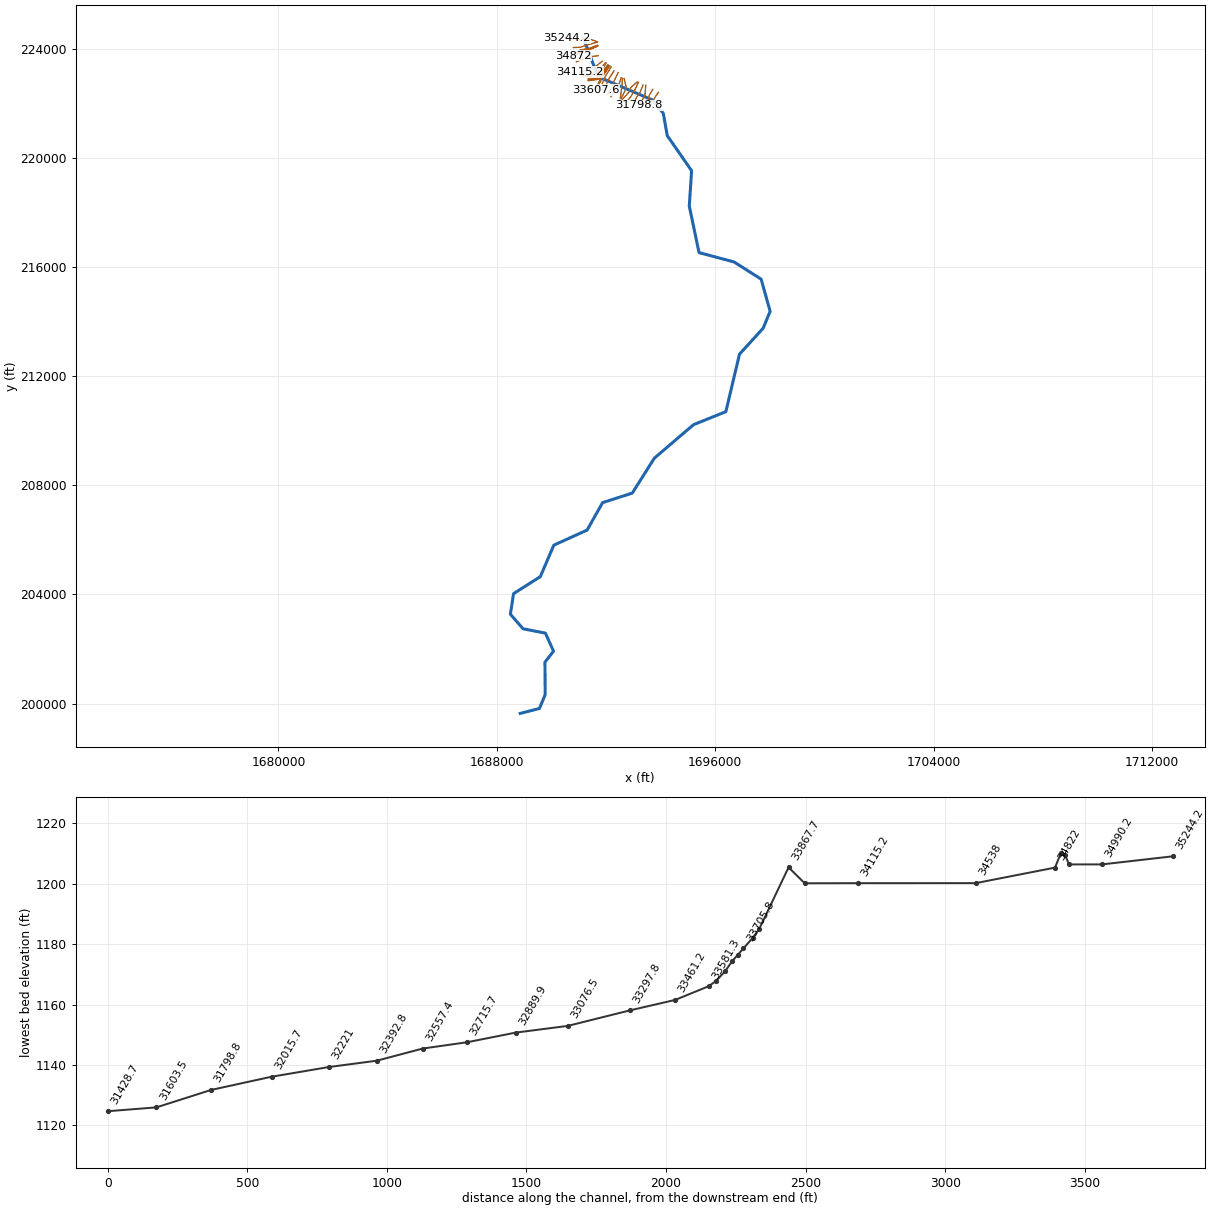
--- bncrk.prj (project) ---

Proj Title=bncrk
Current Plan=p01
Default Exp/Contr=0,0
English Units
Geom File=g01
Flow File=f01
Plan File=p01
BEGIN DESCRIPTION:
END DESCRIPTION:
DSS Export Rating Curves= 0
DSS Export Rating Curve Sorted= 0
DSS Export Volume Flow Curves= 0
DXF OffsetX= 0
DXF OffsetY= 0
DXF ScaleX= 0
DXF ScaleY= 0

--- bncrk.p01 (plan) ---

Plan Title=Approximate Study - 100 yr
Program Version=4.00
Short Identifier=100 yr
Geom File=g01
Flow File=f01
Subcritical Flow
K Sum by GR= 0
Std Step Tol= 0.01
Critical Tol= 0.01
Num of Std Step Trials= 20
Max Error Tol= 0.3
Flow Tol Ratio= 0.001
Split Flow NTrial= 30
Split Flow Tol= 0.02
Split Flow Ratio= 0.02
Log Output Level= 0
Friction Slope Method= 1
Unsteady Friction Slope Method= 2
Unsteady Bridges Friction Slope Method= 1
Parabolic Critical Depth
Global Vel Dist= 0 , 0 , 0
Global Log Level= 0
CheckData=True
Encroach Param=-1 ,0,0, 0
Run HTab= 0
Run UNet= 0
Run PostProcess= 0
Run WQNet= 0
UNET Theta= 0
UNET Theta Warmup= 0
UNET ZTol= 0
UNET ZSATol= 0
UNET MxIter= 0
UNET MaxInSteps= 0
UNET DtIC= 0
UNET DtMin= 0
UNET MaxCRTS= 0
UNET WFStab= 0
UNET SFStab= 0
UNET WFX= 1
UNET SFX= 1
UNET DSS MLevel= 1
UNET DZMax Abort= 0
UNET Convert EG Bridges= 0
UNET Use Existing IB Tables= 0
UNET Froude Reduction=False
UNET Froude Limit= 0
UNET Froude Power= 0
UNET Time Slicing=0,0, 5
Write IC File= 0
Echo Input=False
Echo Output=False
Write Detailed= 0
Detailed Automatic Start=False, 0
WQ ULTIMATE=-1
WQ Max Comp Step=1HOUR
WQ Output Interval=15MIN
WQ Output Selected Increments= 0
WQ Output face flow=0
WQ Output face velocity=0
WQ Output face area=0
WQ Output face dispersion=0
WQ Output cell volume=0
WQ Output cell surface area=0
WQ Output cell continuity=0
WQ Output face conc=0
WQ Output face dconc_dx=0
WQ Output face courant=0
WQ Output face peclet=0
WQ Output face adv mass=0
WQ Output face disp mass=0
WQ Output cell mass=0
WQ Output cell source sink temp=0
WQ Output cell source sink nsm=0
WQ Output MaxMinRange=-1
WQ Daily Max Min Mean=-1
WQ Daily Range=0
WQ Daily Time=0
WQ Create Restart=0
WQ Fixed Restart=0
WQ System Summary=False
Sorting and Armoring Iterations= 10
XS Update Threshold= 0.02
Hydraulics Update Threshold= 0.02
Energy Slope Method= 1
Volume Change Method= 0
XS Weighting Method= 0
Number of US Weighted Cross Sections= 1
Number of DS Weighted Cross Sections= 1
Upstream XS Weight=0.25
Main XS Weight=0.5
Downstream XS Weight=0.25
Number of DS XS's Weighted with US Boundary= 1
Upstream Boundary Weight= 1
Weight of XSs Associated with US Boundary= 0
Number of US XS's Weighted with DS Boundary= 1
Downstream Boundary Weight= 0.5
Weight of XSs Associated with DS Boundary= 0.5
Sediment Output Level= 4
Mass or Volume Output= 0
Output Increment Type= 1
Profile and TS Output Increment= 10
XS Output Flag= 0
XS Output Increment= 10
Disregard all LS=0
Disregard all Conn=0
Disregard all Breaches=0
Disregard all Pumps=0

--- bncrk.f01 (steady flow) ---

Flow Title=USGS Regression Equation
Program Version=4.00
Number of Profiles= 1
Profile Names=P100yr
River Rch & RM=bncrk,Main            ,35244.2
     376
River Rch & RM=bncrk,Main            ,33607.6
     417
River Rch & RM=bncrk,Main            ,33297.8
     486
River Rch & RM=bncrk,Main            ,32392.8
     493
River Rch & RM=bncrk,Main            ,32015.7
     557
River Rch & RM=bncrk,Main            ,30832.7
     568
River Rch & RM=bncrk,Main            ,30577
     874
River Rch & RM=bncrk,Main            ,28768.4
     915
River Rch & RM=bncrk,Main            ,26990.3
    1017
River Rch & RM=bncrk,Main            ,25405.9
    1126
River Rch & RM=bncrk,Main            ,24318.4
    1164
River Rch & RM=bncrk,Main            ,22424.6
    1289
River Rch & RM=bncrk,Main            ,21177.9
    1380
River Rch & RM=bncrk,Main            ,18819
    1491
River Rch & RM=bncrk,Main            ,16460
    1612
River Rch & RM=bncrk,Main            ,10790.5
    1766
River Rch & RM=bncrk,Main            ,10460.3
    2380
River Rch & RM=bncrk,Main            ,5848
    2440
River Rch & RM=bncrk,Main            ,5417.1
    3591
River Rch & RM=bncrk,Main            ,234.5
    3765
Boundary for River Rch & Prof#=bncrk,Main            , 1
Up Type= 0
Dn Type= 3
Dn Slope=0.0066
DSS Import GetInterval= 0
DSS Import GetPeak= 0
DSS Import FillOption= 0

--- bncrk.g01 (geometry) ---

Geom Title=USGS 3m DEM
Program Version=4.00

River Reach=bncrk           ,Main
Reach XY= 30
     1691181.345      224385.746     1691705.333      222989.286
     1693710.599      222130.854     1694097.142      221646.966
     1694244.023      220825.937     1695134.462      219541.751
     1695049.931      218242.722     1695407.036      216537.401
     1696692.836      216193.701     1697681.507      215563.812
     1698010.763      214383.025     1697755.213      213764.103
     1696888.814      212812.189     1696389.006       210703.02
     1695208.332       210227.93       1693770.9      208999.842
     1692962.286       207717.39     1691877.278      207368.625
     1691305.512      206359.742     1690088.008      205807.687
     1689594.251      204653.563     1688613.714      204030.052
     1688497.866      203275.704     1688960.482       202742.42
      1689780.94      202580.734     1690077.559      201919.898
     1689763.347      201517.329     1689772.523      200326.306
     1689561.457      199818.526     1688859.269      199639.026

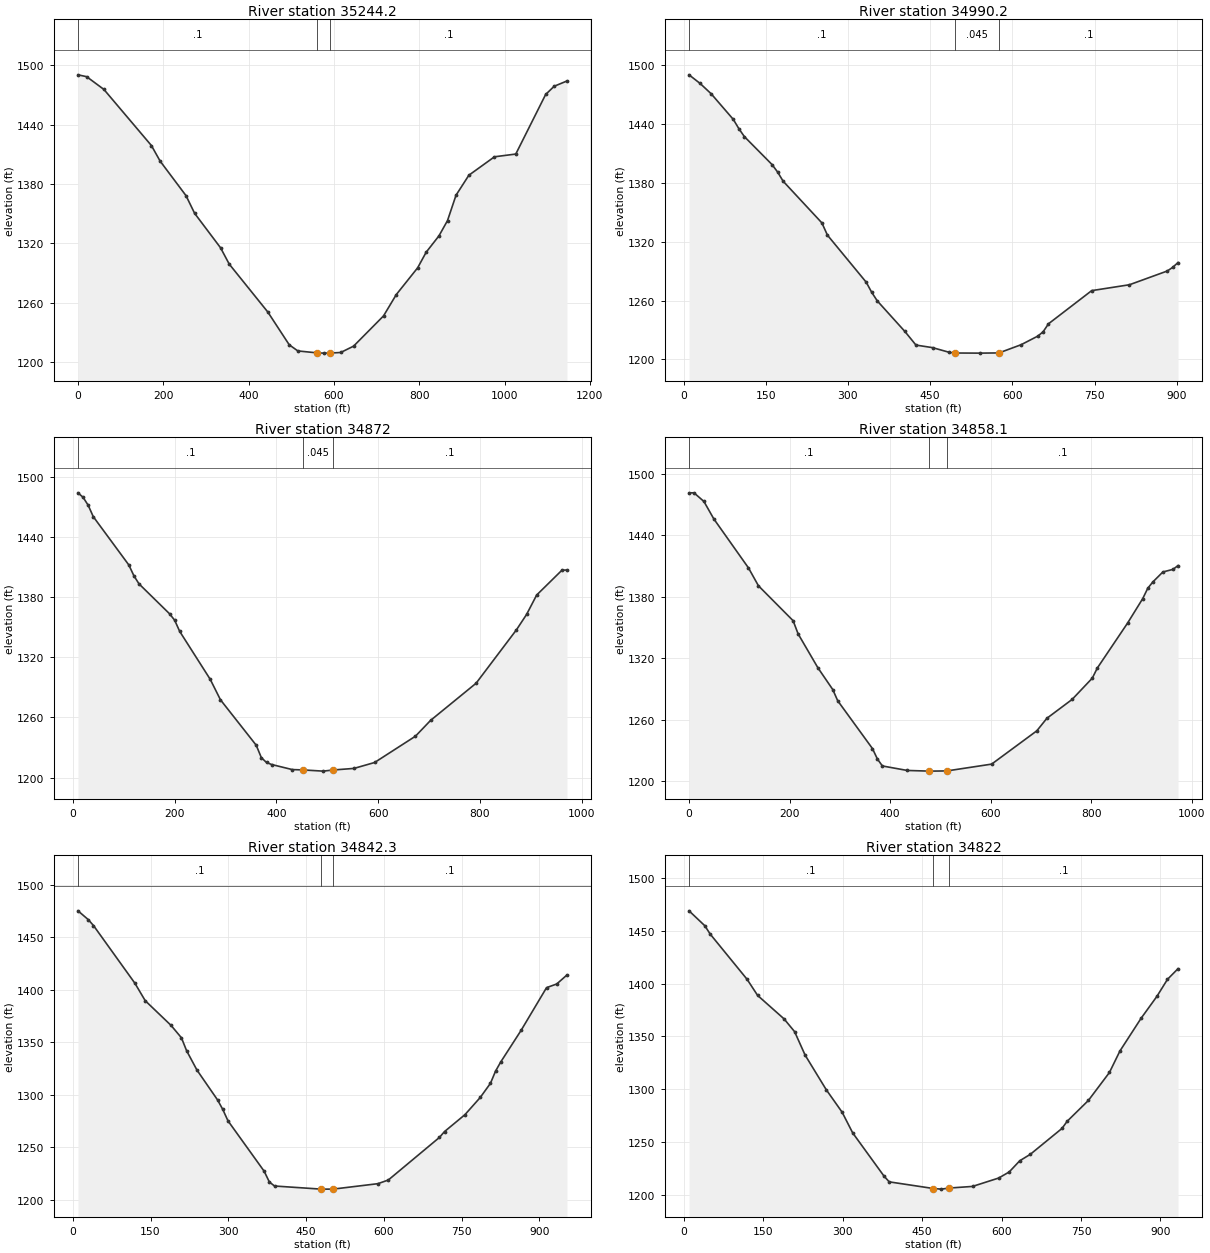
Type RM Length L Ch R = 1 ,35244.2 ,251.6,253.9,256.3
XS GIS Cut Line= 4
      1691687.74       224265.56     1691346.122      224393.133
     1691020.562      224329.866     1690575.298      224395.608
#Sta/Elev= 30
       0 1490.35    20.3 1488.48    60.8 1475.57   172.2 1418.84   192.5 1403.19
   253.2 1368.26   273.5 1350.33   334.3  1315.5   354.5  1299.1   445.1 1250.58
   495.3 1217.45   515.4  1211.3   560.7 1209.31   575.7 1209.07   590.7 1209.13
   615.9 1209.71   646.1 1216.12   716.3 1246.68   746.3 1268.29   796.3 1295.29
   816.3 1311.07   846.3 1327.61   866.3 1343.02   886.3 1368.69   916.4 1388.88
   976.4  1407.5  1026.4 1410.28  1096.4 1470.48  1116.4  1478.8  1146.4 1484.13
#Mann= 3 , 0 , 0
       0      .1       0   560.7    .045       0   590.7      .1       0
Bank Sta=560.7,590.7
XS Rating Curve= 0 ,0
Exp/Cntr=0.3,0.1

Type RM Length L Ch R = 1 ,34990.2 ,121,118.2,115.3
XS GIS Cut Line= 4
     1691676.955      224252.101     1691413.343      224182.244
     1691057.468      224068.891     1690801.764      224057.028
#Sta/Elev= 30
    10.1 1490.43    30.3 1481.63    50.5 1471.08    90.9 1444.91     101 1435.48
   111.1 1427.35   161.6 1398.81   171.7 1391.21   181.8 1381.84   252.5 1339.29
   262.6  1326.8   333.3  1278.8   343.4 1268.43   353.5 1259.72   403.9  1228.5
   424.1 1214.61   454.4 1211.99   484.7 1207.24   494.8 1206.51  540.42 1206.39
   575.5  1206.6   615.9 1214.97   646.2  1223.7     656 1228.11   665.9 1236.34
   744.7 1270.18   813.6 1276.18   882.5 1290.19   892.3 1293.87   902.2 1298.83
#Mann= 3 , 0 , 0
    10.1      .1       0   494.8    .045       0   575.5      .1       0
Bank Sta=494.8,575.5
XS Rating Curve= 0 ,0
Exp/Cntr=0.3,0.1

Type RM Length L Ch R = 1 ,34872   ,13.9,13.9,13.9
XS GIS Cut Line= 4
     1691680.992      224137.388     1691371.825       224022.47
     1691062.658      223970.572     1690807.613      223765.202
#Sta/Elev= 30
      10 1484.08      20  1479.6      30 1471.71      40 1460.32   109.9 1412.08
   119.9 1401.26   129.9 1393.23   189.9 1363.39   199.9 1356.99   209.9 1345.77
   269.9 1297.92   289.9 1277.59   360.2 1232.22   370.3 1219.79   380.4 1215.02
   390.5 1212.98     431 1207.93   451.2  1207.6   491.6 1206.38   511.9 1207.53
   552.3 1209.09   592.8 1214.99   673.1 1241.24   702.9 1257.05   792.2 1294.06
   871.6 1347.44   891.4 1362.69   911.2 1382.06   960.9 1406.87   970.8 1407.08
#Mann= 3 , 0 , 0
      10      .1       0   451.2    .045       0   511.9      .1       0
#XS Ineff= 2 , 0
       0     451             517       0
Permanent Ineff=
       F       F
Bank Sta=451.2,511.9
XS Rating Curve= 0 ,0
Exp/Cntr=0.3,0.1

Type RM Length L Ch R = 1 ,34858.1 ,14.9,15.8,16.8
XS GIS Cut Line= 4
      1691687.74      224130.239     1691375.002      224009.356
     1691082.753      223959.611     1690809.034       223755.91
#Sta/Elev= 30
       0 1481.63     9.9 1481.63    29.6 1473.19    49.3 1456.14   118.3  1408.2
   138.1 1390.74   207.1  1356.6     217 1343.75   256.4 1310.57     286 1289.27
   295.8 1278.35   364.9 1231.62   374.8 1221.37   384.7 1214.59   434.1  1210.2
  478.28 1209.54   513.2 1209.75   602.1  1216.4     692 1248.96     712  1261.2
   762.2 1279.64   802.3 1300.43   812.4 1310.38   872.6 1354.33   902.7 1378.22
   912.7 1388.31   922.8 1394.49   942.8 1404.26   962.9 1406.79   972.9 1410.51
#Mann= 3 , 0 , 0
       0      .1       0  478.28    .045       0   513.2      .1       0
Bank Sta=478.28,513.2
XS Rating Curve= 0 ,0
Exp/Cntr=0.3,0.1

Type RM Length L Ch R = 1 ,34842.3 ,21.1,20.3,19.5
XS GIS Cut Line= 4
     1691691.372      224118.112     1691373.308      224000.228
     1691100.469      223940.174     1690825.407      223749.632
#Sta/Elev= 30
      10 1475.25    29.9 1466.83    39.9 1461.23   119.7  1406.3   139.7 1389.61
   189.6 1366.02   209.5 1354.27   219.5 1341.94   239.4 1323.55   279.3 1294.98
   289.3 1285.96   299.3 1275.13   369.1  1227.1   379.1 1216.85   389.1    1213
  479.05 1210.03  502.01 1210.03   588.6 1215.23   608.6 1218.72   707.2 1259.31
     717 1264.88   756.4 1280.99   785.9 1297.38   805.6 1310.86   815.4 1322.45
   825.2 1331.03   864.6 1361.24   913.8 1402.04   933.5 1405.55   953.2 1414.12
#Mann= 3 , 0 , 0
      10      .1       0  479.05    .045       0  502.01      .1       0
Bank Sta=479.05,502.01
XS Rating Curve= 0 ,0
Exp/Cntr=0.3,0.1

Type RM Length L Ch R = 1 ,34822   ,281.6,284,285.5
XS GIS Cut Line= 4
     1691692.113      224106.991      1691379.98       223975.02
     1691147.919      223933.501     1690840.976      223748.149
#Sta/Elev= 30
      10 1468.81    39.9 1454.65    49.8 1446.89   119.6 1403.98   139.5 1388.71
   189.4 1366.51   209.3 1354.42   229.2 1332.18   269.1 1299.42     299 1278.18
     319 1258.55   378.2  1217.6     388 1212.21   471.2 1205.92   486.2 1205.33
   501.2 1206.35   545.2 1207.89   594.6 1215.82   614.5  1221.6   634.4 1232.18
   654.3 1238.27   714.1 1262.78     724 1269.61   763.9 1289.24   803.7 1315.76
   823.6 1336.18   863.5  1367.1   893.4 1387.86   913.3 1403.95   933.2 1414.03
#Mann= 3 , 0 , 0
      10      .1       0   471.2    .045       0   501.2      .1       0
#XS Ineff= 2 , 0
       0     460             505       0
Permanent Ineff=
       F       F
Bank Sta=471.2,501.2
XS Rating Curve= 0 ,0
Exp/Cntr=0.3,0.1

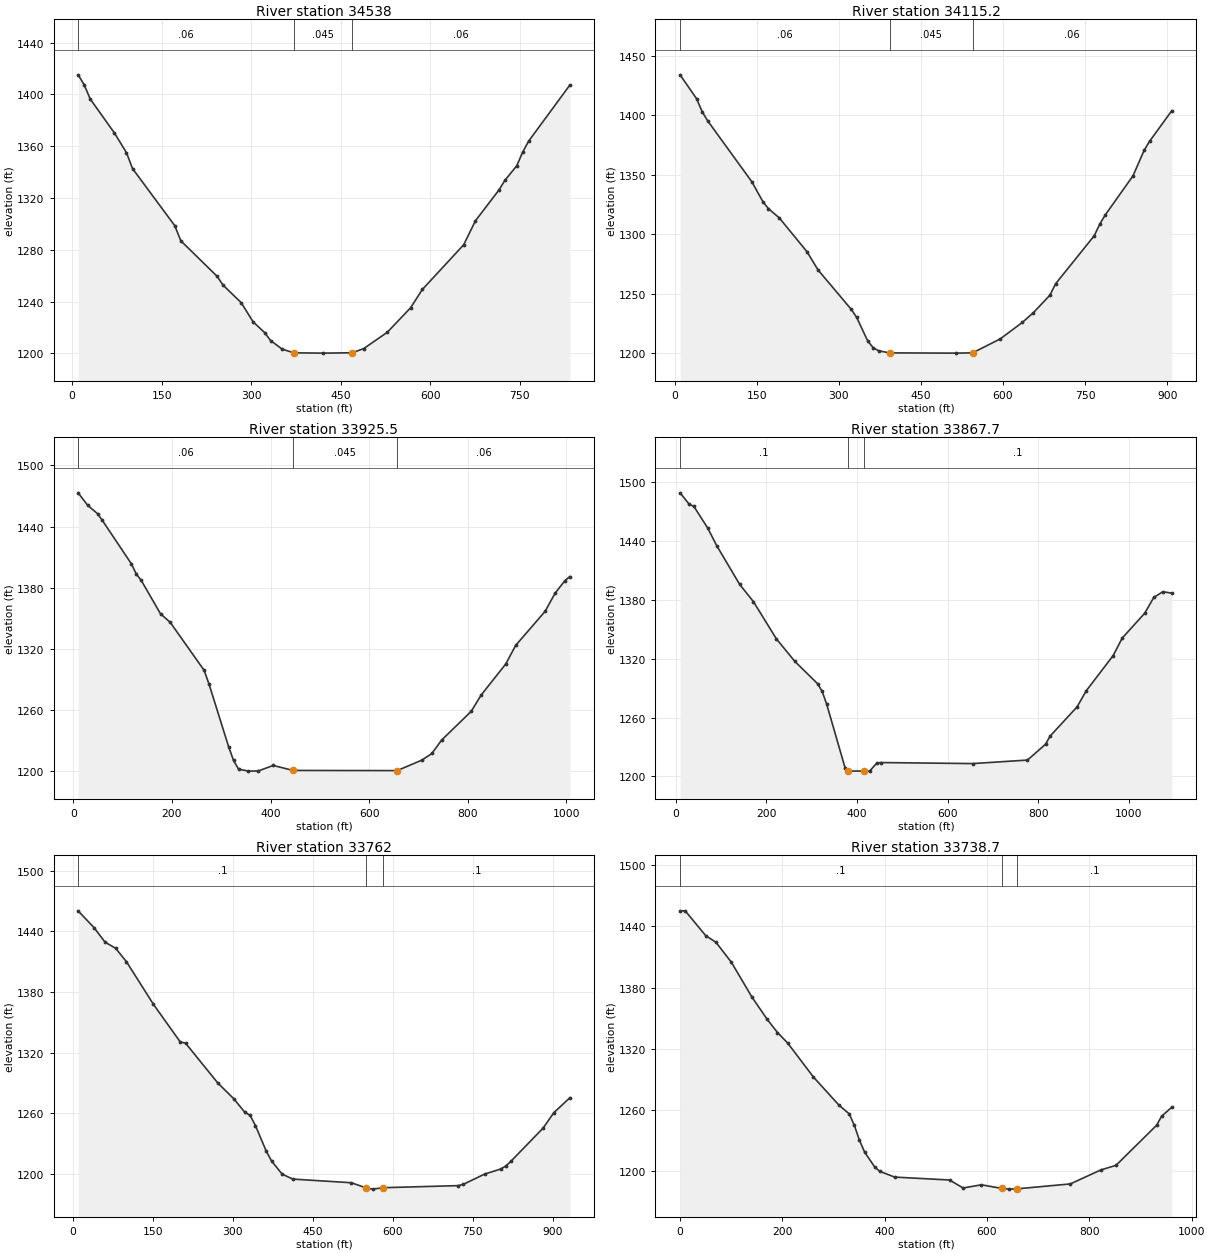
Type RM Length L Ch R = 1 ,34538   ,419.5,422.8,426.1
XS GIS Cut Line= 4
     1691714.843      223756.817     1691423.226      223724.051
     1691172.293      223643.354     1690918.044      223533.916
#Sta/Elev= 30
    10.1 1415.05    20.2 1407.39    30.4 1396.35    70.8 1370.24    91.1 1354.94
   101.2  1342.7     172 1298.59   182.1 1286.92   242.9 1259.51     253 1252.62
   283.3 1239.17   303.2 1224.35   322.7 1215.97   332.5 1209.91     352 1203.24
   371.6 1200.41   420.4 1200.19   469.2 1200.46   488.7 1203.75   527.8 1216.22
   566.9 1235.14   586.7 1249.33   655.9 1283.82   675.7 1302.39   715.2 1326.26
   725.1 1333.66   744.9 1344.87   754.8 1355.41   764.6 1363.74   833.8 1407.17
#Mann= 3 , 0 , 0
    10.1     .06       0   371.6    .045       0   469.2     .06       0
Bank Sta=371.6,469.2
XS Rating Curve= 0 ,0
Exp/Cntr=0.3,0.1

Type RM Length L Ch R = 1 ,34115.2 ,188.4,189.7,191
XS GIS Cut Line= 4
     1691860.275      223553.749      1691653.34      223392.946
     1691330.416      223226.871     1691054.941      223160.968
#Sta/Elev= 30
    10.1 1433.99    40.3 1413.88    50.4 1403.03    60.5 1395.35   141.1 1344.22
   161.3 1327.49   171.4  1321.6   191.5 1313.72   241.9 1285.39   262.1 1270.09
   322.6 1237.06   332.7 1230.21   352.9 1210.36   362.9 1204.72     373  1202.1
   393.2 1200.38   514.2 1200.18   544.5  1200.4   594.9 1212.13   635.3 1225.97
   655.5 1234.17   685.9 1248.97     696 1258.39   766.8 1298.89   776.9  1308.7
   787.1 1316.47   837.6 1349.22   857.9 1370.63     868  1378.3   908.4 1403.88
#Mann= 3 , 0 , 0
    10.1     .06       0   393.2    .045       0   544.5     .06       0
Bank Sta=393.2,544.5
XS Rating Curve= 0 ,0
Exp/Cntr=0.3,0.1

Type RM Length L Ch R = 1 ,33925.5 ,58.5,57.8,57.1
XS GIS Cut Line= 4
     1691974.061      223494.523     1691787.123      223266.577
     1691416.419      223044.155     1691137.094       223027.93
#Sta/Elev= 30
     9.8  1473.1    29.5 1460.69    49.1  1452.7      59    1446   117.9 1403.37
   127.7 1393.54   137.6 1387.35   176.9 1354.42   196.5 1346.11   265.3    1299
   275.1 1285.68   314.9  1224.2     325 1210.59     335 1202.12   355.1 1200.14
   375.2 1200.34   405.4  1205.7   445.6 1200.81   656.7 1200.65     707 1210.96
   727.1 1217.45   747.1 1230.72     807 1258.84     827 1274.77     877 1305.28
     897 1323.45   956.9 1356.98   976.9 1374.64   996.9    1387  1006.9    1391
#Mann= 3 , 0 , 0
     9.8     .06       0   445.6    .045       0   656.7     .06       0
Bank Sta=445.6,656.7
XS Rating Curve= 0 ,0
Exp/Cntr=0.3,0.1

Type RM Length L Ch R = 1 ,33867.7 ,105.1,105.7,106.3
XS GIS Cut Line= 4
     1692001.383       223493.04     1691873.785      223240.216
     1691433.883      222996.046     1691126.192      223015.024
#Sta/Elev= 30
    10.1 1489.05    30.3 1477.36    40.5 1475.27    70.8  1453.3      91 1435.14
   141.6 1395.65   171.9 1378.13   222.5  1340.2     263 1317.36   313.4 1294.49
   323.4 1286.71   333.5 1273.54   373.8 1209.08  381.32  1205.5   416.6  1205.5
     428 1205.41   444.2 1213.72   454.3 1214.14   655.5  1213.1   776.3 1216.68
   816.2 1232.86   826.1 1241.08   885.8 1270.96   905.7 1287.17   965.3 1323.24
   985.2 1341.01  1034.9 1366.38  1054.8  1382.4  1074.7 1388.26  1094.6 1386.79
#Mann= 3 , 0 , 0
    10.1      .1       0  381.32    .045       0   416.6      .1       0
Bank Sta=381.32,416.6
XS Rating Curve= 0 ,0
Exp/Cntr=0.3,0.1

Type RM Length L Ch R = 1 ,33762   ,14.1,23.3,33.1
XS GIS Cut Line= 4
     1692063.586      223418.154     1691849.007      223113.225
      1691497.15      222904.111     1691347.141      222907.615
#Sta/Elev= 30
    10.1 1460.31    40.3 1443.44    60.5 1429.36    80.6 1423.19   100.8  1409.9
   151.2 1367.89   201.5 1330.64   211.6 1329.35   272.1 1289.92   302.3 1274.17
   322.5 1261.03   332.6 1257.94   342.6 1247.83   362.8 1222.58   372.9 1212.73
   392.8 1199.69   412.8 1194.85   522.6 1191.23  550.67 1186.01   562.5 1184.92
   582.5 1186.33   722.3 1188.38   732.3 1189.64   772.2 1199.77   802.2 1204.78
   812.2 1207.83   822.2 1212.74   882.2 1245.41   902.2 1260.59   932.2 1275.33
#Mann= 3 , 0 , 0
    10.1      .1       0  550.67    .045       0   582.5      .1       0
Bank Sta=550.67,582.5
XS Rating Curve= 0 ,0
Exp/Cntr=0.3,0.1

Type RM Length L Ch R = 1 ,33738.7 ,33.5,32.9,31.8
XS GIS Cut Line= 6
     1692064.892      223409.471     1691849.437       223107.74
     1691717.459      223024.728     1691688.078      222980.425
     1691679.217      222917.001     1691363.962      222881.091
#Sta/Elev= 30
       0 1455.36      10 1455.36    50.1    1431    70.1 1424.46   100.2 1404.91
   140.3 1370.78   170.3 1348.76   190.4 1335.84   210.4 1325.47   260.5 1292.22
   310.6 1264.48   330.7  1255.9   340.7 1244.57   350.7 1229.91   360.7  1218.4
   380.5 1203.73   390.2 1199.49   419.5 1193.85   526.7 1190.97   553.3 1183.14
     589 1186.28   628.9  1182.7   643.9 1182.02   658.9  1182.3   762.9 1187.15
   822.4 1200.85   852.1 1205.39   931.4 1244.71   941.3 1253.66   961.2 1262.46
#Mann= 3 , 0 , 0
       0      .1       0   628.9    .045       0   658.9      .1       0
Bank Sta=628.9,658.9
XS Rating Curve= 0 ,0
Exp/Cntr=0.3,0.1

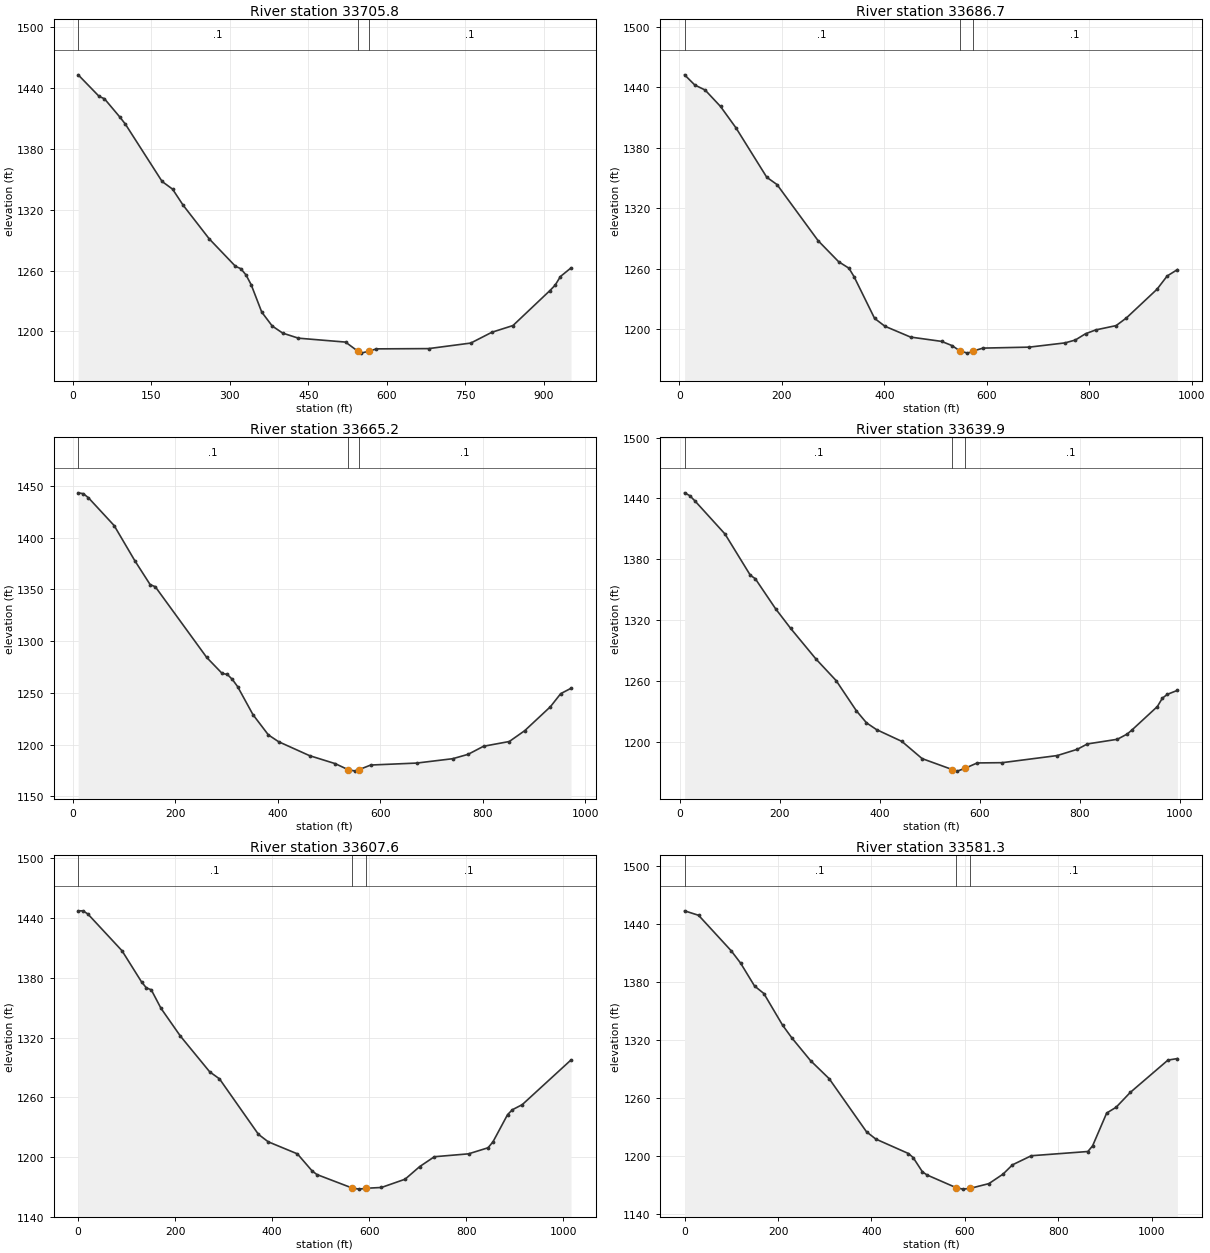
Type RM Length L Ch R = 1 ,33705.8 ,22.3,19,15.8
XS GIS Cut Line= 5
     1692072.304      223405.059     1691853.429      223105.487
     1691742.885      223003.787     1691681.497      222914.384
     1691361.166      222876.041
#Sta/Elev= 30
      10 1453.09    50.1  1431.8    60.2  1429.5    90.2 1411.11   100.3  1404.4
   170.5 1347.87   190.5 1340.31   210.6 1324.53   260.7 1291.21   310.8 1264.18
   320.9 1261.86   330.9  1255.7   340.9 1245.91     361    1219     381 1205.32
   401.1 1198.29   431.1  1193.3   521.2 1189.44     545 1180.37   550.8 1178.55
   565.8 1180.45   580.4 1182.75   680.1 1183.01   760.7 1188.48   801.1 1199.16
   841.4 1205.77     912 1240.26     922 1245.62   932.1 1254.13   952.3  1262.6
#Mann= 3 , 0 , 0
      10      .1       0     545    .045       0   565.8      .1       0
Bank Sta=545,565.8
XS Rating Curve= 0 ,0
Exp/Cntr=0.3,0.1

Type RM Length L Ch R = 1 ,33686.7 ,22.6,21.5,20.4
XS GIS Cut Line= 4
     1692090.276      223401.349     1691815.461      223043.496
     1691682.432      222904.955     1691356.192      222862.776
#Sta/Elev= 30
      10 1452.27    30.1 1442.12    50.1 1437.23    80.2 1420.92   110.3 1399.78
   170.5 1350.78   190.5 1343.56   270.7 1287.98   310.8 1267.13   330.9 1260.69
   340.9 1252.32     381 1210.99   401.1 1203.22   451.2 1192.47   511.9 1188.19
   532.1 1184.04   547.4 1178.84   562.4 1176.56   572.5 1178.48   592.7 1181.54
   683.1  1182.5   752.9 1186.71   772.9 1189.55   792.8 1195.74   812.7 1199.55
   852.6 1203.83   872.5 1211.34   932.4 1239.84   952.3    1253   972.2 1259.29
#Mann= 3 , 0 , 0
      10      .1       0   547.4    .045       0   572.5      .1       0
Bank Sta=547.4,572.5
XS Rating Curve= 0 ,0
Exp/Cntr=0.3,0.1

Type RM Length L Ch R = 1 ,33665.2 ,29.5,25.2,20.9
XS GIS Cut Line= 4
     1692093.307      223384.056     1691783.786      222976.152
     1691704.195      222901.846     1691356.192      222851.998
#Sta/Elev= 30
      10 1443.48    20.1 1442.64    30.1 1438.68    80.3 1411.79   120.5 1377.93
   150.6 1354.68   160.6 1352.65     261 1284.27   291.2 1268.77   301.2 1267.86
   311.2 1262.96   321.3 1256.11   351.4 1228.91   381.5 1209.32   401.6 1202.72
   461.8 1189.29     512 1181.54   536.6 1175.86   551.6  1174.3  558.19 1175.67
   581.3 1180.19   671.2  1182.1   741.5 1186.32   771.6 1190.56   801.7 1198.35
     852 1202.95   882.1 1213.42   932.3  1236.6   952.4 1249.24   972.5 1254.41
#Mann= 3 , 0 , 0
      10      .1       0   536.6    .045       0  558.19      .1       0
Bank Sta=536.6,558.19
XS Rating Curve= 0 ,0
Exp/Cntr=0.3,0.1

Type RM Length L Ch R = 1 ,33639.9 ,20.8,32.3,43.7
XS GIS Cut Line= 4
      1692108.07      223378.612     1691804.306      222950.347
     1691710.413      222893.762     1691353.773        222843.5
#Sta/Elev= 30
    10.1 1445.55    20.2 1442.84    30.3 1437.86    90.9 1404.91   141.4 1364.31
   151.5 1360.76   191.8 1331.29   222.1 1311.78   272.6 1281.61     313 1260.27
   353.4  1230.5   373.6 1218.62   393.8 1211.89   444.3  1200.3   484.7 1183.33
     545 1172.52     555 1170.97     570 1173.65   594.8 1179.05   644.7 1179.31
   754.7 1186.33   794.8 1192.49   814.8 1197.78   874.8 1202.38   894.8 1207.65
   904.8 1211.91   954.8 1234.69   964.8 1242.96   974.8 1246.75   994.8 1250.63
#Mann= 3 , 0 , 0
    10.1      .1       0     545    .045       0     570      .1       0
Bank Sta=545,570
XS Rating Curve= 0 ,0
Exp/Cntr=0.3,0.1

Type RM Length L Ch R = 1 ,33607.6 ,17.9,26.3,34.8
XS GIS Cut Line= 4
     1692119.314      223377.689     1691812.557       222942.39
     1691762.191      222842.902     1691609.226      222503.396
#Sta/Elev= 30
       0 1447.27      10 1447.27    20.1 1444.03    90.4 1407.19   130.6 1375.97
   140.7 1369.83   150.7    1368   170.8 1349.36     211 1321.35   271.3 1285.56
   291.4 1278.55   371.8  1222.8   391.9 1215.33   452.1 1203.21   482.3 1186.17
   492.3 1182.45     564 1169.11     579 1167.79     594 1168.66   625.5 1169.46
   674.2 1177.75   704.4 1190.45   734.6 1200.32   805.1 1203.23   845.3 1209.32
   855.4 1215.22   885.6 1242.63   895.6 1247.55   915.8 1252.61  1016.4  1297.5
#Mann= 3 , 0 , 0
       0      .1       0     564    .045       0     594      .1       0
Bank Sta=564,594
XS Rating Curve= 0 ,0
Exp/Cntr=0.3,0.1

Type RM Length L Ch R = 1 ,33581.3 ,125.2,120.1,115.1
XS GIS Cut Line= 4
      1692144.09      223386.442     1691821.884      222941.769
     1691815.461      222839.856     1691614.231      222490.162
#Sta/Elev= 30
       0  1453.4      30 1448.78    99.8 1412.15   119.8  1399.5   149.8 1375.74
   169.7 1368.03   209.7 1335.38   229.6 1322.19   269.6 1298.74   309.5 1280.07
   389.4 1225.23   409.4 1217.72   479.2  1202.8   489.2 1198.65   509.2 1183.81
   519.2  1180.6   580.6 1167.69   595.6 1166.05   610.6 1166.76   651.3 1171.74
   681.5 1181.52   701.7 1191.12     742 1200.52   863.1 1204.89   873.2  1210.7
   903.4 1244.61   923.6 1250.59   953.8 1265.87  1034.5 1299.27  1054.7 1300.85
#Mann= 3 , 0 , 0
       0      .1       0   580.6    .045       0   610.6      .1       0
Bank Sta=580.6,610.6
XS Rating Curve= 0 ,0
Exp/Cntr=0.3,0.1

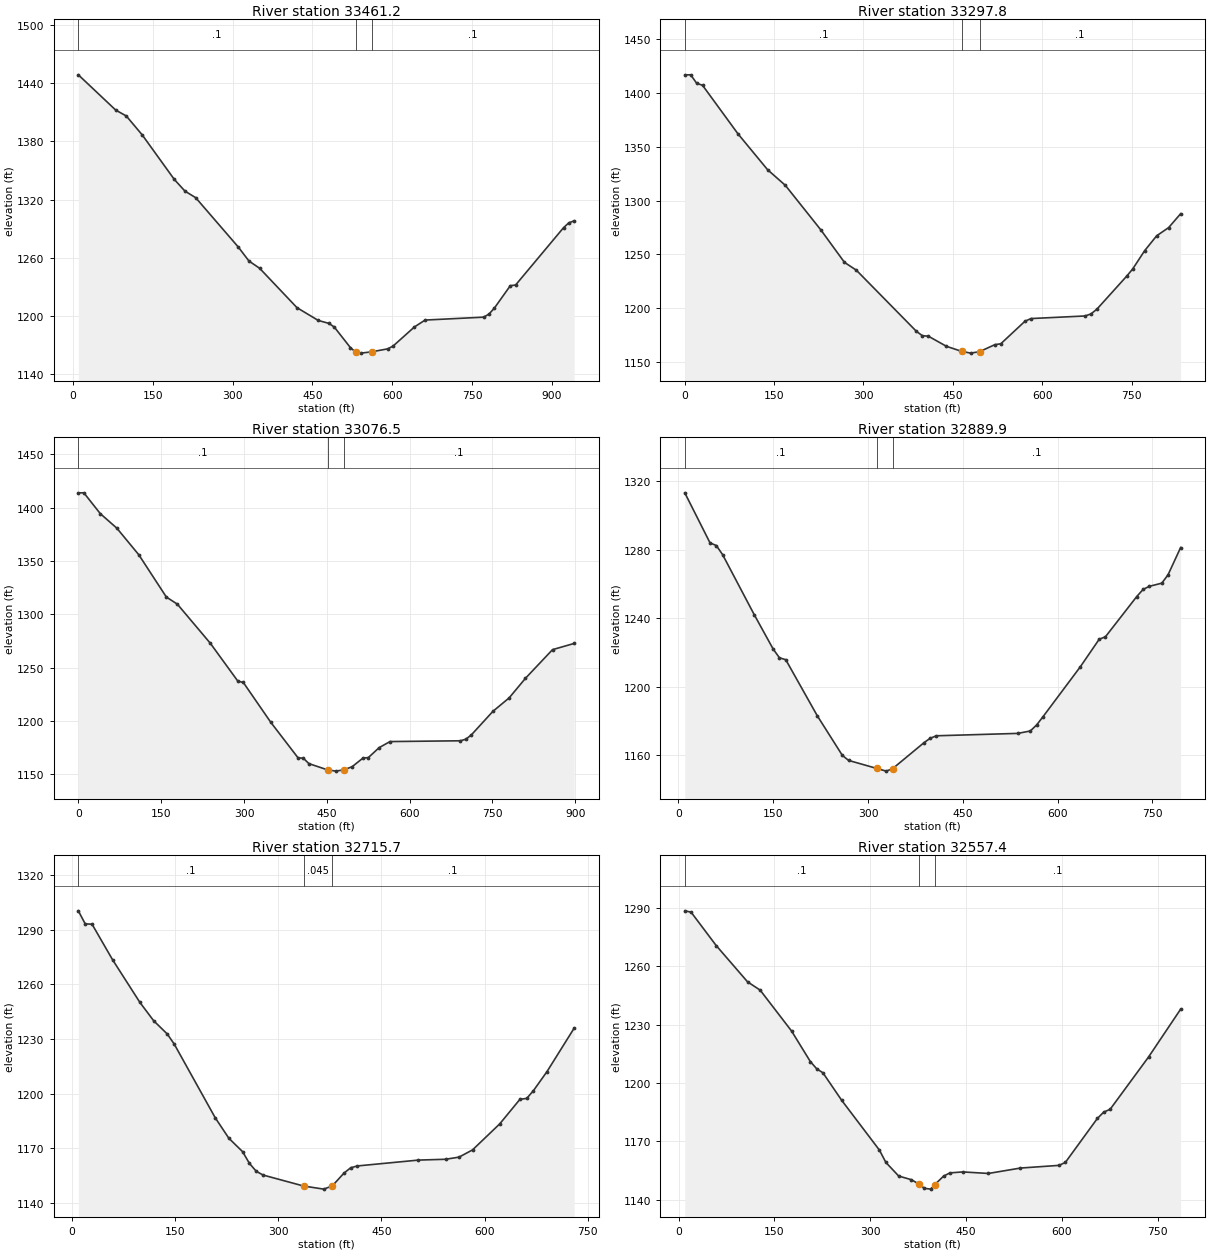
Type RM Length L Ch R = 1 ,33461.2 ,165.7,163.4,161
XS GIS Cut Line= 4
     1692188.904        223346.9     1691962.198       222980.48
      1691865.98      222737.957     1691738.128      222523.114
#Sta/Elev= 30
      10 1448.79    80.2 1412.43   100.2 1406.29   130.3 1386.61   190.4 1340.79
   210.4 1328.76   230.5 1321.99   310.6 1271.05   330.7 1256.56   350.7 1249.12
   420.9 1208.44     461 1195.23   481.1  1192.2   491.1 1188.37   521.2 1167.28
   531.2 1162.54   541.3 1161.52   561.3 1162.87   591.4 1165.94   601.5 1168.81
   641.6 1188.53   661.7 1195.65   771.8 1198.65   781.8 1201.86   791.8 1207.95
   821.8 1231.11   831.8 1231.86   921.8 1290.97   931.8 1296.03   941.8 1298.06
#Mann= 3 , 0 , 0
      10      .1       0   531.2    .045       0   561.3      .1       0
Bank Sta=531.2,561.3
XS Rating Curve= 0 ,0
Exp/Cntr=0.3,0.1

Type RM Length L Ch R = 1 ,33297.8 ,219.2,221.3,223.5
XS GIS Cut Line= 4
     1692289.077      223199.278     1692117.729      222931.712
      1692001.74      222683.917     1691851.481      222495.435
#Sta/Elev= 30
       0  1416.9     9.9  1416.9    19.9 1409.06    29.8 1407.16    89.4 1361.92
     139 1328.63   168.8 1314.11   228.4 1272.65   268.1 1242.42   287.9 1235.23
   388.7 1178.37   398.8 1174.24   408.9 1173.79   439.3 1164.36   464.9 1159.67
   479.9 1158.03   494.9  1159.4   520.4 1165.88   530.5 1166.73   571.1 1187.69
   581.2 1190.19   671.7 1192.59   681.7 1194.42   691.8 1198.89     742 1229.72
     752 1236.37   772.1 1253.39   792.2 1267.18   812.3  1274.8   832.4 1287.69
#Mann= 3 , 0 , 0
       0      .1       0   464.9    .045       0   494.9      .1       0
Bank Sta=464.9,494.9
XS Rating Curve= 0 ,0
Exp/Cntr=0.3,0.1

Type RM Length L Ch R = 1 ,33076.5 ,191.6,186.6,181.6
XS GIS Cut Line= 4
     1692441.972      223139.965     1692291.713      222814.405
     1692212.629      222582.426     1692047.872      222338.586
#Sta/Elev= 30
       0 1414.02      10 1414.02    39.8 1394.48    69.7 1380.89   109.6 1355.84
   159.4 1316.24   179.3 1309.58     239  1272.9   288.8 1237.39   298.8 1236.09
   348.6 1198.67   397.8 1165.45   407.6    1165   417.4 1159.99   451.4 1154.09
   466.4 1152.92   481.4 1154.23   495.8 1157.06   515.4 1165.15   525.2 1165.63
   544.8 1174.98   564.4 1180.65   691.9 1181.39   701.7 1182.86   711.6 1186.83
   750.8 1209.02   780.2 1221.64   809.7    1240   858.7 1266.88   897.9 1272.72
#Mann= 3 , 0 , 0
       0      .1       0   451.4    .045       0   481.4      .1       0
Bank Sta=451.4,481.4
XS Rating Curve= 0 ,0
Exp/Cntr=0.3,0.1

Type RM Length L Ch R = 1 ,32889.9 ,165.6,174.3,183
XS GIS Cut Line= 4
     1692552.688      222948.847     1692486.786      222739.275
     1692372.114      222565.292     1692180.923      222252.393
#Sta/Elev= 30
      10 1313.31    49.9 1284.09    59.9  1282.5    69.9 1277.16   119.8 1242.18
   149.8 1222.08   159.8 1216.92   169.8 1215.81   219.7 1183.04   259.4 1159.89
   269.3 1156.96   313.8 1152.28   328.8  1150.7   338.8 1152.11   388.4 1167.26
   398.3 1169.88   408.2 1171.35   537.1 1172.75   556.9 1174.16   566.8 1177.65
   576.7 1182.36   636.2 1211.75   665.9 1227.75   675.8  1229.2   725.4 1252.73
   735.3 1256.83   745.2 1258.67     765 1260.53   774.9 1265.42   794.8 1281.34
#Mann= 3 , 0 , 0
      10      .1       0   313.8    .045       0   338.8      .1       0
Bank Sta=313.8,338.8
XS Rating Curve= 0 ,0
Exp/Cntr=0.3,0.1

Type RM Length L Ch R = 1 ,32715.7 ,160.4,158.3,155.4
XS GIS Cut Line= 4
     1692601.354      222929.813     1692584.548      222652.032
     1692562.801      222506.717     1692524.247      222204.222
#Sta/Elev= 30
     9.9 1300.29    19.9 1293.12    29.8 1292.96    59.6 1273.46    99.4 1249.98
   119.3 1239.96   139.1 1232.67   149.1 1227.21   208.7 1186.72   228.6 1175.41
   248.5 1168.08   258.4 1161.67   268.4 1157.29   278.3 1155.23   337.1 1149.21
   366.4  1147.5  378.71 1149.23   395.8 1156.29   405.6 1159.24   415.4 1160.23
   503.9 1163.44   543.3 1163.89   562.9 1165.06   582.6 1169.05     622 1183.29
   651.5 1196.84   661.3  1197.3   671.1  1201.6   690.8 1212.06   730.2 1235.88
#Mann= 3 , 0 , 0
     9.9      .1       0   337.1    .045       0  378.71      .1       0
Bank Sta=337.1,378.71
XS Rating Curve= 0 ,0
Exp/Cntr=0.3,0.1

Type RM Length L Ch R = 1 ,32557.4 ,164.9,164.6,164.9
XS GIS Cut Line= 4
     1692664.724      222918.531     1692737.217      222612.742
     1692692.403      222469.073     1692552.688      222180.418
#Sta/Elev= 30
     9.8 1288.54    19.6 1287.87    58.9 1270.69     108 1252.02   127.7 1247.76
   176.8 1226.75   206.2 1211.03   216.1 1207.34   225.9 1205.25   255.3 1191.08
   314.3 1165.49   324.3  1159.2   344.4 1152.17   364.4 1150.26   376.7 1147.92
   384.5 1145.85   394.5 1145.43  400.85 1147.73   414.6  1152.1   424.6 1153.78
   444.7 1154.28   484.8 1153.49   534.9 1156.27     595 1157.64   605.1 1159.13
   655.2 1181.76   665.2 1185.04   675.2 1186.47   735.3 1213.36   785.5 1237.96
#Mann= 3 , 0 , 0
     9.8      .1       0   376.7    .045       0  400.85      .1       0
Bank Sta=376.7,400.85
XS Rating Curve= 0 ,0
Exp/Cntr=0.3,0.1

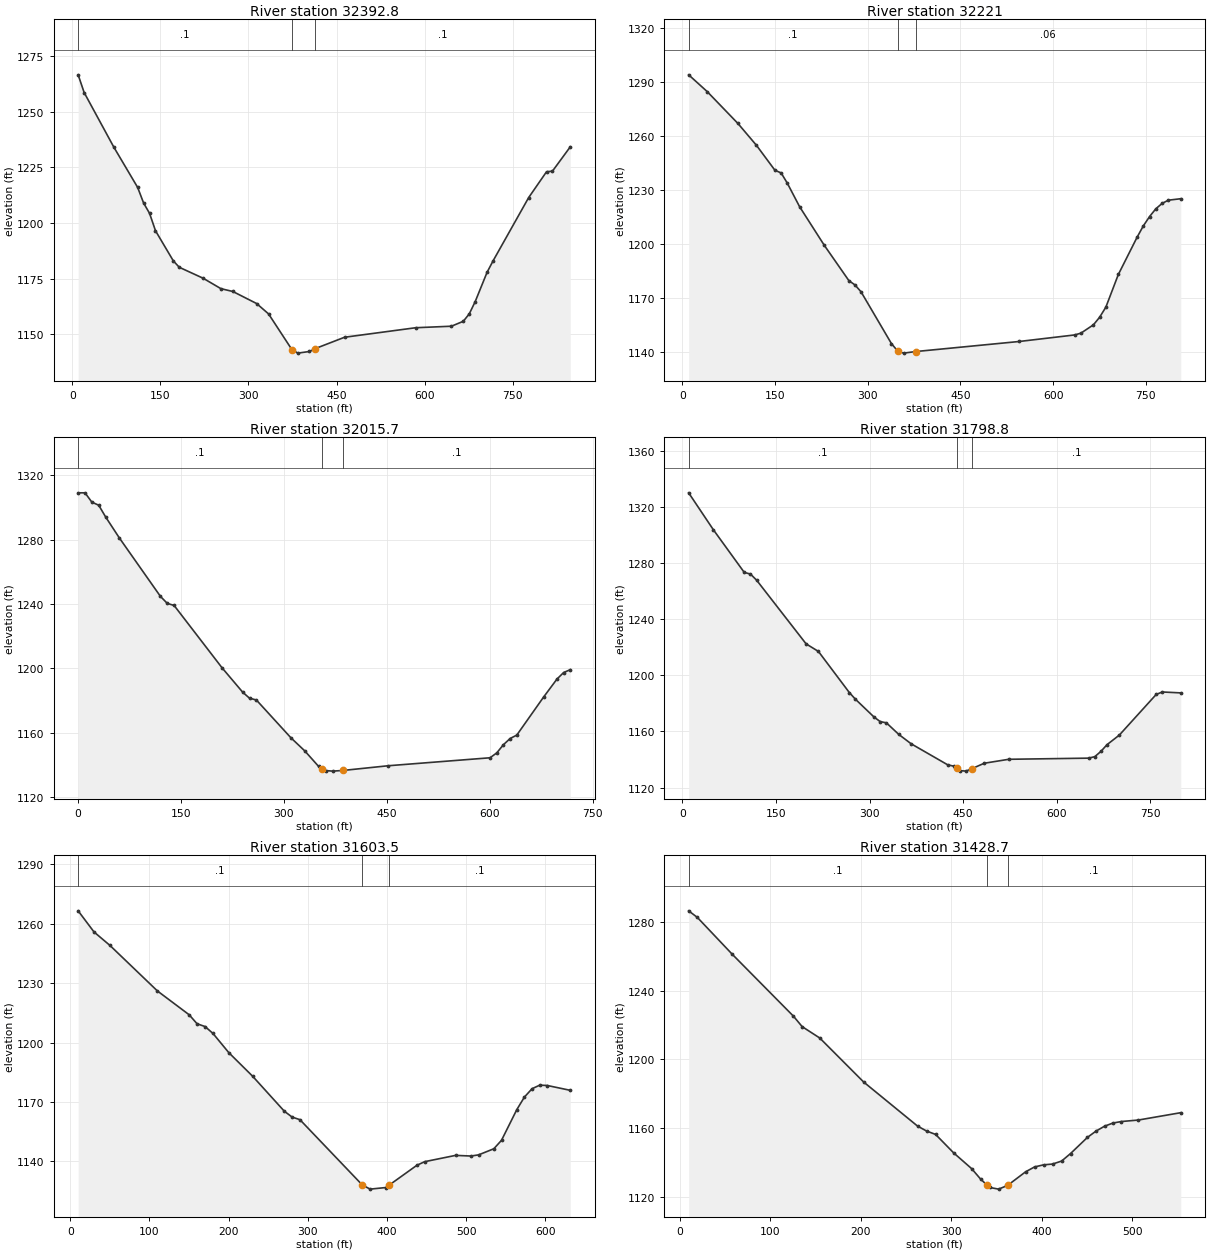
Type RM Length L Ch R = 1 ,32392.8 ,176.8,171.8,166.8
XS GIS Cut Line= 4
     1693139.451      222794.218      1692889.02      222572.784
     1692852.114      222438.342     1692603.001      222158.914
#Sta/Elev= 30
    10.1 1266.73    20.3 1258.76    70.9 1234.14   111.4 1216.03   121.6 1208.97
   131.7 1204.34   141.8 1196.51   172.2 1182.93   182.3 1180.06   222.9 1175.13
   253.2 1170.43   273.5 1169.16     314 1163.73   334.3 1159.07   374.1 1142.97
   384.1  1141.4     404 1142.14     414 1143.46   463.7 1148.55     585 1152.84
   645.7 1153.52   665.9 1155.74   676.1 1159.09   686.2 1164.63   706.4 1177.81
   716.5 1182.91   777.2 1211.45   807.6 1223.08   817.7 1223.35   848.1 1234.32
#Mann= 3 , 0 , 0
    10.1      .1       0   374.1    .045       0     414      .1       0
Bank Sta=374.1,414
XS Rating Curve= 0 ,0
Exp/Cntr=0.3,0.1

Type RM Length L Ch R = 1 ,32221   ,206.9,205.2,203.6
XS GIS Cut Line= 4
     1693185.357      222781.453     1693077.276      222545.521
     1692913.837      222264.774      1692775.44      222090.791
#Sta/Elev= 30
      10 1293.85    39.9 1284.58    89.8 1266.83   119.8 1254.69   149.7 1240.84
   159.7 1239.38   169.7 1233.69   189.6 1220.62   229.6 1199.16   269.4 1179.55
   279.2 1177.18     289 1173.39   338.3 1144.58   348.1 1140.57     358  1139.3
   377.6 1140.18     545 1145.76   634.9  1149.4     645 1150.39   665.2 1155.01
   675.3 1159.23   685.4 1164.85   705.6    1183   735.9 1203.64     746 1209.94
   756.2 1215.17   766.3 1219.47   776.4 1222.43   786.5 1224.23   806.7 1225.05
#Mann= 3 , 0 , 0
      10      .1       0   348.1    .045       0   377.6     .06       0
Bank Sta=348.1,377.6
XS Rating Curve= 0 ,0
Exp/Cntr=0.3,0.1

Type RM Length L Ch R = 1 ,32015.7 ,214.3,216.9,219.5
XS GIS Cut Line= 4
     1693355.613      222683.501     1693251.486      222423.844
     1693118.362      222232.725     1693035.324      222045.561
#Sta/Elev= 30
       0 1309.08      10 1309.08      20 1303.29      30 1301.37      40 1294.13
    59.9 1281.14   119.9 1244.74   129.9 1240.36   139.9 1239.06   209.8 1200.29
   239.8 1185.18   249.8 1181.42   259.8 1180.31   310.1 1156.83   330.4 1148.64
   350.6 1138.98   355.9 1137.66   360.8 1136.44   370.9 1136.09   385.9  1136.5
   451.9 1139.43   600.4 1144.39   610.2 1147.42   619.9 1152.51   629.7 1156.37
   639.4 1158.49   678.4 1182.09   697.9 1193.28   707.7 1197.39   717.4 1199.15
#Mann= 3 , 0 , 0
       0      .1       0   355.9    .045       0   385.9      .1       0
Bank Sta=355.9,385.9
XS Rating Curve= 0 ,0
Exp/Cntr=0.3,0.1

Type RM Length L Ch R = 1 ,31798.8 ,187.4,195.3,203.3
XS GIS Cut Line= 4
     1693456.877      222676.009     1693423.925      222310.906
     1693347.478      222163.284     1693195.901      221944.486
#Sta/Elev= 30
     9.9  1330.2    49.5 1303.88    99.1 1273.41     109 1272.28   118.9 1267.88
   198.2 1222.49     218 1217.06   267.5 1187.77   277.4 1182.95   307.1 1170.31
     317 1167.04     327 1166.15   346.8  1157.9   366.6 1151.22   425.3 1136.19
     435 1135.26   439.6 1133.78   444.8  1132.1   454.6 1131.71   464.4 1133.55
   483.9 1137.34   523.1 1140.15   651.1 1140.97     661 1142.01   670.8 1145.73
   680.7 1150.58   700.4  1157.4   759.6 1186.43   769.4 1188.16     799 1187.51
#Mann= 3 , 0 , 0
     9.9      .1       0   439.6    .045       0   464.4      .1       0
Bank Sta=439.6,464.4
XS Rating Curve= 0 ,0
Exp/Cntr=0.3,0.1

Type RM Length L Ch R = 1 ,31603.5 ,183.6,174.8,166
XS GIS Cut Line= 4
      1693710.17      222522.698     1693575.728      222288.083
     1693559.912      222091.693     1693471.602      221953.297
#Sta/Elev= 30
      10 1266.54      30 1255.88    50.1 1249.08   110.2 1226.03   150.2 1214.03
   160.2 1209.49   170.3 1208.08   180.3 1204.59   200.3 1194.89   230.3 1183.01
   270.4 1165.31   280.3 1162.33   290.1 1161.04   368.9 1128.04   378.8 1125.95
   398.5 1126.75  402.31 1127.83   437.9 1138.02   447.7 1139.82   486.7    1143
   506.1 1142.67   515.7 1143.25     535 1146.34   544.7 1150.61     564 1166.09
   573.7 1172.49   583.3 1176.68     593 1178.47   602.6  1178.3   631.6 1175.86
#Mann= 3 , 0 , 0
      10      .1       0   368.9    .045       0  402.31      .1       0
Bank Sta=368.9,402.31
XS Rating Curve= 0 ,0
Exp/Cntr=0.3,0.1

Type RM Length L Ch R = 1 ,31428.7 ,250.4,242.9,235.3
XS GIS Cut Line= 4
     1693919.515      222413.715     1693808.799      222255.548
     1693690.173      222048.613     1693626.906      221944.486
#Sta/Elev= 30
     9.7 1286.37    19.3 1282.54    57.9 1261.11   125.5 1225.14   135.1 1219.08
   154.5 1212.49     203 1186.92   262.6 1161.29   272.6 1158.41   282.5 1156.46
   302.4 1145.76   322.3 1136.59   332.2 1130.52  338.93 1127.21   342.1 1125.66
   352.1 1124.67     362 1126.81   381.9 1134.72   391.8 1137.56   401.8 1138.78
   411.7 1139.24   421.7 1140.97   431.6 1145.35   450.3 1154.76   459.7 1158.38
   469.1 1161.22   478.5 1163.08   487.8 1163.95   506.6 1164.82   553.4 1169.09
#Mann= 3 , 0 , 0
     9.7      .1       0  338.93    .045       0     362      .1       0
Bank Sta=338.93,362
XS Rating Curve= 0 ,0
Exp/Cntr=0.3,0.1