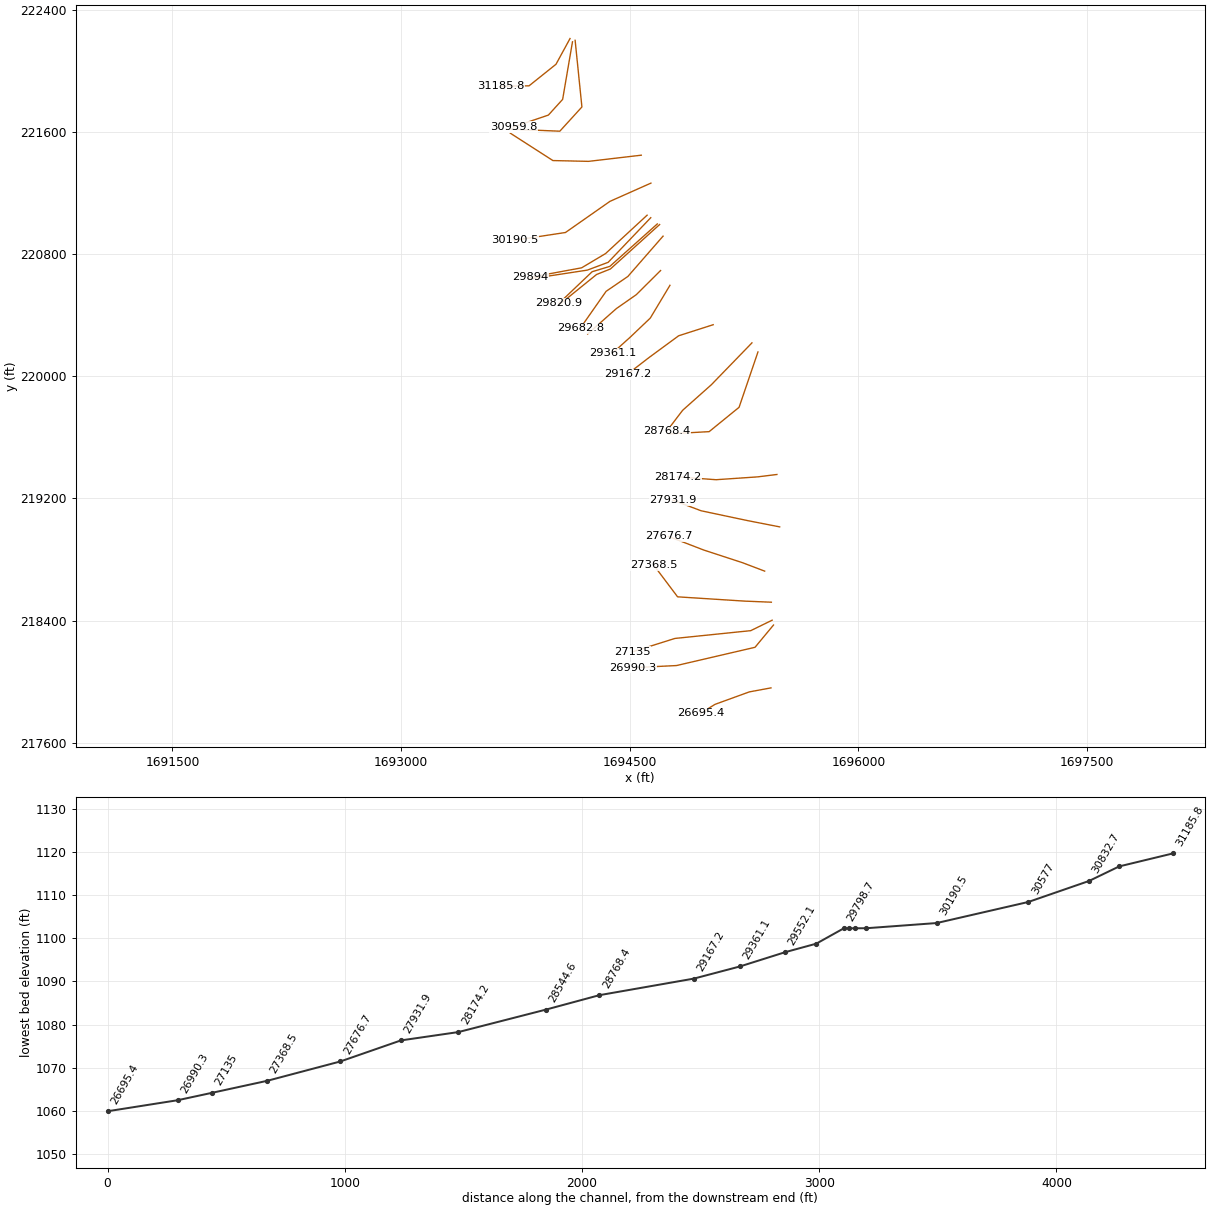
HEC-RAS study bncrk.prj: bncrk

--- bncrk.g01 (geometry) --- (continued)

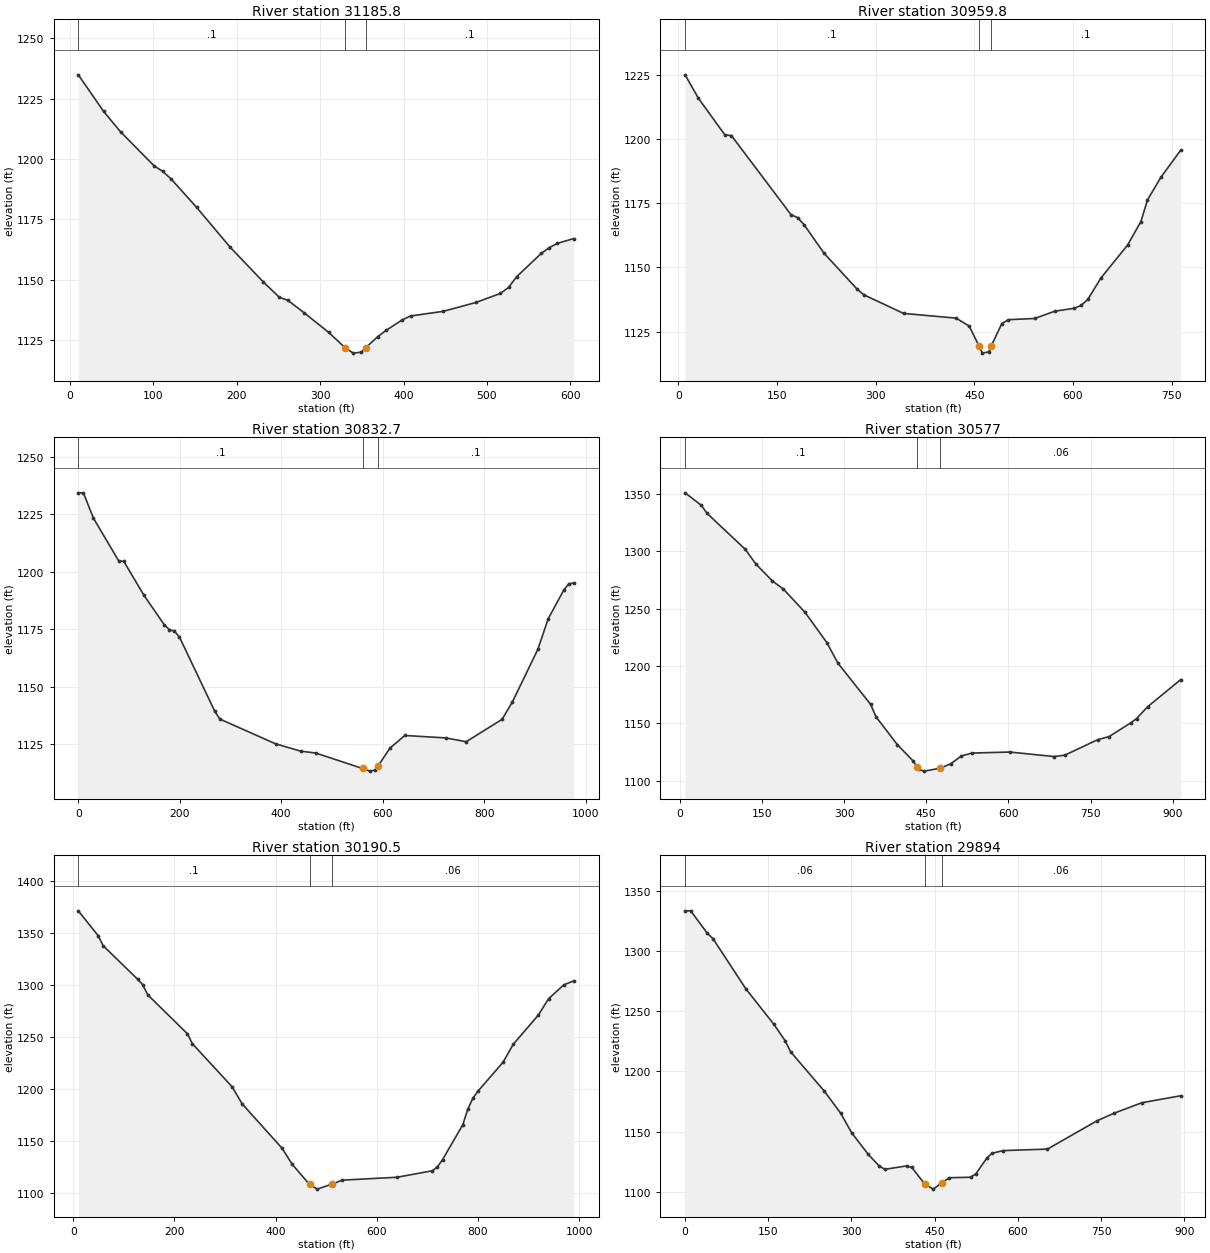
Type RM Length L Ch R = 1 ,31185.8 ,222.8,226,229.2
XS GIS Cut Line= 4
     1694107.998      222210.734     1694015.734      222042.022
     1693839.114       221900.99     1693653.267      221898.354
#Sta/Elev= 30
    10.1 1234.86    40.5 1219.69    60.7 1211.27   101.2  1197.1   111.3  1194.9
   121.4 1191.73   151.8 1180.02   192.3 1163.43   231.6 1149.21   251.3 1142.67
   261.1 1141.54   280.7 1136.36   310.2 1128.23   329.9 1121.88   339.7 1119.62
   349.5 1120.04   354.7 1121.87   369.2 1126.48     379 1129.01   398.7 1133.44
   408.5 1135.01   447.7 1136.93   486.8  1140.6   516.1 1144.32   525.9  1146.8
   535.7 1151.28     565 1160.89   574.8 1163.31   584.6 1165.09   604.2 1167.06
#Mann= 3 , 0 , 0
    10.1      .1       0   329.9    .045       0   354.7      .1       0
Bank Sta=329.9,354.7
XS Rating Curve= 0 ,0
Exp/Cntr=0.3,0.1

Type RM Length L Ch R = 1 ,30959.8 ,127.1,127.1,127.1
XS GIS Cut Line= 4
     1694124.041      222189.229     1694059.456      221812.264
     1693965.874      221709.456     1693736.532       221631.69
#Sta/Elev= 30
    10.1    1225    30.2 1215.92    70.5 1201.63    80.5 1201.34   171.1 1170.55
   181.2 1169.39   191.2 1166.56   221.4 1155.51   271.7 1141.53   281.8 1139.35
   342.2 1132.09   422.2 1130.25     442 1127.17  456.87  1119.5   461.9 1116.62
   471.8 1117.12  475.76 1119.52   491.7 1128.12   501.6 1129.64   541.7 1130.11
   571.9 1132.92   602.2  1134.1   612.3 1135.23   622.4 1137.53   642.6 1145.95
   682.9  1158.7   703.1 1167.81   713.2 1176.29   733.4 1185.04   763.6 1195.62
#Mann= 3 , 0 , 0
    10.1      .1       0  456.87    .045       0  475.76      .1       0
Bank Sta=456.87,475.76
XS Rating Curve= 0 ,0
Exp/Cntr=0.3,0.1

Type RM Length L Ch R = 1 ,30832.7 ,273,255.8,238.5
XS GIS Cut Line= 4
     1694141.389      222199.091     1694185.859      221762.599
     1694041.003      221604.011     1693717.852      221617.388
#Sta/Elev= 30
       0 1234.41      10 1234.41    29.9 1223.35    79.8 1204.72    89.7 1204.57
   129.6 1189.73   169.5 1176.97   179.5 1174.87   189.5 1174.22   199.4 1171.63
   269.2 1139.23   279.2 1135.91   388.9 1125.14   438.8 1121.93     468 1121.14
   560.4  1114.4   575.4 1113.25   585.2 1113.77   590.4 1115.29   614.5 1123.29
   643.8 1128.77   724.3 1127.71   764.7 1126.05   835.5 1135.79   855.7  1143.3
   906.2 1166.34   926.4 1179.56   956.8 1191.93   966.9 1194.85     977 1195.11
#Mann= 3 , 0 , 0
       0      .1       0   560.4    .045       0   590.4      .1       0
Bank Sta=560.4,590.4
XS Rating Curve= 0 ,0
Exp/Cntr=0.3,0.1

Type RM Length L Ch R = 1 ,30577   ,373.7,386.4,399.1
XS GIS Cut Line= 4
     1694575.469      221446.919     1694229.259      221406.498
     1693995.523      221411.771     1693716.095      221591.026
#Sta/Elev= 30
      10 1350.95    39.8 1339.97    49.8 1333.17   119.5 1301.85   139.4 1288.74
   169.3 1274.14   189.2 1267.13   229.1 1246.65   268.9  1220.2   288.8 1202.53
   348.6 1166.54   358.3 1155.81   397.3 1131.48   426.5 1117.04  433.68 1111.76
   436.2 1109.88     446 1108.39   475.2 1110.86   494.7 1114.78   514.2 1121.61
   533.6 1124.14   602.5 1125.03     683  1121.1   703.1 1122.32   763.4 1135.92
   783.6 1138.45   823.8 1150.64   833.9 1154.21     854 1164.48   914.3 1188.13
#Mann= 3 , 0 , 0
      10      .1       0  433.68    .045       0   475.2     .06       0
Bank Sta=433.68,475.2
XS Rating Curve= 0 ,0
Exp/Cntr=0.3,0.1

Type RM Length L Ch R = 1 ,30190.5 ,298.1,296.5,295
XS GIS Cut Line= 4
     1694638.736      221264.148     1694369.852      221144.644
     1694078.122      220940.784     1693742.456      220889.819
#Sta/Elev= 30
     9.8 1371.26      49 1347.36    58.8 1337.76   127.5 1305.28   137.3 1300.09
   147.1 1290.45   225.6 1252.97   235.4 1243.39     314 1201.95   333.8 1185.52
   412.9 1142.76   432.7 1127.43   467.1    1108   482.1 1103.51   511.7 1108.36
   531.5 1112.15   640.3 1114.95   710.1 1121.19     720    1125     730 1131.84
     770 1165.34     780 1180.38   789.9 1190.87   799.9 1197.64   849.9  1225.7
   869.8  1242.8   919.8 1271.14   939.7 1286.67   969.7 1299.99   989.7 1303.98
#Mann= 3 , 0 , 0
     9.8      .1       0   467.1    .045       0   511.7     .06       0
Bank Sta=467.1,511.7
XS Rating Curve= 0 ,0
Exp/Cntr=0.3,0.1

Type RM Length L Ch R = 1 ,29894   ,51.2,47.6,44
XS GIS Cut Line= 4
     1694613.473      221054.082     1694341.212       220802.94
     1694184.033      220709.523     1693849.329      220647.791
#Sta/Elev= 30
       0 1333.25      10 1333.25      40 1314.64    50.1 1310.23   110.1 1268.17
   160.2 1239.01   180.2  1225.6   190.2  1216.3   250.3 1184.03   280.3 1165.48
   300.3 1149.09   330.4 1131.07   350.4 1121.34   360.4 1118.77   399.3 1121.58
   408.9 1120.26   432.4 1106.43   447.4 1102.31   462.4 1107.31   476.3 1111.76
   514.8 1112.18   524.4 1115.04   543.6 1127.77   553.2 1132.02   573.3 1134.28
   653.4 1135.54   743.4 1159.17   773.5 1165.28   823.5    1174   893.6 1179.79
#Mann= 3 , 0 , 0
       0     .06       0   432.4    .045       0   462.4     .06       0
Bank Sta=432.4,462.4
XS Rating Curve= 0 ,0
Exp/Cntr=0.3,0.1

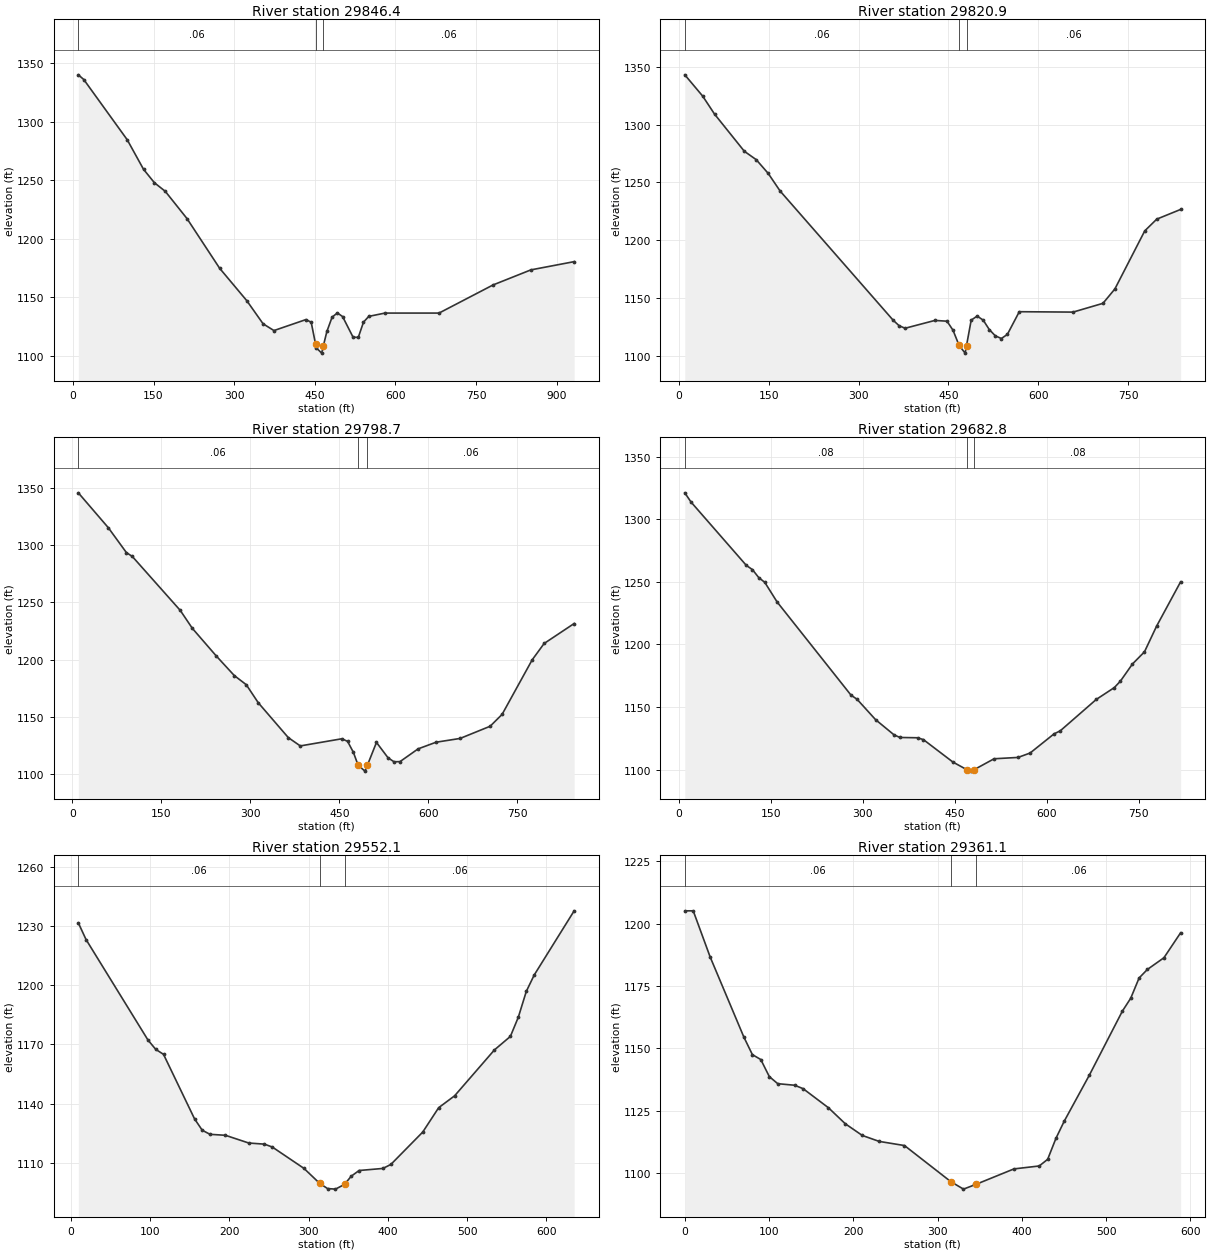
Type RM Length L Ch R = 1 ,29846.4 ,26.9,25.6,24.2
XS GIS Cut Line= 4
     1694637.445      221037.648     1694357.979      220745.422
     1694221.133      220694.433     1693843.397      220636.917
#Sta/Elev= 30
    10.1 1339.89    20.2 1335.89   101.1 1284.42   131.4 1259.23   151.6 1247.77
   171.8 1240.45   212.3 1217.14   272.9 1174.79   323.5 1147.07   353.8 1127.34
     374 1121.56   433.6 1130.95   443.3 1128.66  451.42 1109.99     453 1106.71
   462.8  1102.3  465.73 1108.17   472.5 1120.82   482.2 1133.03     492  1136.6
   501.7 1133.52   521.2  1115.9   530.9 1115.71   540.6 1128.76   550.4 1133.67
   580.5 1136.49   681.1 1136.49   781.6  1160.5     852 1173.37   932.5  1180.4
#Mann= 3 , 0 , 0
    10.1     .06       0  451.42    .045       0  465.73     .06       0
Bank Sta=451.42,465.73
XS Rating Curve= 0 ,0
Exp/Cntr=0.3,0.1

Type RM Length L Ch R = 1 ,29820.9 ,20.4,22.2,24
XS GIS Cut Line= 4
     1694680.447       220996.87     1694369.033      220718.892
     1694253.098      220684.051     1694036.163      220477.885
#Sta/Elev= 30
     9.9 1343.09    39.8 1324.65    59.6 1309.08   109.3 1276.95   129.2 1269.67
   149.1 1257.84     169 1242.59   357.8 1130.77   367.7 1126.04   377.7 1123.81
   427.5 1130.59   447.7 1129.92   457.8 1122.06   467.9 1108.94     478 1102.29
  480.31 1108.84   488.1 1130.83   498.1 1134.35   508.2 1130.82   518.3  1122.7
   528.4 1117.24   538.5 1114.94   548.5 1118.49   568.4 1138.13   658.2 1137.79
   708.1 1145.37     728 1157.79   777.9 1208.06   797.9 1218.21   837.8 1226.62
#Mann= 3 , 0 , 0
     9.9     .06       0   467.9    .045       0  480.31     .06       0
Bank Sta=467.9,480.31
XS Rating Curve= 0 ,0
Exp/Cntr=0.3,0.1

Type RM Length L Ch R = 1 ,29798.7 ,111.4,115.9,120.3
XS GIS Cut Line= 4
     1694695.522      220992.793      1694372.64      220701.851
     1694282.167      220665.941     1694038.141      220468.864
#Sta/Elev= 30
    10.1 1345.94    60.6 1315.42      91 1293.69   101.1  1290.2   181.9 1242.98
   202.2  1227.3   242.6 1203.07   272.9 1185.96   293.1 1177.94   313.3 1162.15
   363.9 1131.64   384.1 1124.35   454.1 1130.61   463.8 1128.35   473.6 1118.72
  481.43  1107.6     493 1102.28   497.2 1107.45   512.5 1127.42     532 1113.94
   542.1 1110.46   552.2 1110.62   582.6 1121.76   612.9 1127.59   653.4  1130.9
     704 1141.56   724.2 1151.98   774.8 1199.66     795 1214.03   845.6 1231.52
#Mann= 3 , 0 , 0
    10.1     .06       0  481.43    .045       0   497.2     .06       0
Bank Sta=481.43,497.2
XS Rating Curve= 0 ,0
Exp/Cntr=0.3,0.1

Type RM Length L Ch R = 1 ,29682.8 ,130.5,130.7,130.9
XS GIS Cut Line= 4
     1694718.186      220916.997      1694487.15      220652.799
     1694344.549      220555.521     1694175.418      220314.536
#Sta/Elev= 30
      10 1320.99    20.1 1313.67   110.3 1263.02   120.3 1259.62   130.4 1253.36
   140.4 1249.46   160.4 1233.85   280.8 1159.45   290.8 1156.08   320.9 1139.83
     351  1127.7   360.6 1125.61   389.3 1125.37   398.9 1123.88   446.9 1105.98
  469.94  1099.8   475.6 1098.73  481.74 1099.96     514  1108.6     553 1109.67
   572.7 1113.18   611.9 1128.55   621.7 1130.85   680.6 1156.01     710 1165.46
   719.9 1170.62   739.5 1184.29   759.1 1194.01   778.7 1214.37     818 1249.94
#Mann= 3 , 0 , 0
      10     .08       0  469.94    .045       0  481.74     .08       0
Bank Sta=469.94,481.74
XS Rating Curve= 0 ,0
Exp/Cntr=0.3,0.1

Type RM Length L Ch R = 1 ,29552.1 ,188,191,194
XS GIS Cut Line= 4
     1694701.865      220691.688      1694542.38      220533.521
     1694411.893      220442.575      1694223.41      220276.499
#Sta/Elev= 30
     9.8 1231.57    19.5 1223.15    97.7 1172.19   107.4 1167.53   117.2 1165.01
   156.3 1132.36     166 1126.59   175.8 1124.52   195.3 1124.02   224.6 1120.12
   244.5 1119.54   254.4 1118.07   294.2 1107.29   314.1 1099.68     324 1097.05
     334 1096.77  345.42 1099.17   353.8  1103.3   363.8  1106.2   393.7 1107.24
   403.8 1109.26     444 1125.66   464.1 1138.01   484.2 1144.02   534.4 1167.26
   554.5 1174.09   564.5 1183.81   574.6 1196.92   584.6 1205.22   634.9 1237.67
#Mann= 3 , 0 , 0
     9.8     .06       0   314.1    .045       0  345.42     .06       0
Bank Sta=314.1,345.42
XS Rating Curve= 0 ,0
Exp/Cntr=0.3,0.1

Type RM Length L Ch R = 1 ,29361.1 ,196.4,193.9,191.3
XS GIS Cut Line= 4
     1694763.414      220595.129     1694634.244      220380.285
     1694503.756      220256.388     1694386.449      220150.943
#Sta/Elev= 30
       0  1205.1      10  1205.1    30.1 1186.58    70.2 1154.37    80.2 1147.42
    90.2 1145.44   100.3  1138.6   110.3 1135.76   130.4 1135.13   140.4 1133.76
   170.5 1126.09   190.5 1119.67   210.6    1115   230.6 1112.61   260.7 1110.94
   315.7 1096.46   330.7 1093.46   345.7  1095.4   390.6 1101.57   420.6 1102.75
   430.6 1105.41   440.5 1113.88   450.3 1120.74   479.9 1139.06   519.3 1164.88
   529.2 1170.05   539.1 1178.15   548.9 1181.57   568.6 1186.28   588.4  1196.3
#Mann= 3 , 0 , 0
       0     .06       0   315.7    .045       0   345.7     .06       0
Bank Sta=315.7,345.7
XS Rating Curve= 0 ,0
Exp/Cntr=0.3,0.1

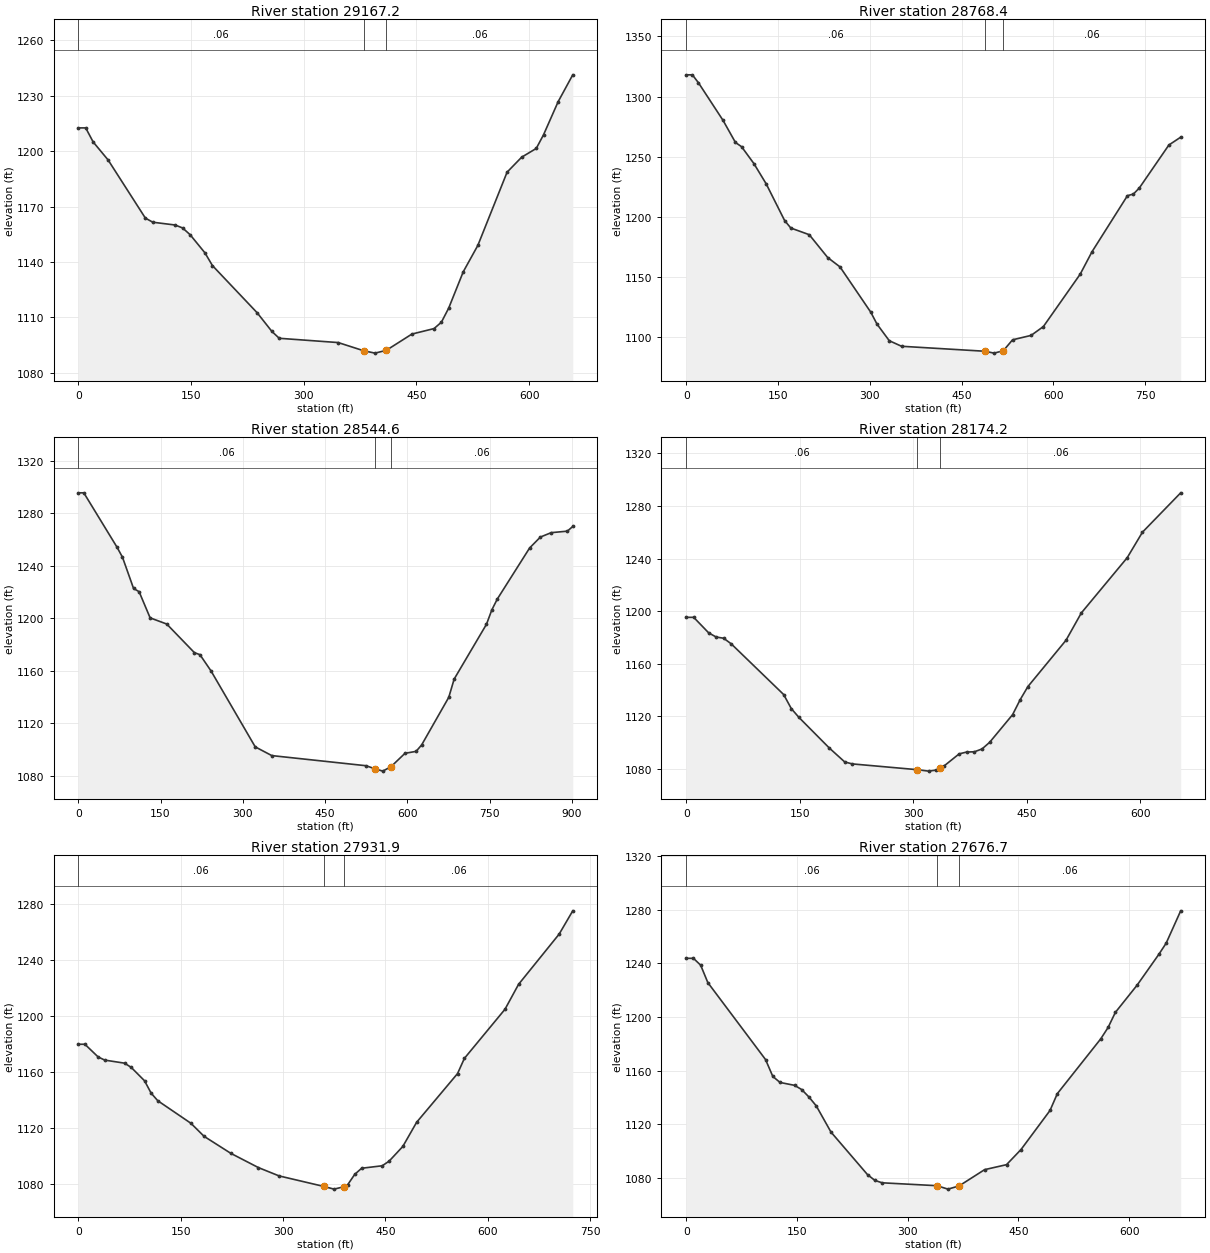
Type RM Length L Ch R = 1 ,29167.2 ,397,398.8,400.7
XS GIS Cut Line= 4
     1695047.197       220337.13     1694820.491      220264.637
     1694622.782      220119.651     1694484.386      220012.888
#Sta/Elev= 30
       0 1212.64     9.9 1212.64    19.8 1205.03    39.7 1195.27    89.3 1163.78
    99.2 1161.55   128.9 1160.04   138.8 1158.45   148.8 1154.81   168.6 1144.94
   178.5 1138.08     238 1112.53   257.6 1102.43   267.4 1098.69   345.9 1096.37
   379.9 1091.92   394.9 1090.65   409.9 1092.17     444 1100.98   473.4 1103.94
   483.2 1107.39   492.9 1115.02   512.3 1134.72   531.7 1148.99   570.6 1188.65
     590 1196.77   609.4  1201.5   619.1 1208.89   638.6 1226.87     658 1241.38
#Mann= 3 , 0 , 0
       0     .06       0   379.9    .045       0   409.9     .06       0
Bank Sta=379.9,409.9
XS Rating Curve= 0 ,0
Exp/Cntr=0.3,0.1

Type RM Length L Ch R = 1 ,28768.4 ,224.7,223.8,222.9
XS GIS Cut Line= 4
     1695301.182      220218.164     1695034.934      219944.008
     1694846.452      219776.615     1694741.007      219638.218
#Sta/Elev= 30
       0  1318.1    10.1  1318.1    20.1 1311.44    60.3 1280.18    80.5 1261.89
    90.5 1258.36   110.6 1244.38   130.7 1227.53   160.9 1196.97     171 1190.78
   201.1 1185.24   231.3 1166.24   251.4 1158.46   301.7 1120.81   311.8 1110.97
   331.9 1097.13     352 1092.51   488.2 1088.37   503.2 1086.81   518.2 1088.76
   533.4 1097.87   563.7 1101.54   583.8  1108.9   643.9 1152.39   663.2 1171.02
   721.2 1217.68   730.9 1219.02   740.6 1224.06   788.9 1259.78   808.2 1266.28
#Mann= 3 , 0 , 0
       0     .06       0   488.2    .045       0   518.2     .06       0
Bank Sta=488.2,518.2
XS Rating Curve= 0 ,0
Exp/Cntr=0.3,0.1

Type RM Length L Ch R = 1 ,28544.6 ,382.7,370.4,358.1
XS GIS Cut Line= 4
     1695340.724      220158.852     1695216.826      219796.385
     1695020.435        219636.9     1694755.506      219622.402
#Sta/Elev= 30
       0 1295.59    10.1 1295.59    70.6 1254.18    80.6 1246.51   100.8  1222.7
   110.9 1220.25     131  1200.3   161.3 1195.59   211.7 1173.78   221.8 1172.24
   241.9 1159.92   322.6 1101.97   352.8 1095.33   524.7  1087.6   540.1 1085.36
   555.1 1083.49   570.1  1086.9   595.6 1097.07   615.8 1098.55   625.9 1103.43
   675.4 1139.75   685.2 1153.66   744.1  1195.4     754 1206.49   763.8  1214.6
   822.8 1253.58   842.4 1261.89   862.1 1265.23   891.5 1266.38   901.4 1269.94
#Mann= 3 , 0 , 0
       0     .06       0   540.1    .045       0   570.1     .06       0
Bank Sta=540.1,570.1
XS Rating Curve= 0 ,0
Exp/Cntr=0.3,0.1

Type RM Length L Ch R = 1 ,28174.2 ,247.8,242.2,236.7
XS GIS Cut Line= 4
     1695465.021      219356.494      1695337.17      219340.678
      1695065.65      219322.225       1694813.9      219340.678
#Sta/Elev= 30
       0 1195.26     9.9 1195.26    29.7 1183.45    39.6 1180.28    49.5 1179.36
    59.5 1175.09   128.8 1136.52   138.9 1125.82     149 1119.11   189.3 1095.74
   209.5 1085.24   219.5 1083.76   305.3 1079.37   320.3 1078.27   330.4 1079.05
   335.3 1080.52   340.5 1082.08   360.7 1091.41   370.7  1092.8   380.8 1092.99
   390.9 1095.13     401 1100.21   431.3 1121.23   441.4 1132.72   451.5 1142.58
   501.9 1177.86   522.1 1198.59   582.7 1240.59   602.9 1260.04   653.4 1289.97
#Mann= 3 , 0 , 0
       0     .06       0   305.3    .045       0   335.3     .06       0
Bank Sta=305.3,335.3
XS Rating Curve= 0 ,0
Exp/Cntr=0.3,0.1

Type RM Length L Ch R = 1 ,27931.9 ,257.4,255.2,253.1
XS GIS Cut Line= 4
     1695483.074      219013.459     1695273.503      219054.318
     1694967.713      219118.903     1694781.867       219188.76
#Sta/Elev= 30
       0 1179.82     9.7 1179.82    29.1 1170.76    38.8  1168.5    67.9 1166.31
    77.6 1163.28    97.1 1153.74   106.8 1144.89   116.5 1139.48     165  1123.4
   184.4 1114.04   223.6 1101.89   263.9 1091.74   294.2 1085.79   359.8 1078.26
   374.8 1076.34   389.8 1078.09     395 1079.63   405.1 1086.87   415.2 1091.25
   445.4 1093.02   455.5 1096.32   475.6 1106.84   495.8 1124.07   555.8 1158.89
   565.8 1169.73   625.3 1204.82   645.2 1222.62   704.7 1258.52   724.6 1275.12
#Mann= 3 , 0 , 0
       0     .06       0   359.8    .045       0   389.8     .06       0
Bank Sta=359.8,389.8
XS Rating Curve= 0 ,0
Exp/Cntr=0.3,0.1

Type RM Length L Ch R = 1 ,27676.7 ,303.1,308.2,313.3
XS GIS Cut Line= 4
      1695384.62      218723.826     1695238.315      218779.185
      1694983.93      218862.223     1694754.588      218950.533
#Sta/Elev= 30
       0 1243.78     9.8 1243.78    19.6 1238.65    29.3 1225.65   107.5 1168.18
   117.3 1155.62   127.1 1151.11   146.7 1148.96   156.4 1145.83   166.3 1140.22
   176.2 1133.59   196.1 1114.08   245.6  1082.3   255.5    1078   265.4 1076.19
   339.6 1074.03   354.6 1071.47   369.6 1073.85   404.2 1086.01   433.9 1089.73
   453.5 1101.02   492.8 1130.19   502.7 1142.75   561.6 1183.72   571.5 1192.18
   581.3  1203.4   610.8 1223.76   640.3 1246.83   650.1 1255.06   669.8 1279.23
#Mann= 3 , 0 , 0
       0     .06       0   339.6    .045       0   369.6     .06       0
Bank Sta=339.6,369.6
XS Rating Curve= 0 ,0
Exp/Cntr=0.3,0.1

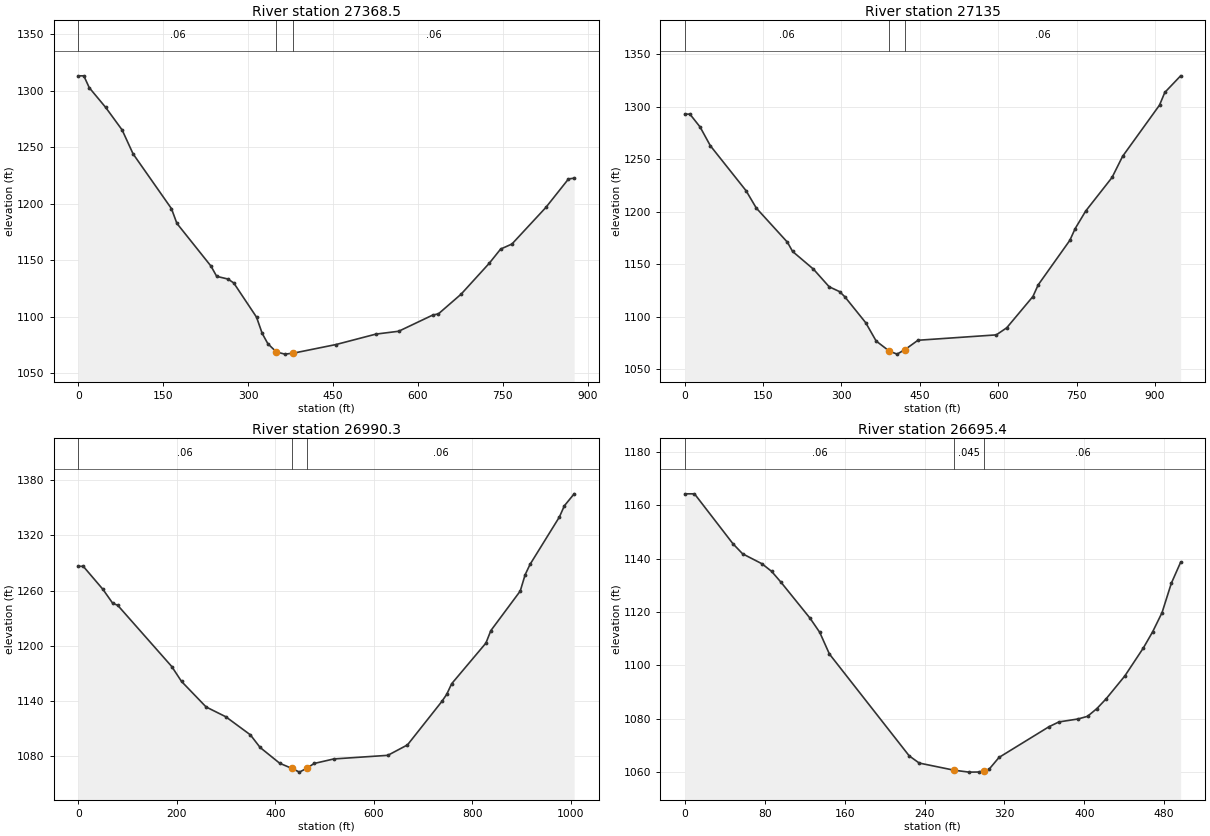
Type RM Length L Ch R = 1 ,27368.5 ,230.2,233.6,236.9
XS GIS Cut Line= 4
     1695428.594      218520.285      1695254.61      218527.315
       1694813.5      218555.433     1694657.091      218762.808
#Sta/Elev= 30
       0 1313.38     9.7 1313.38    19.3 1302.88    48.4 1285.35    77.4 1265.43
    96.7  1244.3   164.5 1195.81   174.1 1182.75   234.4 1144.87   244.4 1135.86
   264.5 1133.44   274.6 1129.97   314.8 1099.72   324.8 1085.33   334.9 1076.14
     350 1068.85     365 1066.99     380 1067.86   455.4 1075.51   525.7 1084.72
   565.9 1087.24   626.1 1101.58   636.1 1102.64   676.1 1120.03     726 1147.48
     746    1160     766 1164.48   825.9 1196.84   865.9 1222.09   875.9 1222.78
#Mann= 3 , 0 , 0
       0     .06       0     350    .045       0     380     .06       0
Bank Sta=350,380
XS Rating Curve= 0 ,0
Exp/Cntr=0.3,0.1

Type RM Length L Ch R = 1 ,27135   ,142.1,144.6,147.1
XS GIS Cut Line= 4
     1695433.867      218402.538     1695293.274         218334.
     1694795.926      218283.034     1694516.498      218195.164
#Sta/Elev= 30
       0 1292.99     9.8 1292.99    29.3 1280.72    48.9 1262.88   117.3    1220
   136.9 1203.44   196.4 1170.93   206.4 1162.09   246.4 1145.17   276.4 1128.42
   296.4 1123.78   306.4 1118.88   346.4 1094.14   366.4 1076.67   391.4 1067.13
   406.4  1064.2   421.4 1068.45   446.4 1077.42   596.4 1082.55   616.4 1089.32
   666.5 1119.12   676.6 1130.23   737.2 1172.69   747.3 1183.79   767.5 1200.58
     818 1232.62   838.2 1252.76   908.9  1301.6     919 1313.68   949.3 1329.51
#Mann= 3 , 0 , 0
       0     .06       0   391.4    .045       0   421.4     .06       0
Bank Sta=391.4,421.4
XS Rating Curve= 0 ,0
Exp/Cntr=0.3,0.1

Type RM Length L Ch R = 1 ,26990.3 ,292.5,294.9,297.4
XS GIS Cut Line= 4
     1695442.654      218370.905     1695321.392       218225.04
      1694806.47      218105.536     1694518.255      218091.477
#Sta/Elev= 30
       0 1286.34      10 1286.34    49.9 1261.31    69.9 1246.08    79.9 1243.96
   189.7 1177.34   209.6  1161.1   259.5 1133.35   299.4 1122.73   349.3 1103.07
   369.2  1089.3   409.1 1072.09     434 1066.47     449 1062.49     464 1066.74
   478.9  1071.9   518.8 1076.83   628.5 1080.76   668.4  1092.1   738.2 1139.35
   748.1 1147.11   758.1 1158.61   827.7 1202.85   837.7  1216.4   897.4 1259.43
   907.3  1277.1   917.3 1288.42     977 1340.05     987 1352.15  1006.9 1365.16
#Mann= 3 , 0 , 0
       0     .06       0     434    .045       0     464     .06       0
Bank Sta=434,464
XS Rating Curve= 0 ,0
Exp/Cntr=0.3,0.1

Type RM Length L Ch R = 1 ,26695.4 ,454.8,452.8,450.7
XS GIS Cut Line= 4
     1695426.139      217959.352     1695283.788      217932.991
       1695058.4      217851.272       1694963.5      217791.959
#Sta/Elev= 30
       0 1164.36     9.7 1164.36    48.3 1145.59    57.9 1141.85    77.2 1138.13
    86.9 1135.28    96.5  1131.1   125.5 1117.64   135.1 1112.38   144.8 1104.25
   224.7 1066.03   234.7 1063.34   269.6 1060.66   284.6 1059.94   294.6 1059.99
   299.6  1060.5   304.6 1061.01   314.6 1065.46   364.5 1076.95   374.5 1078.77
   393.8 1079.89   403.2 1080.88   412.5 1083.76   421.8 1087.44   440.5 1096.01
   459.1 1106.54   468.4  1112.6   477.8 1119.79   487.1 1130.81   496.4 1138.68
#Mann= 3 , 0 , 0
       0     .06       0   269.6    .045       0   299.6     .06       0
Bank Sta=269.6,299.6
XS Rating Curve= 0 ,0
Exp/Cntr=0.3,0.1