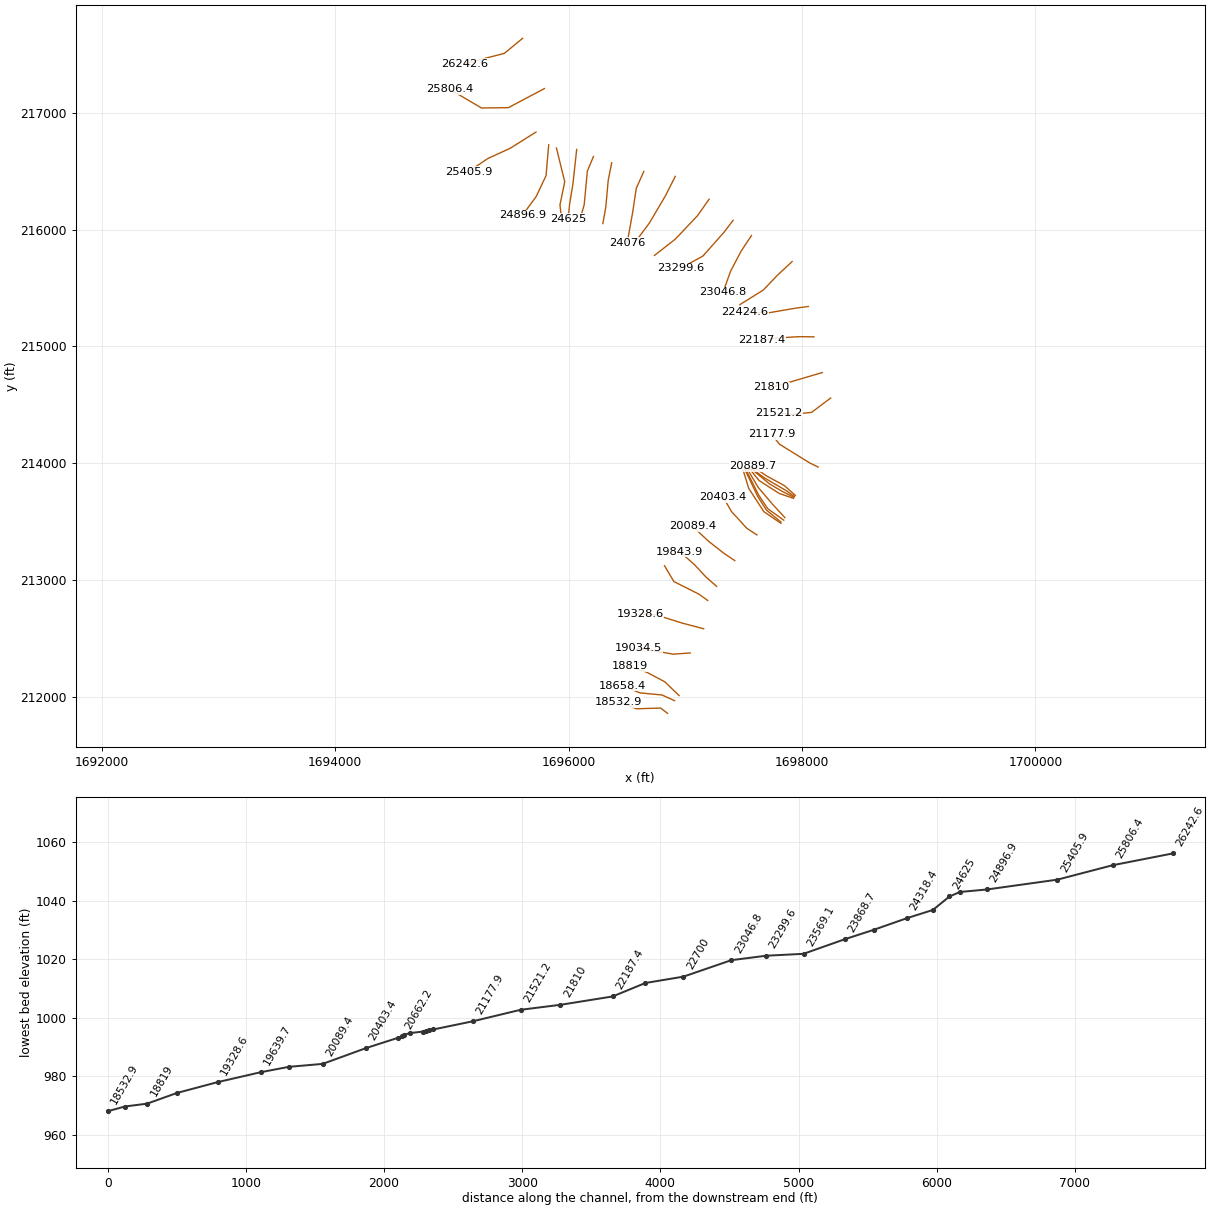
HEC-RAS study bncrk.prj: bncrk

--- bncrk.g01 (geometry) --- (continued)

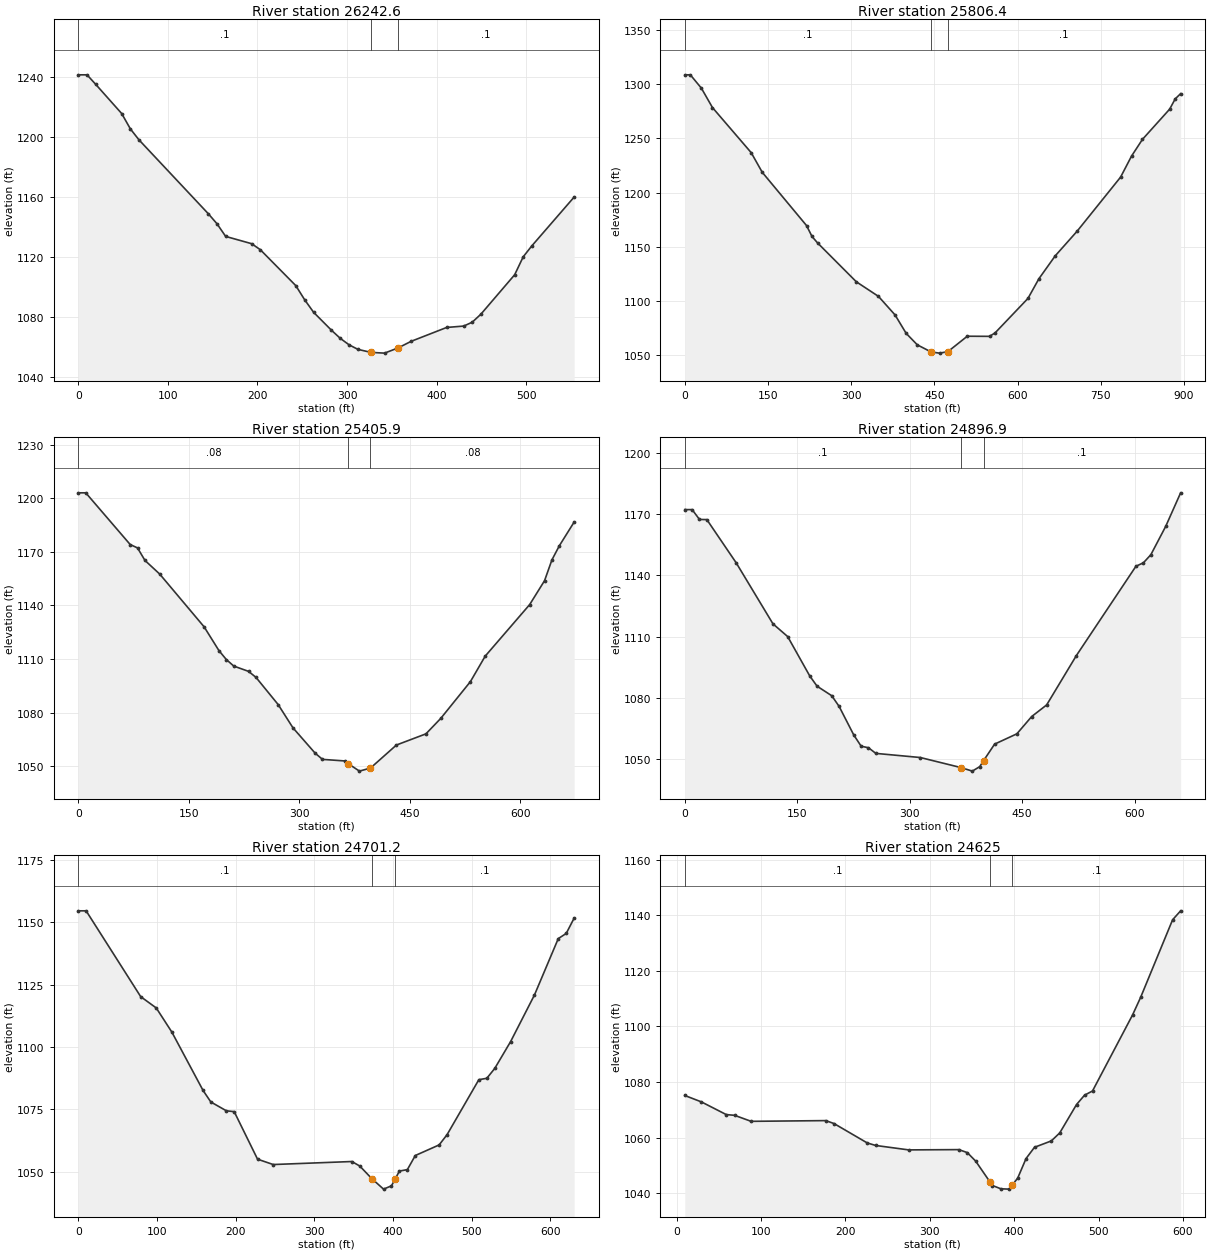
Type RM Length L Ch R = 1 ,26242.6 ,440.9,436.2,431.4
XS GIS Cut Line= 4
     1695605.395      217637.746     1695448.546      217508.576
     1695246.883      217457.172     1695109.805      217418.948
#Sta/Elev= 30
       0 1241.66     9.7 1241.66    19.4 1235.32    48.4 1215.86    58.1 1205.63
    67.7 1198.33   145.1 1149.09   154.8  1142.4   164.5 1133.96   193.5 1129.11
   203.2  1125.1   242.8 1101.16   252.7 1091.74   262.7 1083.37   282.5  1071.5
   292.4 1066.05   302.3  1061.7   312.2 1058.66   326.9 1056.65   341.9 1056.17
   356.9 1059.61   371.7 1064.06   411.3 1073.29   430.3  1074.2   439.8 1076.79
   449.3 1082.01   487.2 1108.42   496.7 1120.36   506.2 1127.56   553.6  1160.2
#Mann= 3 , 0 , 0
       0      .1       0   326.9    .045       0   356.9      .1       0
Bank Sta=326.9,356.9
XS Rating Curve= 0 ,0
Exp/Cntr=0.3,0.1

Type RM Length L Ch R = 1 ,25806.4 ,392.1,400.6,409.1
XS GIS Cut Line= 4
     1695792.378      217207.499     1695483.804      217044.125
     1695253.473       217041.16     1694982.212      217200.469
#Sta/Elev= 30
       0 1308.45      10 1308.45    29.9 1296.16    49.9 1278.29   119.7 1236.79
   139.7 1218.66   219.5 1169.63   229.4 1159.57   239.4 1153.64   309.3 1117.84
   349.2 1104.41   379.2 1087.27   399.2 1070.33   419.3 1059.75   444.3 1053.17
   459.3 1052.13   474.3 1053.46   509.4  1067.7   549.5 1067.58   559.5 1070.76
   618.8 1102.52   638.5  1120.6     668 1141.75   707.3 1164.34   785.9 1214.27
   805.6 1233.62   825.3 1249.03   874.4 1276.88   884.3 1286.28   894.1  1291.1
#Mann= 3 , 0 , 0
       0      .1       0   444.3    .045       0   474.3      .1       0
Bank Sta=444.3,474.3
XS Rating Curve= 0 ,0
Exp/Cntr=0.3,0.1

Type RM Length L Ch R = 1 ,25405.9 ,495,509,522.9
XS GIS Cut Line= 4
     1695720.325      216834.927     1695498.891      216696.092
     1695307.333      216608.221     1695140.379      216495.747
#Sta/Elev= 30
       0 1203.08    10.1 1203.08    70.4 1174.13    80.4 1172.22    90.5 1165.21
   110.6 1157.54   170.9 1127.98     191 1114.68     201  1109.7   211.1 1106.04
   231.2 1103.07   241.3  1099.7   271.4 1084.47   291.5 1071.44   321.6 1057.26
   331.6 1053.77   361.7  1052.9   366.8  1051.3   381.8 1047.19   396.8 1048.92
     432 1061.81   472.1 1068.07   492.2 1076.72   532.5 1097.32   552.6 1111.61
     613 1140.49   633.2 1153.88   643.2 1165.51   653.3 1173.45   673.4 1186.73
#Mann= 3 , 0 , 0
       0     .08       0   366.8    .045       0   396.8     .08       0
Bank Sta=366.8,396.8
XS Rating Curve= 0 ,0
Exp/Cntr=0.3,0.1

Type RM Length L Ch R = 1 ,24896.9 ,190.9,195.7,200.4
XS GIS Cut Line= 4
     1695829.284      216725.968     1695806.438      216462.356
     1695722.082        216283.1     1695604.335      216123.176
#Sta/Elev= 30
       0 1172.38     9.8 1172.38    19.6 1167.54    29.4 1167.47    68.6 1146.19
   117.6 1116.22   137.2 1109.97   166.6 1090.65   176.4 1085.59     196 1080.89
   205.8 1075.66   225.4 1061.57   235.2 1056.08     245 1055.32   254.8 1052.55
   314.1 1050.52   368.5 1045.56   383.5 1043.83   393.4 1046.05   398.5 1048.99
   413.2  1057.1   442.9 1062.17   462.7 1070.68   482.6 1076.36   522.3 1100.66
   601.7 1144.53   611.7 1146.25   621.6 1150.21   641.4 1164.14   661.3 1180.63
#Mann= 3 , 0 , 0
       0      .1       0   368.5    .045       0   398.5      .1       0
Bank Sta=368.5,398.5
XS Rating Curve= 0 ,0
Exp/Cntr=0.3,0.1

Type RM Length L Ch R = 1 ,24701.2 ,75.4,76.2,77.1
XS GIS Cut Line= 4
     1695895.367       216697.97     1695966.543      216409.316
     1695925.683      216211.607     1695940.182      216081.119
#Sta/Elev= 30
       0 1154.68     9.9 1154.68    79.3 1120.24    99.1 1115.69   118.9 1106.02
   158.6 1082.59   168.5 1077.96   188.3 1074.41   198.2 1074.08   227.9    1055
   247.8 1052.85   347.8 1054.06   357.9 1052.25   373.1 1047.22   388.1 1042.98
   398.2  1044.3   403.1 1047.17   408.3 1050.23   418.4 1050.81   428.5 1056.47
   458.8 1060.72   468.9 1064.84   509.3 1086.91   519.4 1087.46   529.5 1091.41
   549.7  1102.2     580 1120.89   610.3 1143.53   620.4  1145.6   630.5 1151.77
#Mann= 3 , 0 , 0
       0      .1       0   373.1    .045       0   403.1      .1       0
Bank Sta=373.1,403.1
XS Rating Curve= 0 ,0
Exp/Cntr=0.3,0.1

Type RM Length L Ch R = 1 ,24625   ,118.4,119.7,121.1
XS GIS Cut Line= 4
     1696068.925      216686.181     1696036.868      216393.241
     1696008.127      216216.372     1695995.967      216093.669
#Sta/Elev= 30
     9.8 1075.13    29.5 1072.82    58.9 1068.26    68.8 1067.99    88.4 1065.83
   176.8 1066.09   186.6 1065.03   225.9 1058.06   235.8 1057.15     275 1055.55
   334.5 1055.65   344.5 1054.57   354.4 1051.51  371.53 1043.93   374.3 1042.73
   384.3 1041.54   394.2 1041.43  397.95 1042.97   404.2 1045.41   414.1 1052.45
   424.1 1056.49     444 1058.78     454 1061.66   473.9 1071.88   483.4 1075.25
   492.8 1076.75   540.3 1104.14   549.8 1110.43   587.7 1138.37   597.2 1141.59
#Mann= 3 , 0 , 0
     9.8      .1       0  371.53    .045       0  397.95      .1       0
Bank Sta=371.53,397.95
XS Rating Curve= 0 ,0
Exp/Cntr=0.3,0.1

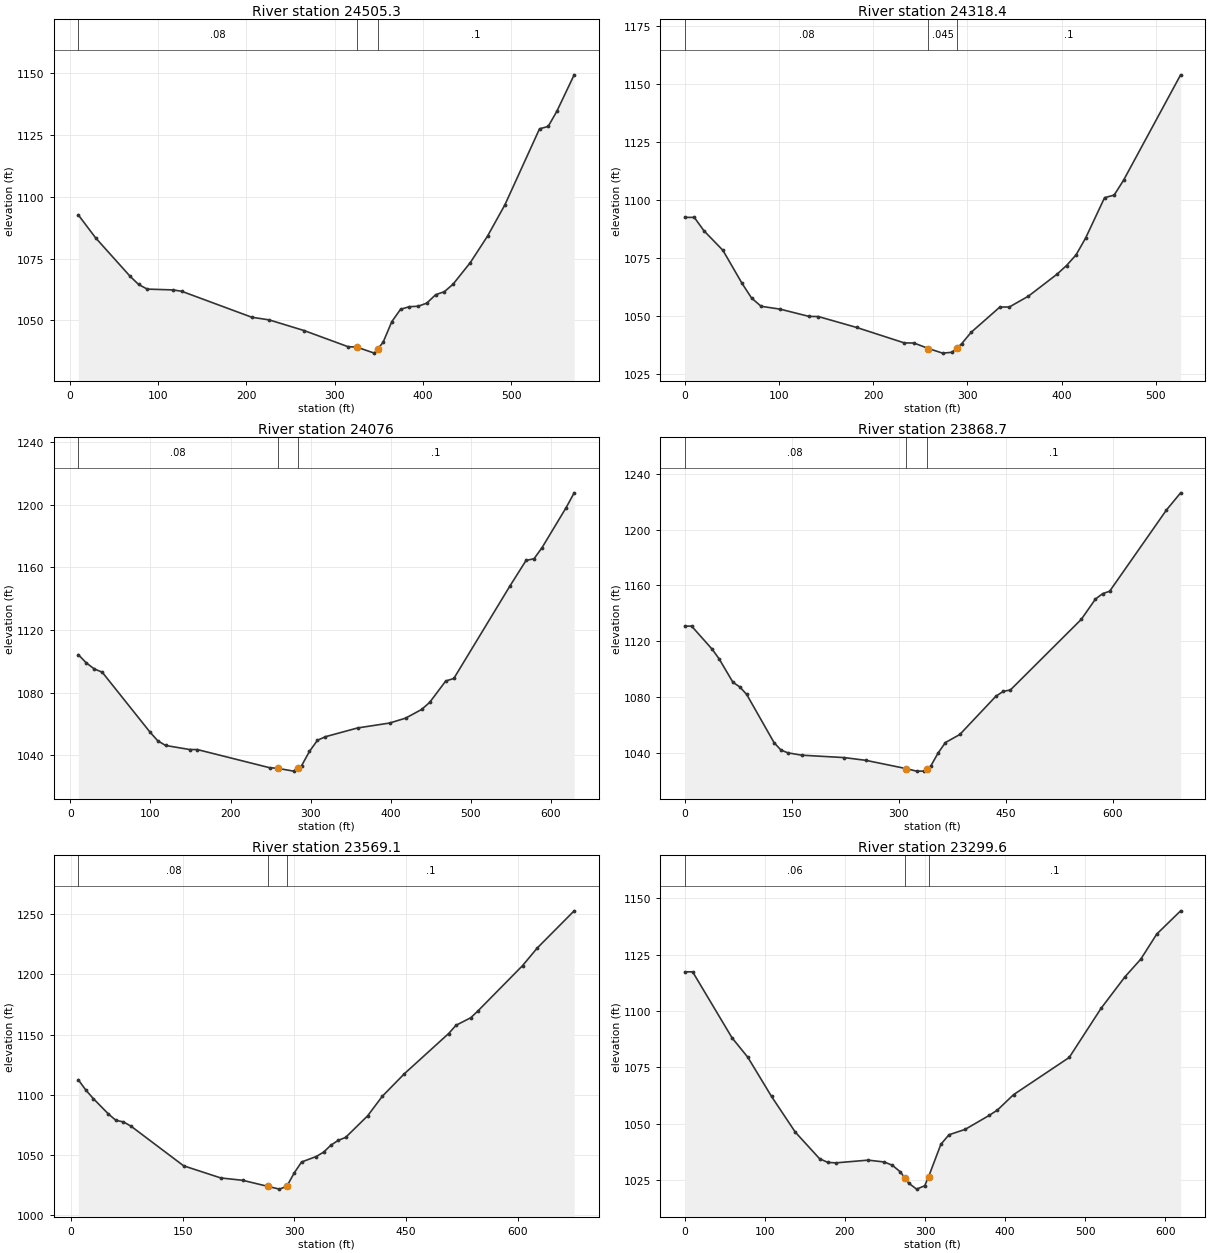
Type RM Length L Ch R = 1 ,24505.3 ,186.9,186.9,186.9
XS GIS Cut Line= 4
       1696212.4      216625.795     1696160.062      216499.677
     1696133.532      216213.371     1696092.896      216072.211
#Sta/Elev= 30
     9.8 1092.64    29.3 1083.41    68.3 1067.89      78 1064.56    87.8 1062.68
     117 1062.35   126.8  1061.8     206 1051.33   225.8 1050.24   265.4 1045.93
     315 1039.43   324.9 1039.26   344.8 1036.82  348.75 1038.56   354.7 1041.15
   364.6 1049.53   374.5 1054.52   384.4 1055.58   394.3 1055.75   404.2 1057.01
   414.2 1060.41   424.1 1061.64   433.9 1064.65   453.5 1073.41     473 1084.12
   492.6 1096.72   531.8 1127.42   541.6 1128.39   551.4 1134.51     571 1149.23
#Mann= 3 , 0 , 0
     9.8     .08       0   324.9    .045       0  348.75      .1       0
Bank Sta=324.9,348.75
XS Rating Curve= 0 ,0
Exp/Cntr=0.3,0.1

Type RM Length L Ch R = 1 ,24318.4 ,243.6,242.4,241.2
XS GIS Cut Line= 4
     1696368.809      216571.316     1696339.142      216422.297
     1696318.139      216190.157     1696293.241      216051.122
#Sta/Elev= 30
       0 1092.46    10.1 1092.46    20.3 1086.71    40.5 1078.26    60.8 1064.03
    70.9 1057.74      81 1054.19   101.3 1052.95   131.7 1049.85   141.8 1049.77
   182.3 1045.09     233 1038.43   243.2 1038.39   258.6 1036.02   273.6 1034.03
   283.7 1034.39   288.6 1036.16   293.8 1038.05     304 1043.01   334.4 1053.86
   344.5 1053.89   364.8 1058.57   395.1    1068   405.2 1071.74   415.3 1076.31
   425.4 1083.53   445.6 1100.96   455.7 1102.04   465.7 1108.43   526.3 1153.82
#Mann= 3 , 0 , 0
       0     .08       0   258.6    .045       0   288.6      .1       0
Bank Sta=258.6,288.6
XS Rating Curve= 0 ,0
Exp/Cntr=0.3,0.1

Type RM Length L Ch R = 1 ,24076   ,215,207.3,199.6
XS GIS Cut Line= 4
     1696644.025      216497.625      1696579.44      216352.639
     1696548.218      216145.086     1696502.251      215888.559
#Sta/Elev= 30
     9.9 1104.34    19.8 1099.14    29.8 1095.25    39.7 1093.19    99.2 1055.06
   109.1 1049.37     119 1046.38   148.8 1043.81   158.7 1043.76   248.7 1032.21
   258.7 1031.82   278.7 1030.01  284.63 1032.12   288.7 1033.43   298.6 1042.62
   308.6 1049.72   318.6 1051.99   358.6 1057.56   398.7 1060.71   418.7 1063.84
   438.8 1069.41   448.8 1073.94   468.8 1087.54   478.9 1089.16     549 1148.21
   569.1 1164.49   579.1  1165.6   589.1 1172.69   619.2 1198.23   629.2 1207.66
#Mann= 3 , 0 , 0
     9.9     .08       0   258.7    .045       0  284.63      .1       0
Bank Sta=258.7,284.63
XS Rating Curve= 0 ,0
Exp/Cntr=0.3,0.1

Type RM Length L Ch R = 1 ,23868.7 ,304.2,299.6,295.1
XS GIS Cut Line= 4
     1696913.607      216455.326     1696831.009      216291.887
     1696692.173      216056.394     1696549.823      215864.836
#Sta/Elev= 30
       0 1130.78     9.6 1130.78    38.6 1114.08    48.2 1107.25    67.5 1090.53
    77.1 1087.19    86.7 1081.86   125.3 1047.16   134.9 1041.91   144.6 1039.94
   163.8 1038.27   223.6 1036.53     254 1034.56   309.9 1028.68   324.9 1026.83
     335 1026.84   339.9 1028.69   345.1 1030.66   355.2 1039.87   365.4 1047.32
   385.6 1053.09   436.2 1080.53   446.4 1083.97   456.5 1085.01   555.9 1135.62
   575.8  1150.2   585.8 1154.04   595.7  1155.8   675.3 1214.01   695.2 1226.33
#Mann= 3 , 0 , 0
       0     .08       0   309.9    .045       0   339.9      .1       0
Bank Sta=309.9,339.9
XS Rating Curve= 0 ,0
Exp/Cntr=0.3,0.1

Type RM Length L Ch R = 1 ,23569.1 ,268.8,269.4,270.1
XS GIS Cut Line= 4
      1697203.58      216260.254     1697105.165      216119.661
     1696915.364      215919.316     1696736.108      215778.723
#Sta/Elev= 30
    10.1 1112.53    20.2 1103.96    30.3 1096.89    50.5 1084.13    60.6 1078.86
    70.7 1077.58    80.8 1074.04   151.4 1041.16   201.2  1031.1   230.8 1029.12
     265 1024.01     280 1021.82   289.9 1024.24   299.7 1035.16   309.6 1044.31
   329.3 1048.88   339.2 1052.49     349 1058.28   358.9 1062.33   368.7 1064.69
   398.3 1082.65     418 1098.87   447.6 1117.56     507 1150.91   516.9 1157.76
   536.7 1164.02   546.6 1169.85   606.1 1207.21   625.9 1221.88   675.4  1252.7
#Mann= 3 , 0 , 0
    10.1     .08       0     265    .045       0   289.9      .1       0
Bank Sta=265,289.9
XS Rating Curve= 0 ,0
Exp/Cntr=0.3,0.1

Type RM Length L Ch R = 1 ,23299.6 ,248,252.8,257.7
XS GIS Cut Line= 4
     1697409.197      216079.241     1697331.871      215977.311
     1697150.857      215773.451       1696959.3      215668.006
#Sta/Elev= 30
       0 1117.33     9.8 1117.33      59 1088.13    78.7 1079.52   108.3 1062.19
     138 1046.39   168.3 1034.64   178.4 1033.02   188.5 1032.79   228.9    1034
   249.1 1033.18   259.2 1031.73   269.3 1028.77   274.5 1026.25   279.4 1023.87
   289.5 1021.17   299.6 1022.65   304.5  1026.7   319.8 1041.01   329.9 1045.22
   350.1 1047.61   380.4 1053.85   390.5 1056.19   410.5 1062.96   480.1 1079.45
   519.8 1101.16   549.7 1115.13   569.5 1122.97   589.4 1134.05   619.2 1144.33
#Mann= 3 , 0 , 0
       0     .06       0   274.5    .045       0   304.5      .1       0
Bank Sta=274.5,304.5
XS Rating Curve= 0 ,0
Exp/Cntr=0.3,0.1

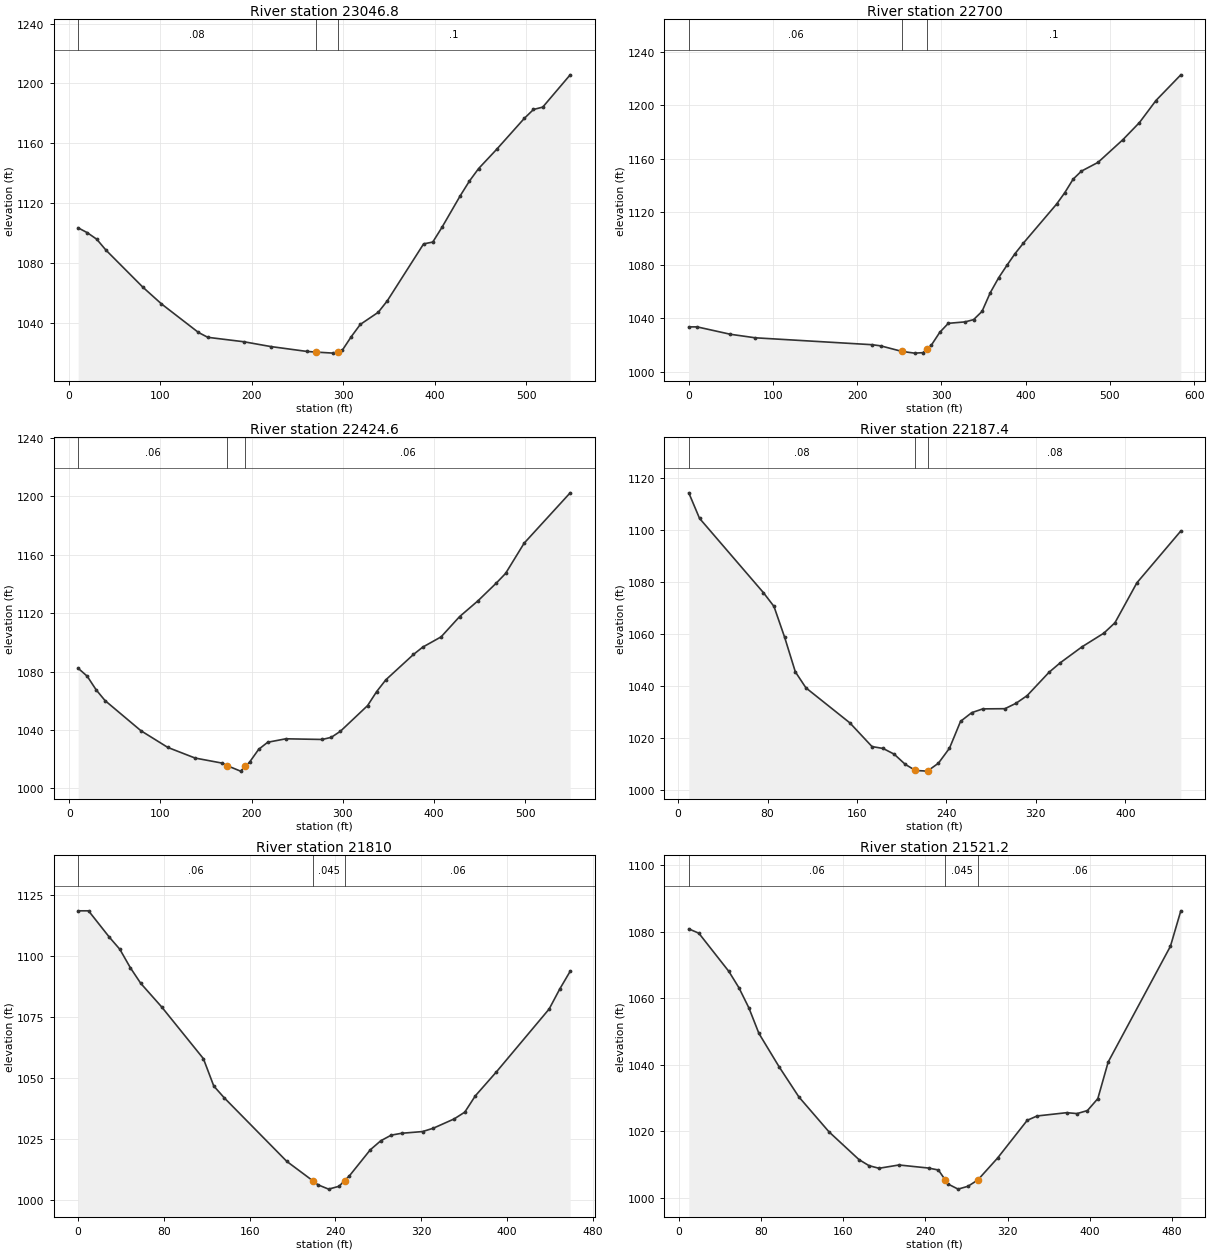
Type RM Length L Ch R = 1 ,23046.8 ,352.4,346.8,341.1
XS GIS Cut Line= 4
     1697566.786      215948.858     1697477.246      215813.995
     1697386.601      215640.442     1697322.486      215461.362
#Sta/Elev= 30
    10.1 1103.42    20.2 1100.14    30.4 1095.82    40.5 1088.53    80.9 1063.71
   101.2 1052.55   141.6 1033.47   151.8 1030.22   191.3 1027.25   220.6 1024.05
   259.8 1020.81   269.6 1020.36   289.2 1019.65  294.28  1020.6   298.9 1021.65
   308.7 1030.72   318.5 1038.84   338.1 1046.95   347.9 1054.52   387.7 1092.69
   397.7  1093.9   407.7 1103.69   427.8 1124.93   437.8 1134.72   447.8 1143.04
   467.8 1156.08   497.8 1176.63   507.8 1182.55   517.9 1184.13   547.9 1205.72
#Mann= 3 , 0 , 0
    10.1     .08       0   269.6    .045       0  294.28      .1       0
Bank Sta=269.6,294.28
XS Rating Curve= 0 ,0
Exp/Cntr=0.3,0.1

Type RM Length L Ch R = 1 ,22700   ,288.3,275.4,262.5
XS GIS Cut Line= 4
     1697915.332      215726.001     1697792.313      215611.769
     1697667.537      215481.721     1697467.192      215356.944
#Sta/Elev= 30
       0 1033.71     9.9 1033.71    49.4 1028.16      79 1025.51   217.9 1020.32
     228 1019.45     253 1015.29     268 1014.01     278 1014.35     283  1017.2
     288 1020.04     298 1029.67   308.1 1036.38   328.1 1037.46   338.1 1039.15
   348.1 1045.31   357.9 1059.36   367.8  1070.5   377.6 1079.85   387.4 1088.76
   397.3 1096.63   436.6 1125.83   446.4 1134.46   456.3 1144.59   466.1 1150.59
   485.8 1157.15   515.3 1174.18     535 1187.04   554.6  1203.6   584.1 1222.87
#Mann= 3 , 0 , 0
       0     .06       0     253    .045       0     283      .1       0
Bank Sta=253,283
XS Rating Curve= 0 ,0
Exp/Cntr=0.3,0.1

Type RM Length L Ch R = 1 ,22424.6 ,239.5,237.2,235
XS GIS Cut Line= 4
     1698054.167      215341.128     1697946.965      215327.068
     1697711.472      215286.648     1697509.369      215290.163
#Sta/Elev= 30
     9.8 1082.29    19.7 1076.87    29.5 1067.55    39.3 1060.15    78.6 1039.52
   108.1 1028.07     138  1020.8   167.9  1017.3   172.8 1015.69   187.8 1011.84
  193.12 1015.08   197.7 1017.97   207.7 1026.77   217.6 1031.61   237.5 1033.98
   277.4 1033.52   287.3 1034.98   297.3 1039.13   327.1 1056.71   337.1 1066.35
   347.1 1074.36   377.4 1091.73   387.5 1096.73   407.7 1103.79   427.9 1117.61
   448.1 1128.47   468.3 1140.67   478.4 1147.23   498.7 1167.92   549.2 1202.42
#Mann= 3 , 0 , 0
     9.8     .06       0   172.8    .045       0  193.12     .06       0
Bank Sta=172.8,193.12
XS Rating Curve= 0 ,0
Exp/Cntr=0.3,0.1

Type RM Length L Ch R = 1 ,22187.4 ,372.9,377.4,382
XS GIS Cut Line= 4
     1698101.815      215081.093     1697977.982      215082.894
     1697790.059       215071.84     1697654.115      215051.247
#Sta/Elev= 30
     9.5 1114.13    19.1 1104.34    76.2 1075.82    85.7  1070.5    95.3 1058.57
   104.8 1045.38   114.3 1039.21   153.6 1025.76   173.4 1016.66   183.3 1015.94
   193.2 1013.75   203.1 1009.84  212.25 1007.49   222.9 1007.23   223.5  1007.4
   232.8 1010.28   242.7 1016.04   252.6 1026.36   262.6 1029.69   272.5 1031.14
   292.3 1031.21   302.2 1033.29   312.1 1036.22   331.7 1045.18   341.6 1048.79
   361.2 1054.97   380.8 1060.24   390.7 1064.23   410.3 1079.56   449.6 1099.47
#Mann= 3 , 0 , 0
     9.5     .08       0  212.25    .045       0   223.5     .08       0
Bank Sta=212.25,223.5
XS Rating Curve= 0 ,0
Exp/Cntr=0.3,0.1

Type RM Length L Ch R = 1 ,21810   ,292.4,288.7,285
XS GIS Cut Line= 4
     1698173.671      214775.241     1698024.291      214731.306
     1697874.911      214687.371     1697732.561      214648.707
#Sta/Elev= 30
       0 1118.53     9.7 1118.53    29.2 1107.67    38.9 1102.75    48.7 1095.18
    58.4 1088.78    77.9 1079.11   116.8 1057.91   126.5 1046.67   136.2 1041.86
   194.6 1015.76   218.6  1007.9   223.8 1006.13   233.6 1004.38   243.3 1005.54
   248.6 1007.89     253 1009.83   272.5 1020.52   282.2  1024.2     292 1026.52
   301.7 1027.29   321.2 1027.99   331.1 1029.34   350.7 1033.18   360.6 1035.96
   370.4 1042.62   390.1 1052.47   439.3 1078.27   449.1  1086.4   458.9 1093.74
#Mann= 3 , 0 , 0
       0     .06       0   218.6    .045       0   248.6     .06       0
Bank Sta=218.6,248.6
XS Rating Curve= 0 ,0
Exp/Cntr=0.3,0.1

Type RM Length L Ch R = 1 ,21521.2 ,356.5,343.4,330.2
XS GIS Cut Line= 4
     1698245.725      214557.322     1698082.093      214434.415
     1697910.059      214416.729     1697799.342      214425.516
#Sta/Elev= 30
     9.7 1080.93    19.5 1079.63    48.7 1068.15    58.5 1063.24    68.2 1057.18
      78 1049.48    97.5 1039.53   116.9 1030.39   146.2  1019.9   175.4 1011.55
   185.2 1009.72   194.9 1008.94   214.3 1009.93   243.1 1009.01   252.7 1008.42
   259.4 1005.44   262.3 1004.17   271.9 1002.67   281.5 1003.53   291.1 1005.43
   310.3 1012.01   339.2 1023.37   348.8 1024.67   377.6 1025.66   387.7 1025.39
   397.8  1026.3   407.9 1029.88     418  1040.9   478.6 1075.71   488.7 1086.36
#Mann= 3 , 0 , 0
     9.7     .06       0   259.4    .045       0   291.1     .06       0
Bank Sta=259.4,291.1
XS Rating Curve= 0 ,0
Exp/Cntr=0.3,0.1

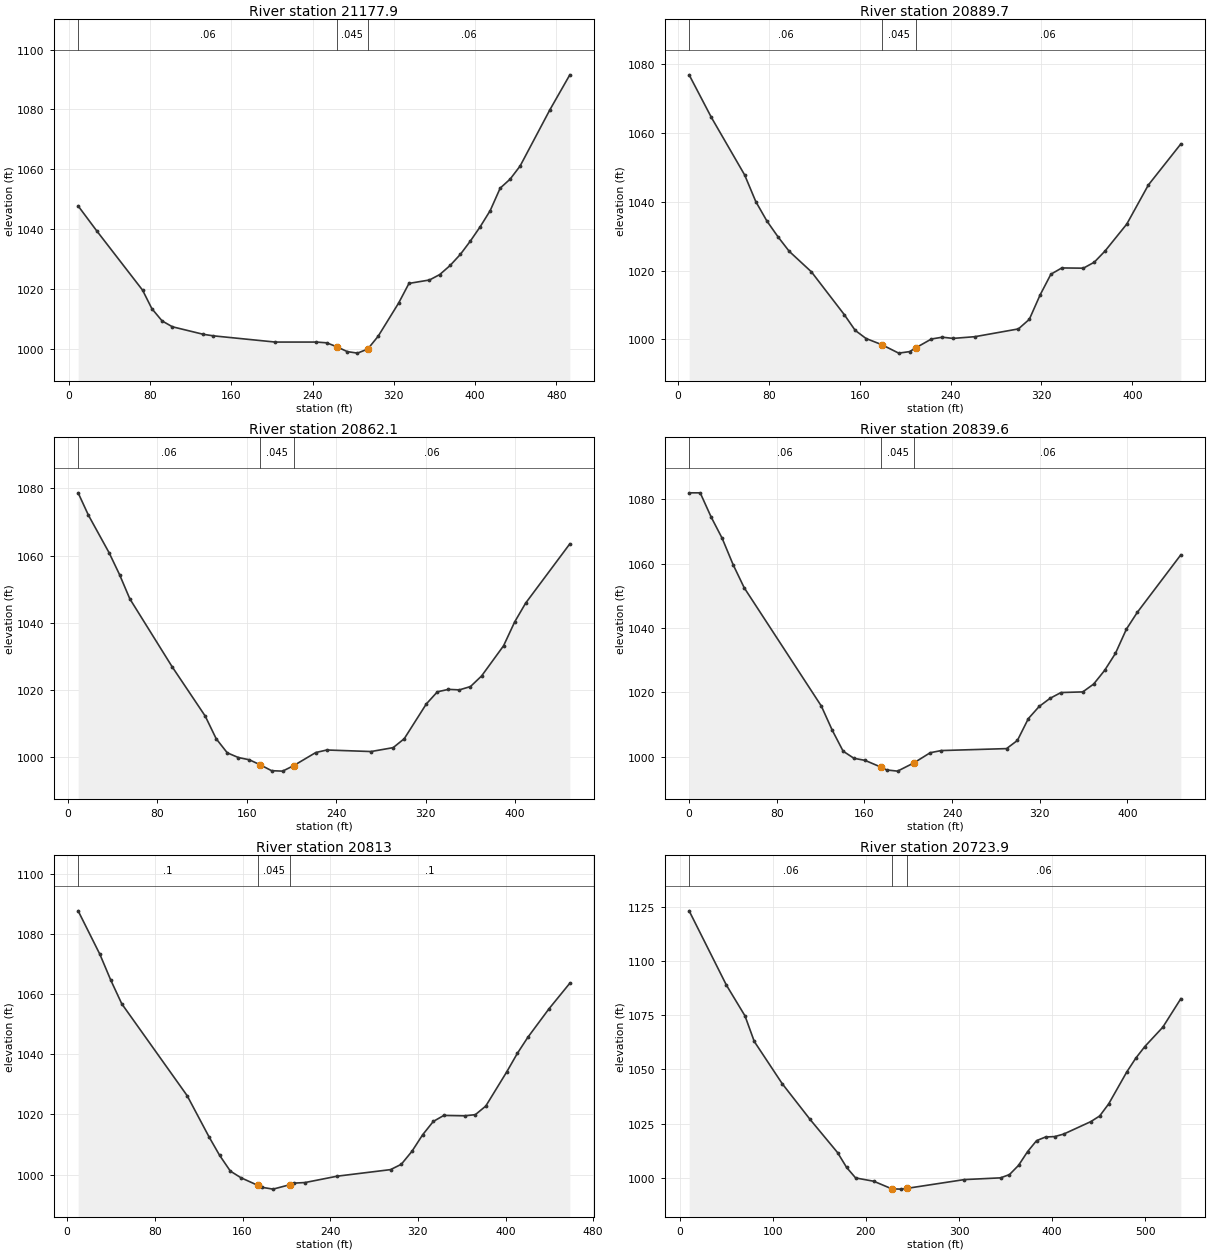
Type RM Length L Ch R = 1 ,21177.9 ,287,288.2,289.3
XS GIS Cut Line= 4
     1698138.044      213966.047     1698064.711       214001.98
     1697806.372      214161.905     1697739.991      214246.793
#Sta/Elev= 30
     9.1 1047.85    27.2 1039.63    72.6 1019.74    81.7 1013.59    91.8  1009.5
   101.9 1007.55   132.3 1005.04   142.4 1004.52   203.2 1002.45   243.7 1002.45
   253.8  1002.2     264 1000.87   274.1  999.27   284.2  998.76   294.3 1000.12
   304.5 1004.37   324.7 1015.45   334.9 1022.01   355.1 1023.15   365.2 1024.96
   375.4 1027.98   385.5 1031.69   395.3 1036.11   405.1 1040.94   414.9  1046.3
   424.7 1053.77   434.5 1056.78   444.3 1061.13   473.7 1079.93   493.3 1091.56
#Mann= 3 , 0 , 0
     9.1     .06       0     264    .045       0   294.3     .06       0
Bank Sta=264,294.3
XS Rating Curve= 0 ,0
Exp/Cntr=0.3,0.1

Type RM Length L Ch R = 1 ,20889.7 ,28.2,27.6,27
XS GIS Cut Line= 4
     1697943.172      213722.093     1697848.658      213807.281
     1697696.937      213889.359     1697579.416      213970.815
#Sta/Elev= 30
     9.8 1076.99    29.4 1064.58    58.7 1047.82    68.5 1040.07    78.3  1034.4
    88.1 1029.79    97.9  1025.6   117.5  1019.6   146.4 1007.15     156 1002.57
   165.6 1000.19   179.3  998.42   194.3  995.94   203.9  996.38   209.3  997.47
   223.1 1000.05   232.7 1000.58   242.2 1000.23   261.4 1000.73   299.7 1002.99
   309.3 1005.78   318.8 1012.88   328.3 1018.92   337.9 1020.75   356.9 1020.68
   366.5 1022.42     376 1025.69   395.1 1033.52   414.1  1044.9   442.7 1056.86
#Mann= 3 , 0 , 0
     9.8     .06       0   179.3    .045       0   209.3     .06       0
#XS Ineff= 2 , 0
       0                     234       0
Permanent Ineff=
       F       F
Bank Sta=179.3,209.3
XS Rating Curve= 0 ,0
Exp/Cntr=0.3,0.1

Type RM Length L Ch R = 1 ,20862.1 ,22.7,22.6,22.4
XS GIS Cut Line= 4
     1697933.745      213714.297     1697866.124      213762.972
     1697678.283       213872.57     1697559.417      213960.775
#Sta/Elev= 30
     9.3  1078.7    18.5 1072.05      37 1060.86    46.3 1054.38    55.5 1047.16
    93.2 1027.01   122.9 1012.26   132.7 1005.52   142.6 1001.33   152.5  999.93
   162.4  999.25   172.3  997.72   182.2  996.01   192.1  995.88   201.9   997.5
   221.7 1001.41   231.6 1002.17   271.1 1001.71   290.9 1002.87   300.8 1005.53
   320.5 1015.86   330.4 1019.48   340.3 1020.21   350.1 1020.06     360 1021.05
   369.9 1024.19   389.6  1033.2   399.5 1040.28   409.3 1045.88   448.8 1063.52
#Mann= 3 , 0 , 0
     9.3     .06       0   172.3    .045       0   201.9     .06       0
Bank Sta=172.3,201.9
XS Rating Curve= 0 ,0
Exp/Cntr=0.3,0.1

Type RM Length L Ch R = 1 ,20839.6 ,27.2,26.5,25.8
XS GIS Cut Line= 4
     1697930.114       213707.17     1697822.542      213761.889
     1697719.944      213822.826     1697558.896      213955.892
#Sta/Elev= 30
       0 1082.03    10.1 1082.03    20.1 1074.51    30.2 1067.87    40.2 1059.67
    50.3 1052.51   120.7 1015.75   130.6 1008.28   140.6 1001.72   150.5   999.5
   160.5  998.88   175.3  996.74   180.4  995.88   190.3  995.52   205.3   998.1
   220.1 1001.24   230.1 1001.91   289.8 1002.52   299.7 1005.06   309.7 1011.85
   319.6 1015.63   329.6 1018.17   339.5 1019.95   359.4 1020.15   369.3 1022.58
   379.3 1026.82   389.2 1032.12   399.2 1039.65   409.1 1044.85   448.9 1062.76
#Mann= 3 , 0 , 0
       0     .06       0   175.3    .045       0   205.3     .06       0
Bank Sta=175.3,205.3
XS Rating Curve= 0 ,0
Exp/Cntr=0.3,0.1

Type RM Length L Ch R = 1 ,20813   ,95,89.1,83.3
XS GIS Cut Line= 4
     1697926.383      213698.465     1697803.888      213740.126
     1697631.648      213850.807     1697552.678      213947.187
#Sta/Elev= 30
      10 1087.65    29.9 1073.17    39.8 1064.62    49.8 1056.78   109.5 1026.25
   129.4 1012.61   139.1 1006.44   148.9  1001.2   158.6  998.99  174.22  996.42
   178.1  995.79   187.9  995.21   202.9  996.65   207.4  997.21   217.1   997.4
   246.4  999.51   295.1 1001.69   304.9 1003.46   314.6 1007.76   324.4 1013.27
   334.1 1017.69   343.7 1019.69   362.9 1019.56   372.5 1019.95     382  1022.8
   401.2  1034.2   410.8  1040.3   420.4 1045.65   439.6 1055.07   458.7 1063.61
#Mann= 3 , 0 , 0
      10      .1       0  174.22    .045       0   202.9      .1       0
#XS Ineff= 2 , 0
       0                     235       0
Permanent Ineff=
       F       F
Bank Sta=174.22,202.9
XS Rating Curve= 0 ,0
Exp/Cntr=0.3,0.1

Type RM Length L Ch R = 1 ,20723.9 ,49.6,47.2,44.8
XS GIS Cut Line= 4
      1697853.01      213533.064     1697751.034      213643.124
     1697624.808      213791.114      1697525.94      213957.758
#Sta/Elev= 30
      10 1123.25      50 1088.98      70 1074.75      80 1062.92     110 1043.43
     140 1026.89   169.5 1011.59   179.2 1004.74   188.9  999.89   208.4  998.36
   227.8  994.85   237.6  994.72   244.4   995.1   305.6  999.12   344.6  999.93
   354.2 1001.44   363.9 1005.68   373.6 1012.02   383.3 1017.11     393 1018.81
   402.7 1018.98   412.4 1020.14   441.4 1025.86   451.1  1028.5   460.8  1034.1
   480.2 1048.82   489.9  1055.2   499.6 1060.57   518.9 1069.49   538.3 1082.67
#Mann= 3 , 0 , 0
      10     .06       0   227.8    .045       0   244.4     .06       0
#XS Ineff= 2 , 0
       0                     327       0
Permanent Ineff=
       F       F
Bank Sta=227.8,244.4
XS Rating Curve= 0 ,0
Exp/Cntr=0.3,0.1

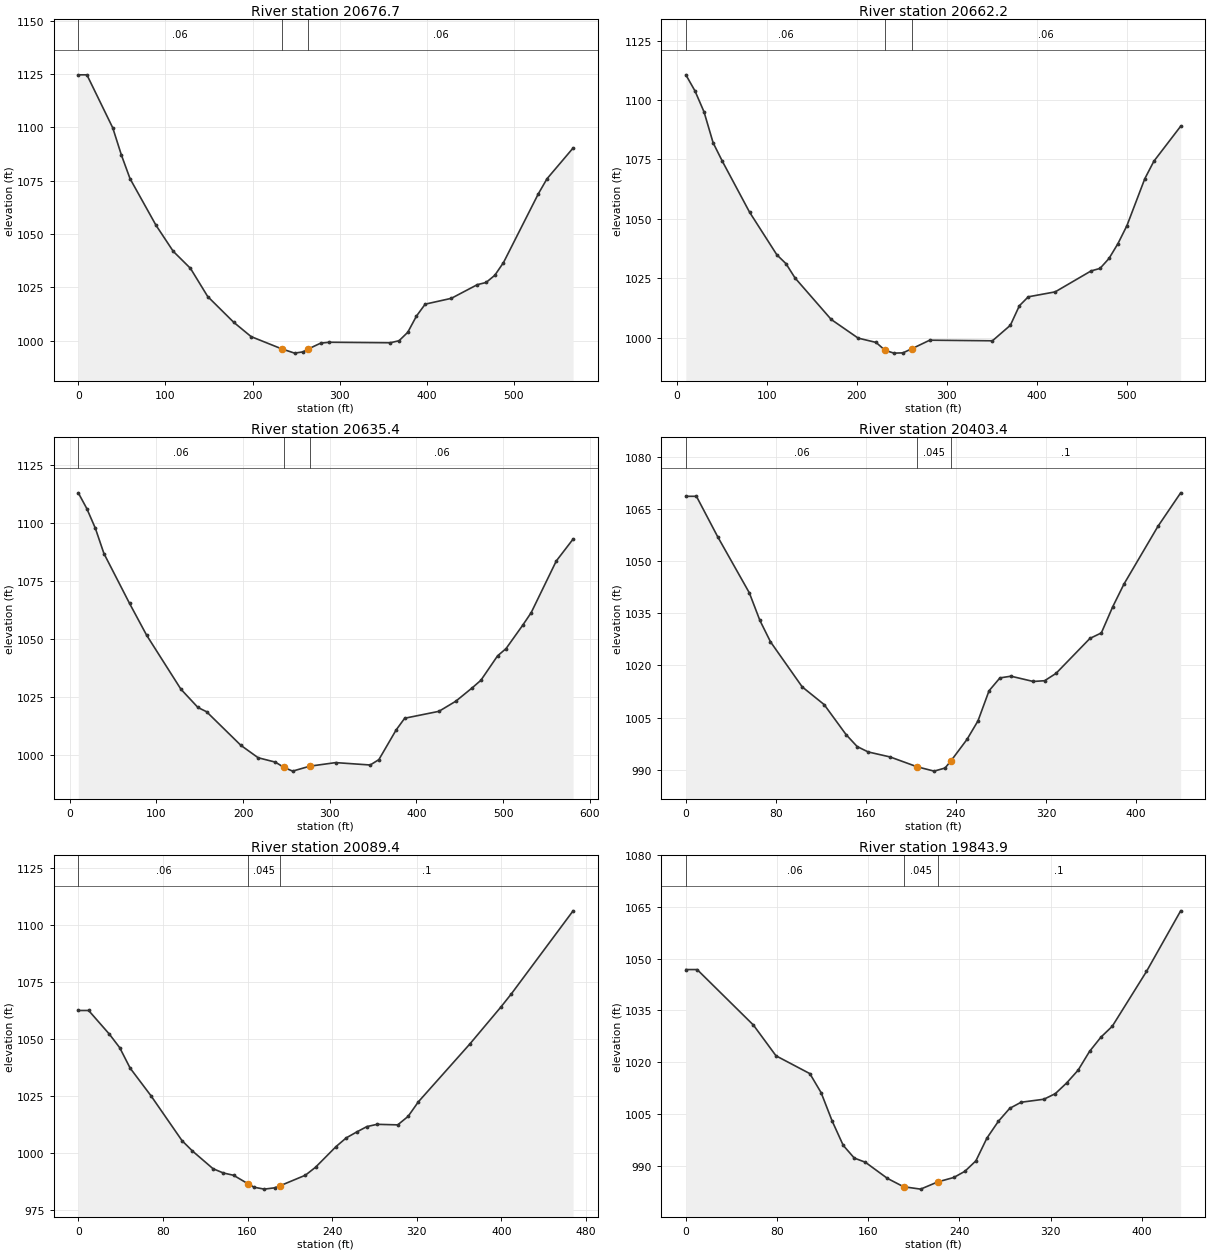
Type RM Length L Ch R = 1 ,20676.7 ,14.9,14.5,14
XS GIS Cut Line= 4
     1697843.061      213511.301     1697706.264      213609.546
     1697628.538      213725.824     1697511.639      213957.758
#Sta/Elev= 30
       0 1124.57     9.9 1124.57    39.6 1099.69    49.5 1086.97    59.4 1075.91
    89.2 1054.07     109 1041.85   128.8 1033.85   148.6 1020.64   178.4  1008.6
   198.4 1001.87   233.3  996.16   248.3  994.13   258.3  994.74   263.3  995.95
   278.3  998.82   288.3  999.23   358.2  998.99   368.2  999.94   378.2 1003.89
   388.2  1011.5   398.2 1017.08   428.2 1019.81   458.1 1026.23   468.1 1027.24
   478.1  1030.6   488.1 1036.58   528.1 1068.81     538 1075.83     568 1090.27
#Mann= 3 , 0 , 0
       0     .06       0   233.3    .045       0   263.3     .06       0
Bank Sta=233.3,263.3
XS Rating Curve= 0 ,0
Exp/Cntr=0.3,0.1

Type RM Length L Ch R = 1 ,20662.2 ,26.6,26.8,27.1
XS GIS Cut Line= 4
     1697819.433      213495.134      1697694.45      213597.732
     1697619.833      213715.253      1697508.53      213949.052
#Sta/Elev= 30
    10.1 1110.58    20.2 1103.84    30.3 1094.99    40.4    1082    50.5 1074.35
    80.9 1052.83   111.2 1034.92   121.3 1031.22   131.4 1025.19   171.6 1007.74
   201.5  999.91   221.4   998.1   231.3  994.81   241.2   993.6   251.2  993.71
   261.1  995.43     281  999.04   350.7  998.79   370.6 1005.31   380.6 1013.51
   390.5 1017.27   420.4 1019.35   460.3 1028.16   470.2 1029.21   480.2  1033.4
   490.1 1039.62   500.1  1047.2     520 1066.96     530 1074.25   559.8 1088.97
#Mann= 3 , 0 , 0
    10.1     .06       0   231.3    .045       0   261.1     .06       0
Bank Sta=231.3,261.1
XS Rating Curve= 0 ,0
Exp/Cntr=0.3,0.1

Type RM Length L Ch R = 1 ,20635.4 ,228.9,231.9,234.9
XS GIS Cut Line= 4
     1697819.433      213483.942     1697672.687      213584.052
     1697542.729      213784.274      1697494.85      213941.591
#Sta/Elev= 30
     9.9 1112.98    19.7 1106.22    29.6 1097.71    39.5 1086.83    69.1 1065.31
    88.8 1051.62   128.3  1028.4     148 1020.51   157.9 1018.69   197.5 1004.21
   217.4  998.87   237.3  996.97   247.3  994.69   257.2   993.1   277.1  995.24
   306.9  996.77   346.7  995.74   356.7  998.05   376.6 1010.82   386.5 1015.88
     426 1018.86   445.4  1023.2   464.7 1029.07   474.4 1032.23   493.7 1042.78
   503.4 1045.86   522.7 1055.97   532.4 1061.34   561.4 1083.62   580.8 1093.06
#Mann= 3 , 0 , 0
     9.9     .06       0   247.3    .045       0   277.1     .06       0
#XS Ineff= 2 , 0
       0                     295       0
Permanent Ineff=
       F       F
Bank Sta=247.3,277.1
XS Rating Curve= 0 ,0
Exp/Cntr=0.3,0.1

Type RM Length L Ch R = 1 ,20403.4 ,310.4,314.1,317.7
XS GIS Cut Line= 4
     1697613.457      213384.783     1697526.944      213441.366
     1697395.138      213585.474     1697324.802      213707.707
#Sta/Elev= 30
       0 1068.67     9.4 1068.67    28.2 1057.08    56.4 1040.89    65.8 1032.94
    75.2  1026.8   103.4 1013.82   122.9 1008.73   142.4 1000.08   152.2  996.66
     162   995.1   181.5  993.66   205.6  990.82   220.6  989.58   230.3  990.47
   235.6  992.55   249.8   998.7   259.6 1004.05   269.4  1012.7   279.1 1016.41
   288.9  1016.9   308.7 1015.38   318.8  1015.6   328.9  1017.7   359.1 1027.78
   369.2 1029.35   379.3 1036.87   389.3 1043.41   419.5 1060.03   439.7 1069.67
#Mann= 3 , 0 , 0
       0     .06       0   205.6    .045       0   235.6      .1       0
Bank Sta=205.6,235.6
XS Rating Curve= 0 ,0
Exp/Cntr=0.3,0.1

Type RM Length L Ch R = 1 ,20089.4 ,248.4,245.5,242.5
XS GIS Cut Line= 4
     1697423.657      213164.667      1697326.12       213230.57
      1697196.55      213332.406     1697061.229       213458.94
#Sta/Elev= 30
       0  1062.4     9.8  1062.4    29.4 1052.03    39.2 1046.09      49 1037.18
    68.7 1025.07    98.1 1005.39   107.9 1000.88   127.4  993.11   137.1  991.25
   146.8  990.23   160.9  986.39   166.2  984.99   175.9  984.17   185.6  984.74
   190.9  985.67   214.7  990.26   224.3  993.75   243.7 1002.81   253.4 1006.63
   263.1 1009.16   272.8 1011.55   282.5 1012.55     302 1012.31   311.8 1016.02
   321.5 1022.39   370.3 1047.79   399.5  1063.9   409.3  1069.6   467.8 1106.04
#Mann= 3 , 0 , 0
       0     .06       0   160.9    .045       0   190.9      .1       0
Bank Sta=160.9,190.9
XS Rating Curve= 0 ,0
Exp/Cntr=0.3,0.1

Type RM Length L Ch R = 1 ,19843.9 ,197.2,204.2,211.3
XS GIS Cut Line= 4
     1697268.126      212944.551     1697178.498      213022.317
     1697079.643       213129.08     1696951.792      213241.114
#Sta/Elev= 30
       0 1046.85     9.9 1046.85    59.3 1030.74    79.1 1021.83   108.8 1016.66
   118.7 1011.13   128.4 1002.89   138.1  995.84   147.8  992.16   157.5  990.95
   176.9  986.26     191  983.85     206  983.15     221  985.24   235.1  986.53
   244.8  988.31   254.5  991.35   264.2  997.97   274.2 1002.81   284.2 1006.59
   294.2 1008.36   314.2 1009.23   324.2 1010.85   334.2 1013.97   344.2 1017.66
   354.2 1023.09   364.2 1027.23   374.2 1030.41   404.2  1046.3   434.2 1063.89
#Mann= 3 , 0 , 0
       0     .06       0     191    .045       0     221      .1       0
Bank Sta=191,221
XS Rating Curve= 0 ,0
Exp/Cntr=0.3,0.1

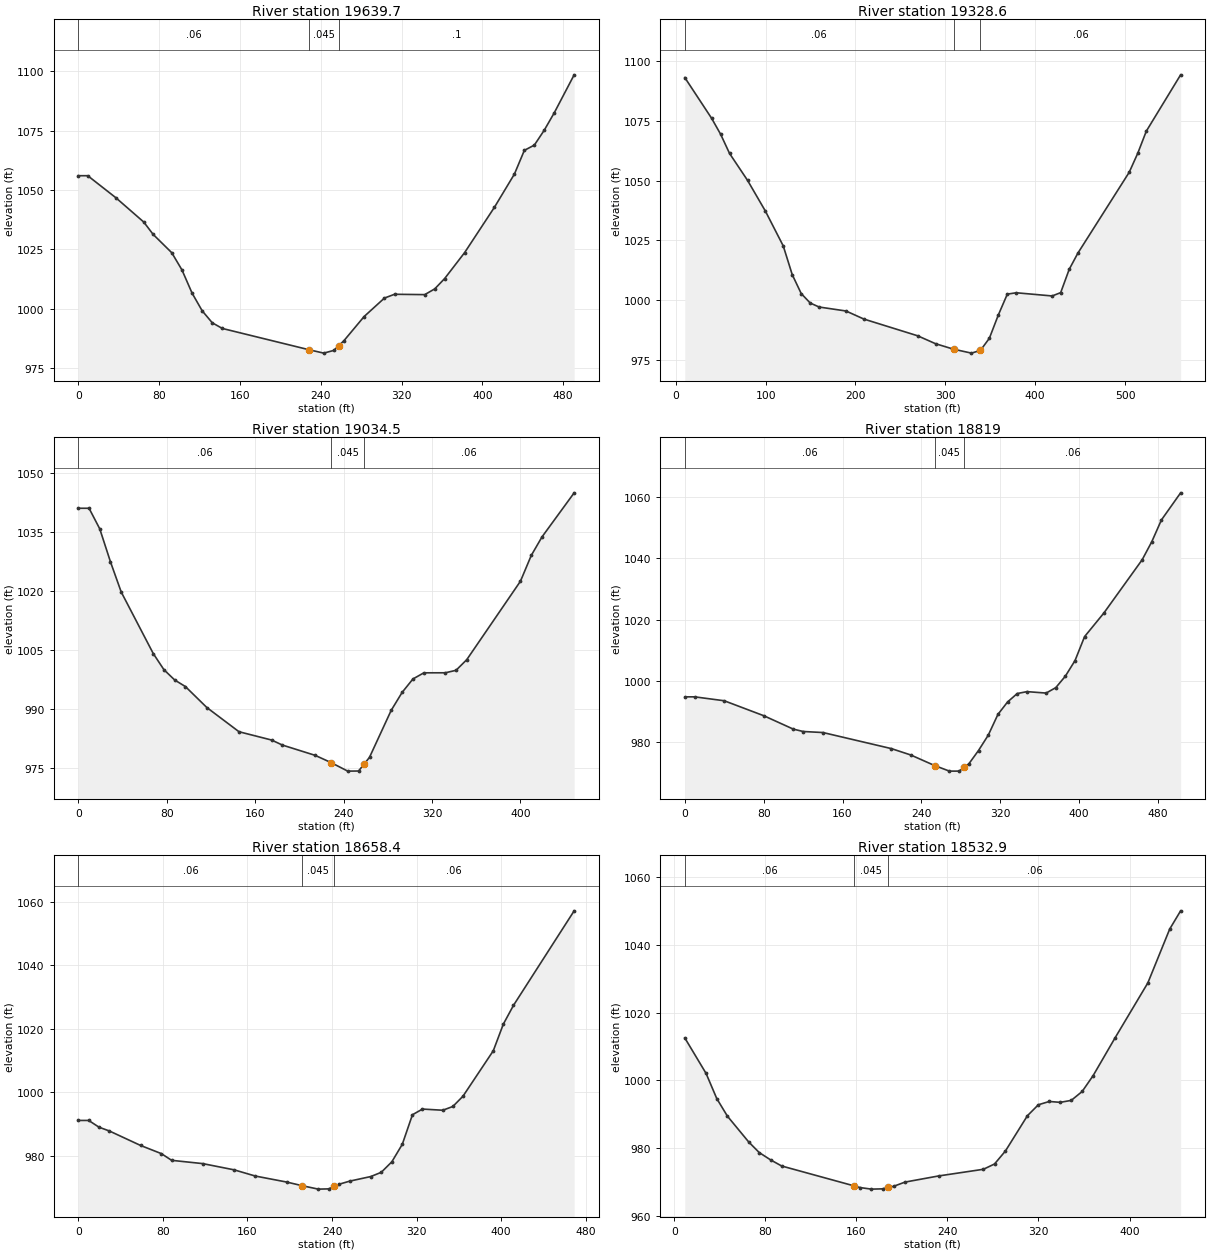
Type RM Length L Ch R = 1 ,19639.7 ,307.8,311,314.3
XS GIS Cut Line= 4
     1697191.678       212823.29     1697116.549       212877.33
     1696901.705      212985.411     1696821.304      213121.171
#Sta/Elev= 30
       0 1056.07     9.3 1056.07      37 1046.84    64.8 1036.53      74 1031.37
    92.5 1023.61   102.6 1016.35   112.6 1006.59   122.6  999.14   132.6  994.08
   142.6   991.7   227.9  982.78   242.9  981.31   252.9  982.46   257.9   984.5
   262.9  986.54   282.9  996.73     303 1004.51     313 1006.11   342.9 1005.96
   352.8 1008.38   362.6 1012.73   382.4 1023.68   411.9 1042.78   431.7 1056.79
   441.5 1066.75   451.4 1068.97   461.2 1075.25   471.1 1082.57   490.8 1098.58
#Mann= 3 , 0 , 0
       0     .06       0   227.9    .045       0   257.9      .1       0
Bank Sta=227.9,257.9
XS Rating Curve= 0 ,0
Exp/Cntr=0.3,0.1

Type RM Length L Ch R = 1 ,19328.6 ,291.5,294.1,296.7
XS GIS Cut Line= 4
     1697156.671      212581.297     1696973.445      212629.383
      1696754.57      212698.196     1696611.969      212708.974
#Sta/Elev= 30
      10 1093.02    39.9 1075.97    49.9 1069.33    59.8 1061.34    79.8 1050.11
    99.7 1037.25   119.6 1022.68   129.6 1010.69   139.6 1002.79   149.6  998.85
   159.5  997.18   189.4  995.52   209.4  992.14   269.2  985.16   289.2  981.84
   309.1  979.57   329.1  977.92   339.1  979.07     349  984.12     359  993.86
     369 1002.57     379 1003.13   418.9  1001.8   428.4 1003.19   437.9 1012.94
   447.5 1019.66   504.7 1053.48   514.2 1061.41   523.7 1070.63   561.9 1094.16
#Mann= 3 , 0 , 0
      10     .06       0   309.1    .045       0   339.1     .06       0
Bank Sta=309.1,339.1
XS Rating Curve= 0 ,0
Exp/Cntr=0.3,0.1

Type RM Length L Ch R = 1 ,19034.5 ,221.8,215.5,209.3
XS GIS Cut Line= 4
     1697041.419      212373.832     1696896.433      212363.287
     1696731.676      212392.285     1696597.234      212413.373
#Sta/Elev= 30
       0 1041.02     9.7 1041.02    19.4 1035.78    29.1 1027.39    38.8 1019.74
    67.8  1004.1    77.5  999.98    87.2  997.38    96.9  995.71   116.3  990.38
   145.4  984.23   174.9  982.12   184.7  980.84   214.3  978.23   228.8  976.38
   243.8  974.22   253.6  974.25   258.8  976.07   263.5  977.73   283.1  989.65
     293  994.22   302.8  997.64   312.7   999.2   332.1  999.21   341.8  999.84
   351.5 1002.54   400.1 1022.48   409.9 1029.04   419.6 1033.74   448.7 1044.94
#Mann= 3 , 0 , 0
       0     .06       0   228.8    .045       0   258.8     .06       0
Bank Sta=228.8,258.8
XS Rating Curve= 0 ,0
Exp/Cntr=0.3,0.1

Type RM Length L Ch R = 1 ,18819   ,152.6,160.5,168.4
XS GIS Cut Line= 4
     1696946.519       212008.73     1696823.979      212126.822
     1696667.569       212209.42     1696520.786      212261.797
#Sta/Elev= 30
       0  994.81      10  994.81      40  993.53    80.1  988.65   110.1  984.27
   120.1   983.5   140.2  983.16   209.5  977.92   229.1  975.85   253.4  972.39
   268.4  970.57   278.3  970.58   283.4  971.81   288.1  972.95   297.9   977.3
   307.8  982.31   317.6  989.08   327.4  993.15   337.2  995.89   347.1  996.51
   366.5  996.04   376.3  997.82     386 1001.56   395.8 1006.65   405.5 1014.47
     425 1022.14   463.9 1039.54   473.7 1045.46   483.4 1052.52   502.9 1061.38
#Mann= 3 , 0 , 0
       0     .06       0   253.4    .045       0   283.4     .06       0
Bank Sta=253.4,283.4
XS Rating Curve= 0 ,0
Exp/Cntr=0.3,0.1

Type RM Length L Ch R = 1 ,18658.4 ,123,125.5,128
XS GIS Cut Line= 4
     1696907.334      211965.195     1696800.107      212013.834
     1696612.184      212031.521     1696461.845      212093.425
#Sta/Elev= 30
       0   991.2     9.8   991.2    19.6  989.07    29.4  987.88    58.9  983.33
    78.5  980.77    88.3  978.65   117.7  977.62   147.5  975.65   167.4  973.71
   197.2  971.81     212  970.65     227  969.59     237  969.67     242  970.42
   246.9  971.15   256.8  972.11   276.7  973.55   286.6  974.88   296.6  978.18
   306.5  983.69   316.1  992.99   325.6  994.78   344.8  994.41   354.3  995.59
   363.9  998.82   392.6 1013.13   402.1 1021.51   411.7 1027.41   469.1 1057.15
#Mann= 3 , 0 , 0
       0     .06       0     212    .045       0     242     .06       0
Bank Sta=212,242
XS Rating Curve= 0 ,0
Exp/Cntr=0.3,0.1

Type RM Length L Ch R = 1 ,18532.9 ,51.8,48.6,45.5
XS GIS Cut Line= 4
     1696847.665      211856.329     1696788.352      211901.802
     1696581.747      211895.871     1696427.534      211950.241
#Sta/Elev= 30
     9.3 1012.55      28 1002.08    37.4  994.66    46.7   989.5    65.4  981.89
    74.7  978.75    84.6  976.61    94.4  974.79   158.2  968.91   163.3  968.43
   173.2  967.97     183  968.05   188.2  968.45   192.8   968.8   202.7  970.04
   232.2  971.85   271.6  973.82   281.4  975.38     291  979.22   310.3  989.61
   319.9  992.84   329.5  993.81   339.1  993.56   348.8  994.13   358.4  996.76
     368 1001.42   387.2 1012.51   416.1 1028.77   435.3 1044.64   444.9 1050.02
#Mann= 3 , 0 , 0
     9.3     .06       0   158.2    .045       0   188.2     .06       0
#XS Ineff= 2 , 0
       0     102             269       0
Permanent Ineff=
       F       F
Bank Sta=158.2,188.2
XS Rating Curve= 0 ,0
Exp/Cntr=0.3,0.1