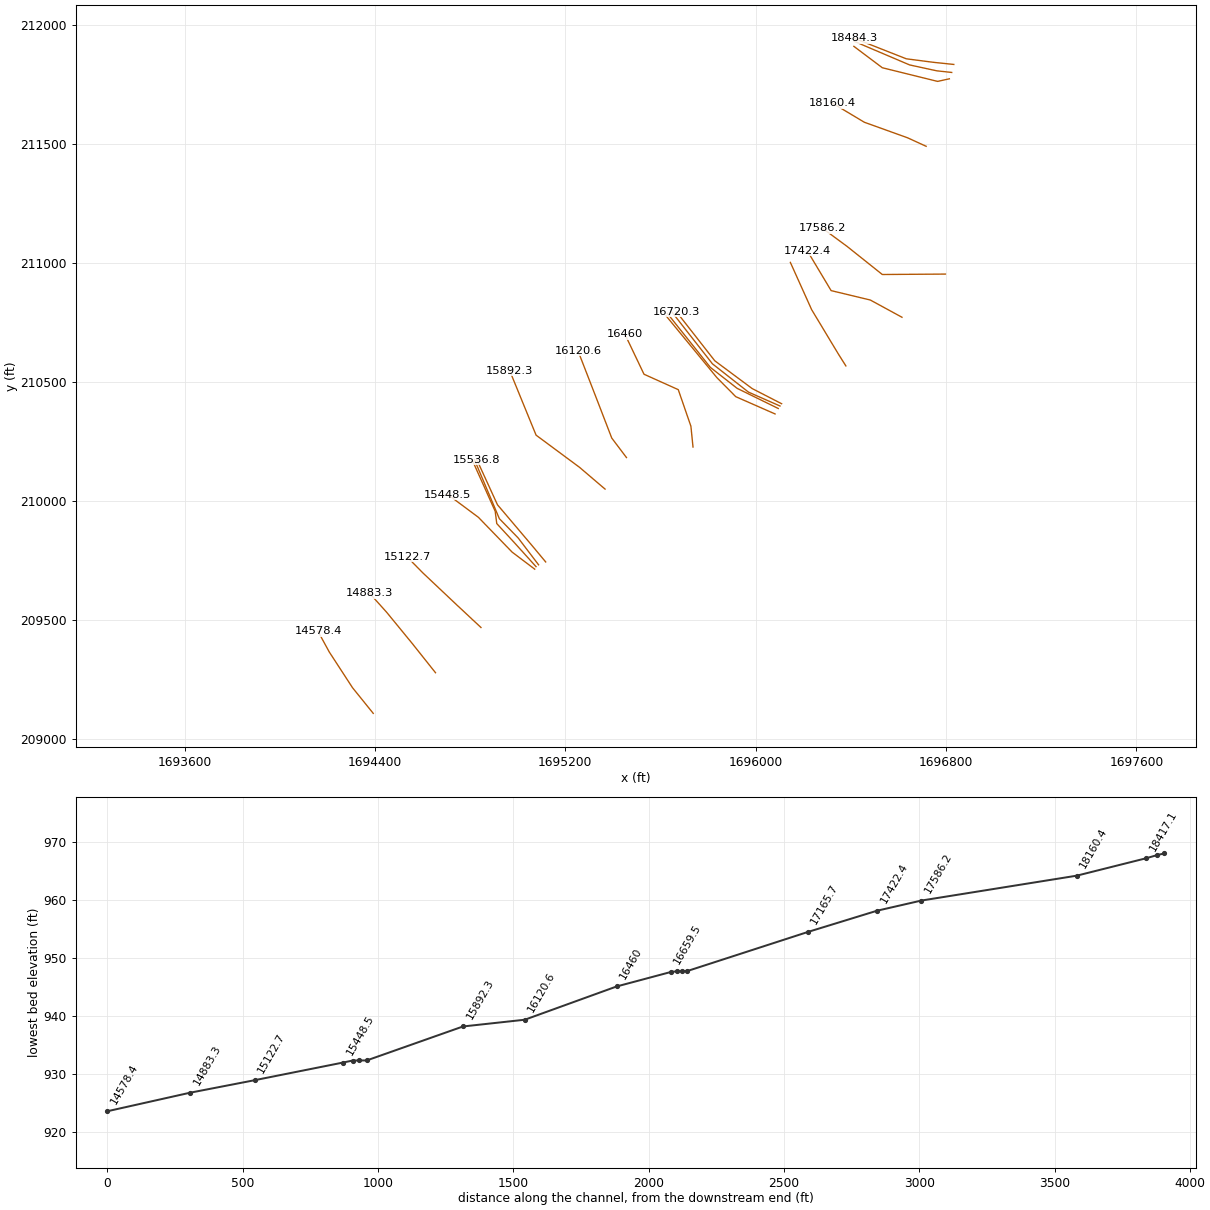
HEC-RAS study bncrk.prj: bncrk

--- bncrk.g01 (geometry) --- (continued)

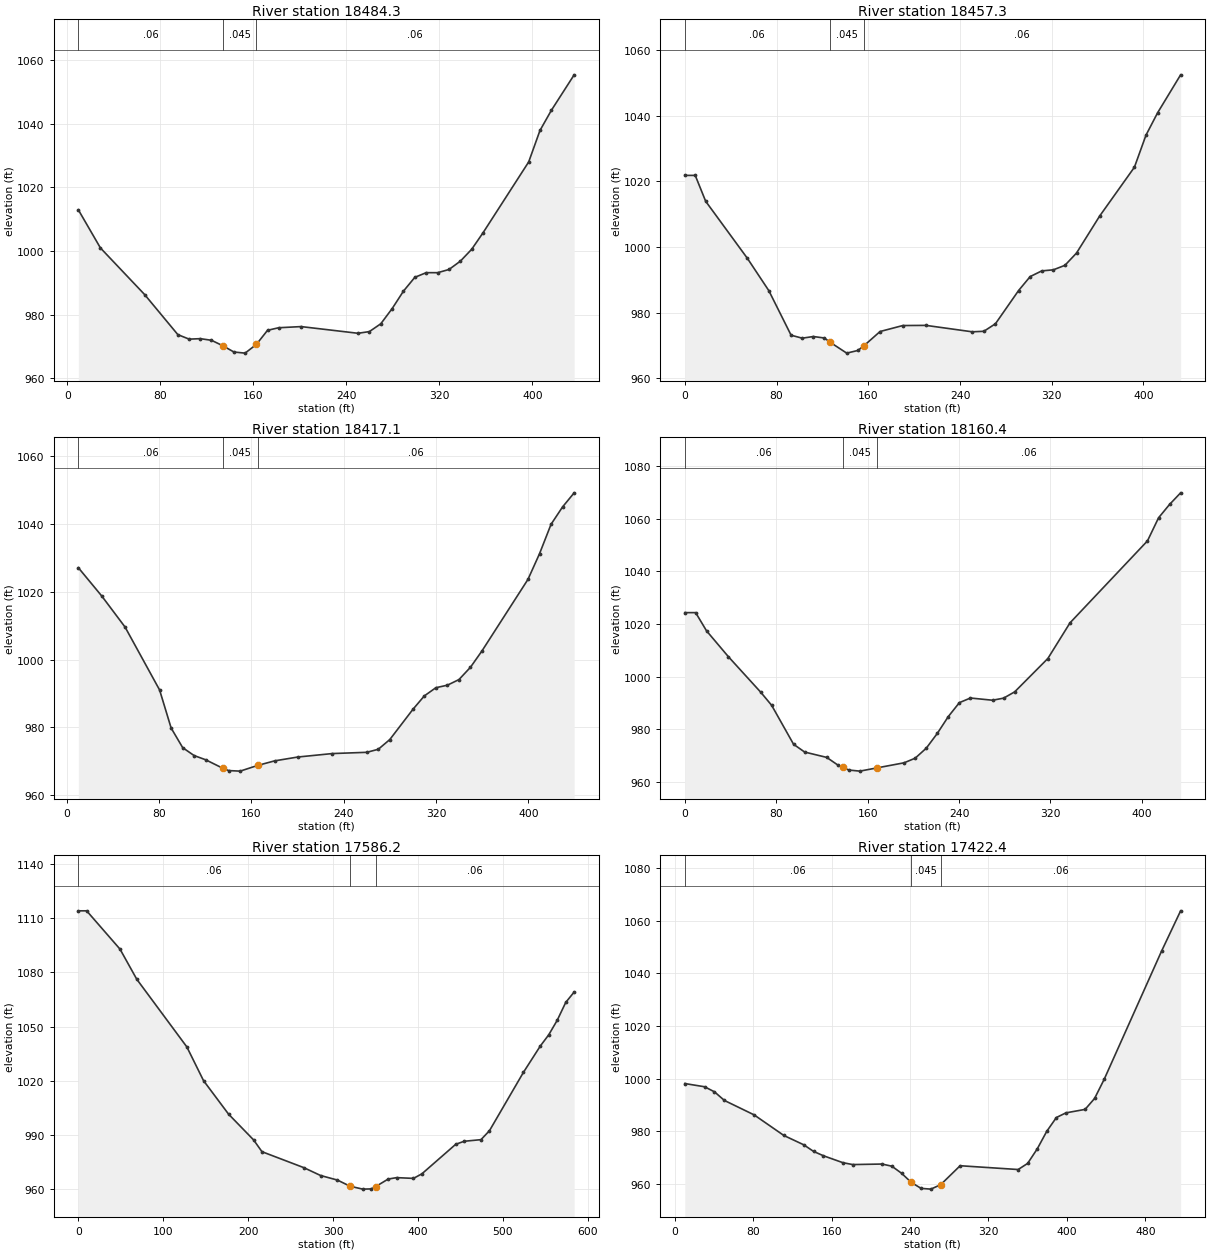
Type RM Length L Ch R = 1 ,18484.3 ,28.7,27,25.3
XS GIS Cut Line= 4
     1696832.837      211833.593     1696747.822      211842.489
     1696633.151      211857.318     1696414.683      211943.321
#Sta/Elev= 30
     9.5 1012.95    28.5 1000.98    66.5  986.35    95.1  973.76   104.8  972.35
   114.4   972.5     124  971.99   133.7  970.29   143.3  968.31   152.9  967.96
   162.6  970.68   172.2  975.12   181.8  975.93   201.1  976.29     250  974.19
   259.8  974.72   269.6  977.17   279.4  981.95   289.1  987.42   298.9  991.76
   308.7  993.22   318.5  993.21   328.3  994.22   338.1  996.85   347.8 1000.57
   357.6 1005.77   396.8 1027.98   406.5 1037.85   416.3 1044.18   435.9 1055.32
#Mann= 3 , 0 , 0
     9.5     .06       0   133.7    .045       0   162.6     .06       0
Bank Sta=133.7,162.6
XS Rating Curve= 0 ,0
Exp/Cntr=0.3,0.1

Type RM Length L Ch R = 1 ,18457.3 ,40.7,40.2,39.6
XS GIS Cut Line= 4
      1696823.94      211799.982     1696760.673      211806.902
      1696646.99      211831.615     1696414.683       211930.47
#Sta/Elev= 30
       0 1021.86     9.1 1021.86    18.2 1013.97    54.6  996.56    73.3  986.71
    92.7  973.13   102.4  972.23   112.1  972.73   121.8  972.28   126.2  971.11
   141.2  967.67   150.9  968.48   156.2  969.91   170.3  974.26   190.1  976.08
   210.3  976.13   250.7  974.17   260.8  974.33   270.9  976.62   291.1  986.76
   301.2  991.01   311.3  992.74   321.4  993.07   331.5  994.44   341.6  998.18
   361.8 1009.47   392.1 1024.35   402.2 1034.13   412.3 1040.93   432.4 1052.52
#Mann= 3 , 0 , 0
       0     .06       0   126.2    .045       0   156.2     .06       0
Bank Sta=126.2,156.2
XS Rating Curve= 0 ,0
Exp/Cntr=0.3,0.1

Type RM Length L Ch R = 1 ,18417.1 ,258.8,256.7,254.6
XS GIS Cut Line= 4
     1696814.054      211773.291     1696764.627      211762.417
     1696532.319      211819.753     1696412.705       211909.71
#Sta/Elev= 30
    10.1 1027.13    30.4 1018.77    50.6 1009.61    80.5  991.06    90.5  979.83
   100.5  974.05   110.4  971.72   120.4  970.48   135.3  967.97   140.3  967.29
   150.3  967.13   165.3   968.8   180.2  970.16   200.2  971.29   230.1  972.31
     260  972.68   269.9  973.57   279.9  976.44   299.9  985.34   309.8  989.31
   319.8  991.73   329.8  992.48   339.8  994.13   349.8  997.77   359.7 1002.56
   399.6 1023.69   409.6 1031.25   419.6 1039.94   429.6 1045.07   439.6 1049.21
#Mann= 3 , 0 , 0
    10.1     .06       0   135.3    .045       0   165.3     .06       0
#XS Ineff= 2 , 0
       0     120             185       0
Permanent Ineff=
       F       F
Bank Sta=135.3,165.3
XS Rating Curve= 0 ,0
Exp/Cntr=0.3,0.1

Type RM Length L Ch R = 1 ,18160.4 ,580.9,574.2,567.6
XS GIS Cut Line= 4
     1696716.518      211489.744     1696638.753      211525.332
      1696456.68      211590.811     1696323.737      211670.318
#Sta/Elev= 30
       0 1024.31     9.5 1024.31      19 1017.41      38 1007.65    66.5  994.07
      76  989.12    95.2  974.32   104.9  971.37   124.2  969.34   133.9  966.45
   138.2   965.6   143.6  964.54   153.2  964.13   168.2  965.36   191.9  967.29
   201.6  969.04   211.3  972.83     221  978.47   230.6  984.85   240.3  990.14
     250  991.89   269.3  991.05     279  991.84   288.7  994.24   317.7 1006.89
   337.1 1020.43   404.9 1051.56   414.6 1060.32   424.2 1065.38   433.9  1069.8
#Mann= 3 , 0 , 0
       0     .06       0   138.2    .045       0   168.2     .06       0
Bank Sta=138.2,168.2
XS Rating Curve= 0 ,0
Exp/Cntr=0.3,0.1

Type RM Length L Ch R = 1 ,17586.2 ,155,163.8,172.6
XS GIS Cut Line= 4
     1696797.618      210952.871     1696532.249      210951.114
     1696384.626       211068.86     1696280.241      211145.731
#Sta/Elev= 30
       0 1114.16     9.8 1114.16    49.1  1092.9    68.8 1076.23   127.8 1038.68
   147.4 1020.01   176.9 1001.42   206.4  987.12   216.2  980.61   265.4  971.78
   285.3  967.39   305.1  964.87   319.9  961.46   334.9  959.85   344.9  959.98
   349.9   961.2   364.8  965.43   374.7  966.22   394.6  965.81   404.5  968.33
   444.3  984.69   454.2  986.38   474.1  987.28   484.1  992.26     524 1024.55
     544 1039.23   553.9 1045.44   563.9 1053.52   573.9 1063.39   583.8 1069.14
#Mann= 3 , 0 , 0
       0     .06       0   319.9    .045       0   349.9     .06       0
Bank Sta=319.9,349.9
XS Rating Curve= 0 ,0
Exp/Cntr=0.3,0.1

Type RM Length L Ch R = 1 ,17422.4 ,272.8,256.7,240.6
XS GIS Cut Line= 4
     1696615.028      210771.402     1696481.904      210843.895
     1696317.146      210883.437     1696216.974       211050.83
#Sta/Elev= 30
    10.1  998.17    30.3  996.95    40.4  995.02    50.5  991.76    80.8  986.29
   111.2  978.46   131.4  974.94   141.5  972.42   151.6  970.76   171.5  968.13
   181.5  967.42   211.4  967.62   221.4   966.8   231.3  964.13   241.3  960.62
   251.3  958.38   261.2   958.1   271.2  959.78   291.1  966.98   350.3  965.54
     360  967.87   369.8  973.39   379.5  980.05   389.3  985.27     399  987.04
   418.6  988.36   428.3  992.51   438.1  999.79   496.6 1048.39   516.1 1063.72
#Mann= 3 , 0 , 0
    10.1     .06       0   241.3    .045       0   271.2     .06       0
Bank Sta=241.3,271.2
XS Rating Curve= 0 ,0
Exp/Cntr=0.3,0.1

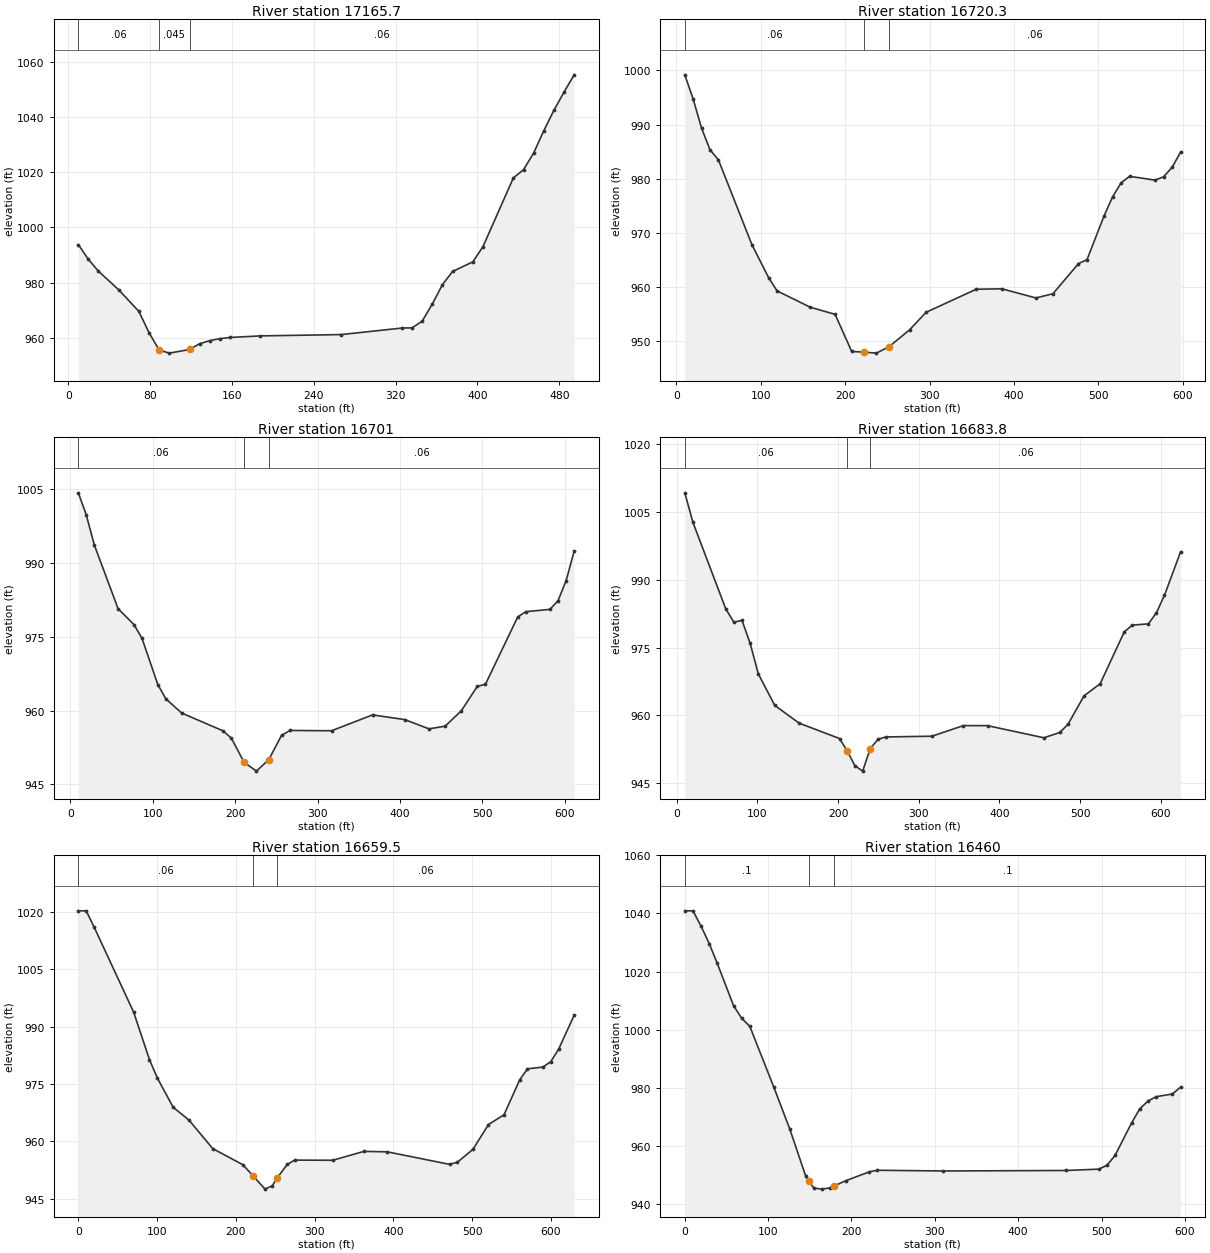
Type RM Length L Ch R = 1 ,17165.7 ,437.6,445.4,453.2
XS GIS Cut Line= 4
     1696379.095      210567.103     1696347.462      210617.189
     1696235.246      210803.491     1696145.799      211002.062
#Sta/Elev= 30
     9.9  993.75    19.7  988.43    29.6  984.11    49.4  977.37    69.1  969.54
      79  961.83    88.9  955.56    98.8  954.43   118.6  955.75   128.4  957.83
   138.3  958.95   148.2  959.68   158.1   960.1   187.8  960.68   266.8  961.15
   326.2  963.52   336.1  963.59     346  966.02   355.9  972.25   365.8  979.27
   375.7  984.02   395.5  987.52   405.4  993.04   435.1 1017.95     445  1020.9
   454.9 1026.94   464.8 1035.01   474.7 1042.42   484.6 1049.03   494.5 1055.29
#Mann= 3 , 0 , 0
     9.9     .06       0    88.9    .045       0   118.6     .06       0
Bank Sta=88.9,118.6
XS Rating Curve= 0 ,0
Exp/Cntr=0.3,0.1

Type RM Length L Ch R = 1 ,16720.3 ,19.9,19.3,18.8
XS GIS Cut Line= 4
     1696109.041      210408.264     1695985.382      210471.846
     1695828.066      210588.746      1695666.42      210795.279
#Sta/Elev= 30
     9.9  999.19    19.9  994.66    29.8  989.31    39.7  985.34    49.7  983.47
    89.4  967.78   109.3  961.64   119.2  959.22   158.6   956.2     188  954.88
   207.6  948.02     222   947.9     237  947.71     252  948.91   276.2  952.02
   295.8  955.27   355.2  959.53   385.5  959.61   425.8  957.92     446  958.69
   476.3  964.27   486.4     965   506.5  973.05   516.6  976.59   526.7  979.19
   536.8  980.42     567  979.71   577.1  980.33   587.2  982.07   597.3  984.91
#Mann= 3 , 0 , 0
     9.9     .06       0     222    .045       0     252     .06       0
#XS Ineff= 2 , 0
       0     197             266       0
Permanent Ineff=
       F       F
Bank Sta=222,252
XS Rating Curve= 0 ,0
Exp/Cntr=0.3,0.1

Type RM Length L Ch R = 1 ,16701   ,17.1,17.1,17.2
XS GIS Cut Line= 4
     1696102.368      210398.626     1695969.837      210456.923
     1695818.409      210575.822     1695649.368      210791.572
#Sta/Elev= 30
     9.7 1004.29    19.3  999.82      29  993.74    57.9  980.74    77.2   977.5
    86.9  974.72   106.2  965.29   115.8  962.42   135.1  959.51   185.3  955.89
   195.5  954.38   210.9  949.48   225.9   947.7   240.9  950.06   256.3  954.96
   266.4  955.97     317  955.91   366.7  959.13   405.8  958.18   435.2   956.3
   454.8  956.84   474.4  959.95   493.9  964.95   503.7  965.34   542.9  979.05
   552.7  980.12     582  980.59   591.8  982.35   601.6   986.4   611.4  992.41
#Mann= 3 , 0 , 0
     9.7     .06       0   210.9    .045       0   240.9     .06       0
#XS Ineff= 2 , 0
       0                     266       0
Permanent Ineff=
       F       F
Bank Sta=210.9,240.9
XS Rating Curve= 0 ,0
Exp/Cntr=0.3,0.1

Type RM Length L Ch R = 1 ,16683.8 ,26.9,24.3,21.8
XS GIS Cut Line= 4
     1696094.954      210388.246     1695922.206      210472.766
     1695809.512      210560.994      1695629.35      210787.123
#Sta/Elev= 30
    10.1 1009.19    20.2 1002.66    60.7  983.62    70.9   980.6      81  981.01
    91.1   975.9   101.2   969.2   121.5  962.23   151.8  958.29   201.9  954.89
   211.4  952.14   220.9  948.91   230.5  947.69     240  952.69   249.6  954.73
   259.1  955.24   316.4  955.41   355.4  957.75   385.3  957.74   455.1  955.06
     475  956.24     485  958.04   504.9  964.32   524.9  967.01   554.8  978.48
   564.7  979.96   584.7  980.23   594.7  982.72   604.6  986.55   624.6  996.18
#Mann= 3 , 0 , 0
    10.1     .06       0   211.4    .045       0     240     .06       0
Bank Sta=211.4,240
XS Rating Curve= 0 ,0
Exp/Cntr=0.3,0.1

Type RM Length L Ch R = 1 ,16659.5 ,208.5,199.5,190.5
XS GIS Cut Line= 4
     1696081.609      210365.262     1695916.275       210437.92
     1695836.944      210517.992     1695623.419      210777.485
#Sta/Elev= 30
       0 1020.21      10 1020.21    20.1 1015.94    70.2  993.76    90.3  981.36
   100.3  976.55   120.4  968.92   140.5  965.57   170.6  958.13   208.8  953.93
     222  950.97     237  947.55   246.3  948.45     252  950.36   265.1  953.98
   274.5  955.12     323  955.09   362.5   957.4   392.1  957.29   471.2  954.02
   481.1  954.56   500.9  957.93   520.6  964.41   540.4  966.97   560.2  976.05
   570.1  978.95   589.8  979.42   599.7  980.85   609.6  984.05   629.4  992.96
#Mann= 3 , 0 , 0
       0     .06       0     222    .045       0     252     .06       0
Bank Sta=222,252
XS Rating Curve= 0 ,0
Exp/Cntr=0.3,0.1

Type RM Length L Ch R = 1 ,16460   ,338.7,339.4,340
XS GIS Cut Line= 5
     1695736.682       210226.35     1695727.838      210313.679
     1695674.777      210467.334     1695530.754      210532.096
     1695450.375       210700.58
#Sta/Elev= 30
       0 1040.89     9.8 1040.89    19.5 1035.61    29.3 1029.62      39 1022.77
    58.5 1008.24    68.3 1003.88      78 1001.11   106.9  980.11     126  965.73
   145.1  949.53   149.3  947.75   154.7  945.45   164.3  945.07   173.8  945.48
   179.3  946.19     193  947.95   221.6  951.05   231.2  951.57   309.6  951.32
   457.4  951.49   496.7  951.95   506.5  953.26   516.3   956.7     536  967.82
   545.8   972.7   555.6  975.37   565.4  976.89   585.1  977.83   594.9  980.22
#Mann= 3 , 0 , 0
       0      .1       0   149.3    .045       0   179.3      .1       0
Bank Sta=149.3,179.3
XS Rating Curve= 0 ,0
Exp/Cntr=0.3,0.1

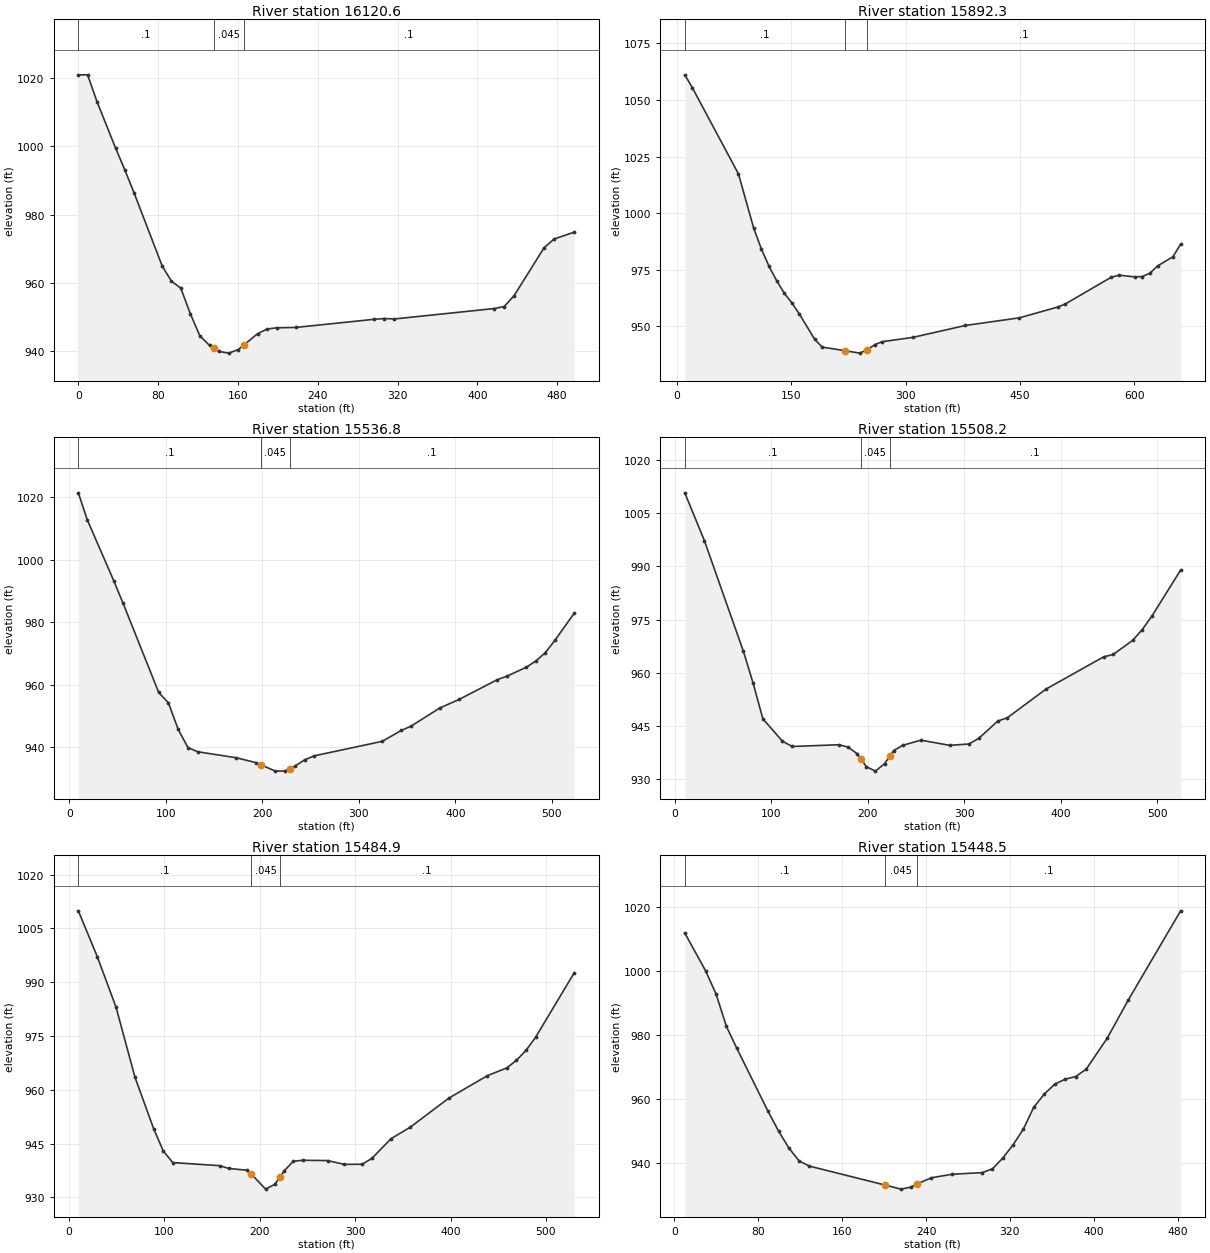
Type RM Length L Ch R = 1 ,16120.6 ,216.9,228.3,239.7
XS GIS Cut Line= 4
     1695457.007      210182.132     1695395.147       210264.06
     1695339.789      210407.728     1695252.797      210631.798
#Sta/Elev= 30
       0 1020.99     9.3 1020.99    18.7 1013.13    37.3  999.53    46.7  993.03
      56  986.27      84  964.94    93.3  960.46   102.7  958.41   112.3  950.87
   121.9  944.37   131.5  941.63   135.8  940.83   141.1  939.84   150.8  939.35
   160.4   940.4   165.8  941.69   179.6  945.04   189.3  946.42   198.9  946.79
   218.1  946.89   296.7  949.28   306.7   949.5   316.7  949.37   416.9  952.43
   426.9  953.02   436.9  956.25   466.9  970.29     477  972.84     497  974.83
#Mann= 3 , 0 , 0
       0      .1       0   135.8    .045       0   165.8      .1       0
Bank Sta=135.8,165.8
XS Rating Curve= 0 ,0
Exp/Cntr=0.3,0.1

Type RM Length L Ch R = 1 ,15892.3 ,360.1,355.5,350.9
XS GIS Cut Line= 4
     1695367.085      210049.561     1695259.883      210140.947
     1695077.112      210276.268     1694966.395      210546.909
#Sta/Elev= 30
    10.1 1061.07    20.1 1055.33    80.5 1017.34   100.6  993.26   110.7  984.07
   120.7  976.45   130.8  970.09   140.9  964.55   150.8  960.29   160.6  955.39
   180.4  944.36   190.3  940.86     220  939.28   239.7  938.19   249.6   939.7
   259.5  941.97   269.4  943.25     309  945.12   378.4  950.41   448.9  953.76
   499.4  958.53   509.4  959.89   569.9  971.75     580  972.59   600.2  971.87
   610.3  972.01   620.4  973.49   630.4  976.67   650.6  980.75   660.7  986.31
#Mann= 3 , 0 , 0
    10.1      .1       0     220    .045       0   249.6      .1       0
Bank Sta=220,249.6
XS Rating Curve= 0 ,0
Exp/Cntr=0.3,0.1

Type RM Length L Ch R = 1 ,15536.8 ,27.2,28.6,30
XS GIS Cut Line= 4
     1695117.532      209743.497      1695058.22      209814.673
     1694914.881      209983.714     1694827.889      210173.514
#Sta/Elev= 30
     9.3 1021.47    18.5 1012.88    46.3  993.11    55.6  986.16    92.6  957.53
   102.7   954.2   112.8  945.69   122.9  939.89   132.9  938.56   173.2  936.62
   193.4  935.07   198.5  934.37   213.5  932.35   223.6  932.41   228.5  933.15
   233.7  933.93   243.8  935.96   253.8  937.25   324.2  941.89   344.1   945.4
   354.1  946.75   383.9  952.57   403.8   955.3   443.5  961.64   453.5  962.77
   473.4   965.6   483.3  967.59   493.2  970.28   503.2  974.25   523.1  982.92
#Mann= 3 , 0 , 0
     9.3      .1       0   198.5    .045       0   228.5      .1       0
#XS Ineff= 2 , 0
       0     170             260       0
Permanent Ineff=
       F       F
Bank Sta=198.5,228.5
XS Rating Curve= 0 ,0
Exp/Cntr=0.3,0.1

Type RM Length L Ch R = 1 ,15508.2 ,23.9,23.3,22.8
XS GIS Cut Line= 4
     1695087.656       209731.47     1695001.873      209844.329
     1694922.789      209925.389     1694818.004      210173.514
#Sta/Elev= 30
    10.1 1010.71    30.4  997.26    70.9  966.07      81  957.08    91.1  947.06
   111.4  940.77   121.5  939.28   170.1  939.77   179.5   939.1   188.9  937.24
   192.8  935.75   198.4  933.61   207.8  932.34   217.3  934.44   222.8  936.59
   226.7  938.11   236.1   939.6     255  941.06   284.9   939.6   304.9  939.99
   314.9  941.54   334.8  946.45   344.8  947.39   384.7  955.43   444.5  964.52
   454.5   965.2   474.5  969.13   484.4  972.14   494.4  975.92   524.4  988.95
#Mann= 3 , 0 , 0
    10.1      .1       0   192.8    .045       0   222.8      .1       0
Bank Sta=192.8,222.8
XS Rating Curve= 0 ,0
Exp/Cntr=0.3,0.1

Type RM Length L Ch R = 1 ,15484.9 ,35.9,36.4,36.9
XS GIS Cut Line= 5
     1695077.002      209723.726     1694984.079      209826.535
     1694911.915       209904.63     1694905.297      209956.587
     1694810.211      210168.513
#Sta/Elev= 30
     9.9 1009.89    29.7  997.16    49.5  982.97    69.3  963.48    89.1     949
      99  942.93   108.9  939.73   157.9  938.87   167.6   938.1   186.9  937.58
   191.2  936.54   206.2  932.33   215.9  933.69   221.2  935.71   225.6   937.4
   235.2  940.09   244.9  940.37   271.1  940.29   288.6  939.23   307.4  939.26
   317.5  940.88   337.7  946.39   357.9  949.61   398.3   957.7   438.7  963.96
   458.9  966.09     469   968.2   479.1  970.99   489.2  974.66   529.6  992.59
#Mann= 3 , 0 , 0
     9.9      .1       0   191.2    .045       0   221.2      .1       0
Bank Sta=191.2,221.2
XS Rating Curve= 0 ,0
Exp/Cntr=0.3,0.1

Type RM Length L Ch R = 1 ,15448.5 ,324.9,325.8,326.7
XS GIS Cut Line= 4
     1695071.557      209713.104     1694976.472      209784.835
     1694834.678      209931.077     1694706.167      210026.626
#Sta/Elev= 30
     9.9 1011.91    29.8 1000.09    39.7  992.89    49.6  982.77    59.6  975.88
    89.3  956.27    99.3  950.14   109.2   944.8   119.1  940.73   128.8  939.16
   201.1  933.24   216.1  931.98   225.8  932.62   231.1  933.55   245.2  935.53
   264.6  936.61   293.7  937.14   303.4  938.31   313.1  941.63   322.8  945.68
   332.8  950.67   342.8  957.54   352.8  961.63   362.8  964.73   372.8  966.29
   382.9  967.13   392.9  969.44   412.9  979.11   432.9  990.97   482.9 1018.84
#Mann= 3 , 0 , 0
     9.9      .1       0   201.1    .045       0   231.1      .1       0
#XS Ineff= 2 , 0
       0     170             264       0
Permanent Ineff=
       F       F
Bank Sta=201.1,231.1
XS Rating Curve= 0 ,0
Exp/Cntr=0.3,0.1

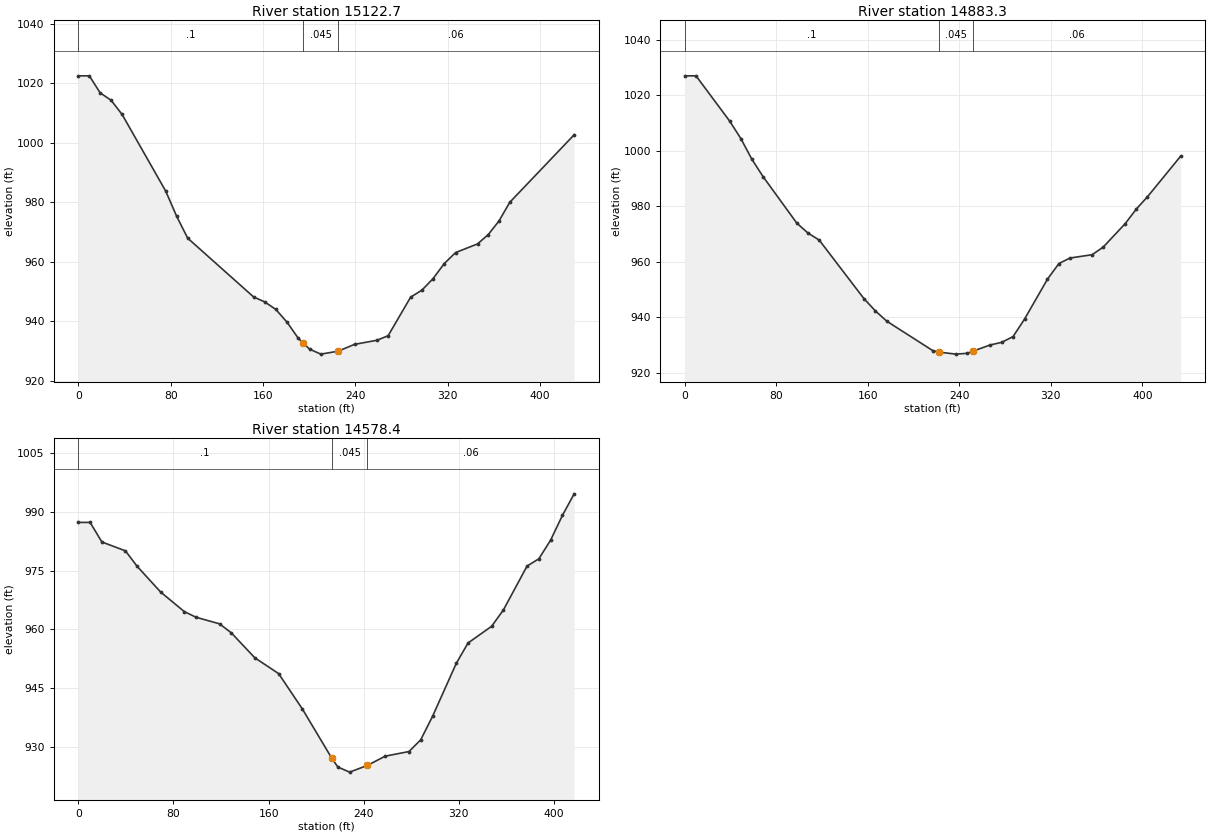
Type RM Length L Ch R = 1 ,15122.7 ,241.9,239.5,237
XS GIS Cut Line= 4
     1694845.551      209468.099     1694741.754      209564.976
     1694600.393       209698.43     1694535.149      209764.662
#Sta/Elev= 30
       0 1022.49     9.5 1022.49    18.9 1016.78    28.4 1014.26    37.9 1009.51
    75.7  983.73    85.2  975.24    94.7  967.93   151.7   948.2   161.4   946.5
   171.1  943.96   180.9   939.6   190.6  934.21     195  932.58   200.3  930.62
     210  928.95     225  929.94   239.2  932.23   258.6  933.61   268.3  935.14
   287.8  948.11   297.5  950.44   307.2  954.32   316.9  959.39   326.7  963.08
   345.7  965.99     355  969.13   364.3   973.7   373.6  979.96   429.4 1002.68
#Mann= 3 , 0 , 0
       0      .1       0     195    .045       0     225     .06       0
Bank Sta=195,225
XS Rating Curve= 0 ,0
Exp/Cntr=0.3,0.1

Type RM Length L Ch R = 1 ,14883.3 ,307.1,304.8,302.5
XS GIS Cut Line= 4
     1694654.399      209278.152     1694556.862      209400.732
     1694448.782      209532.538     1694377.606      209611.621
#Sta/Elev= 30
       0 1027.01     9.8 1027.01    39.2 1010.73      49 1004.42    58.7  996.92
    68.5  990.68    97.9  973.98   107.7  970.39   117.5  967.87   156.6  946.79
   166.7  942.32   176.7  938.62   216.8  928.05   221.9  927.54   236.9  926.79
   246.9  927.08   251.9  927.85   266.9  930.08     277  931.03     287  933.11
     297  939.38   317.1   953.8   327.1  959.42   336.8   961.4   356.1  962.59
   365.8  965.33   385.1  973.81   394.8  979.05   404.5  983.45   433.5  998.06
#Mann= 3 , 0 , 0
       0      .1       0   221.9    .045       0   251.9     .06       0
Bank Sta=221.9,251.9
XS Rating Curve= 0 ,0
Exp/Cntr=0.3,0.1

Type RM Length L Ch R = 1 ,14578.4 ,266.7,262.1,257.5
XS GIS Cut Line= 4
     1694392.798      209107.281     1694305.807      209215.032
     1694207.941      209365.291      1694160.49      209452.282
#Sta/Elev= 30
       0  987.29     9.9  987.29    19.8   982.3    39.6  980.04    49.5  976.07
    69.2  969.54      89  964.57    98.9  963.11   118.7  961.43   128.6  959.14
   148.4  952.76   168.4  948.74   188.3  939.75   213.1  927.16   218.2  924.91
   228.1  923.61   243.1  925.33     258  927.68     278  928.86   287.9  931.86
   297.9  937.88   317.8  951.36   327.7  956.55   347.5   960.8   357.4  964.96
   377.3  976.16   387.2  978.01   397.1  982.77     407  989.06   416.9  994.58
#Mann= 3 , 0 , 0
       0      .1       0   213.1    .045       0   243.1     .06       0
Bank Sta=213.1,243.1
XS Rating Curve= 0 ,0
Exp/Cntr=0.3,0.1