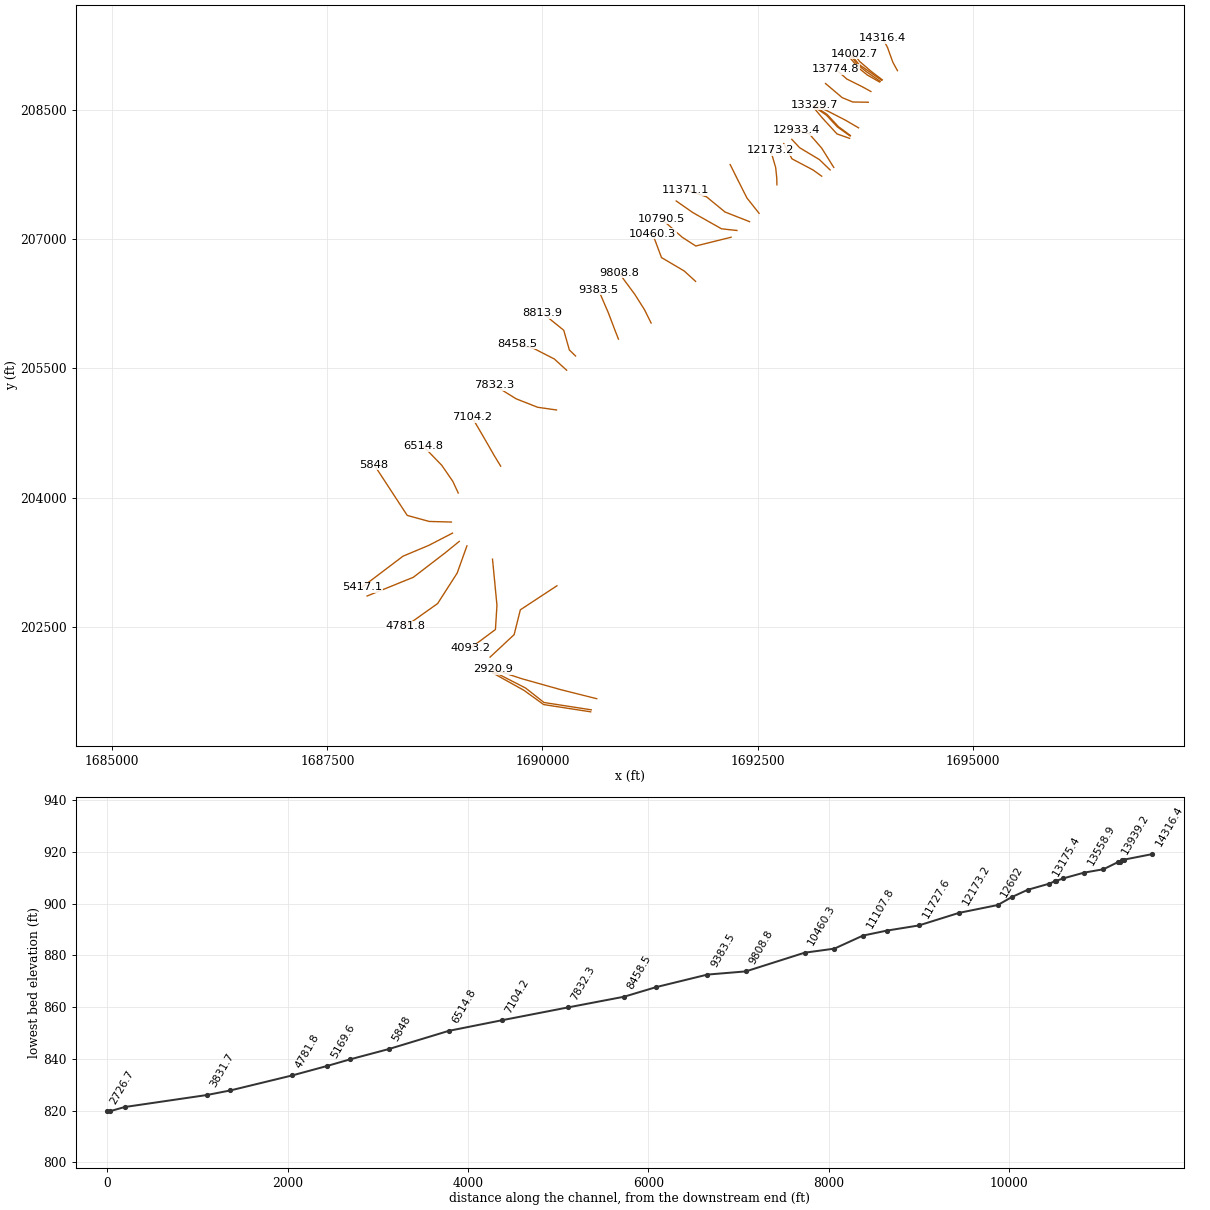
HEC-RAS study bncrk.prj: bncrk

--- bncrk.g01 (geometry) --- (continued)

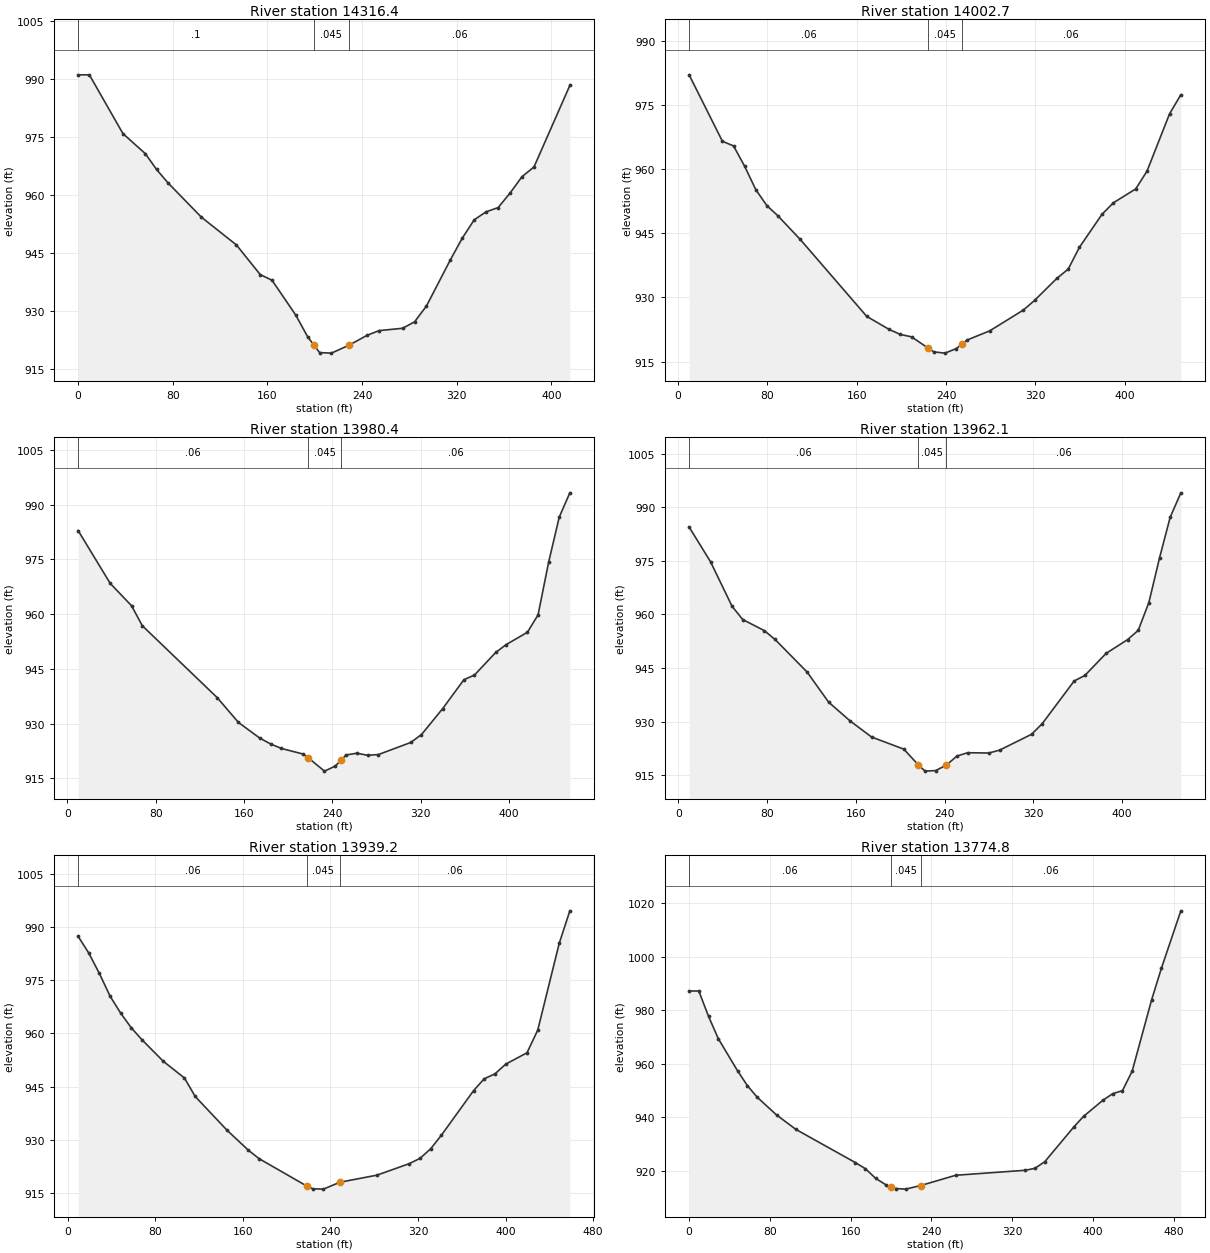
Type RM Length L Ch R = 1 ,14316.4 ,303.3,313.6,324
XS GIS Cut Line= 4
     1694124.903      208959.987     1694070.533       209059.83
     1694009.243       209229.86     1693951.908      209336.623
#Sta/Elev= 30
       0     991     9.5     991    37.9  975.81    56.8  970.64    66.3  966.56
    75.8  963.14   104.2  954.23   133.8  947.06   153.9  939.41   163.9  937.94
     184  928.92     194  923.34   199.1  921.28   204.1  919.26   214.1  919.12
   229.1  921.19   244.2  923.71   254.3  924.93   274.3  925.54   284.4  927.21
   294.4  931.28   314.6   943.2   324.7  948.82   334.8  953.56   344.9  955.63
     355  956.71   365.1  960.47   375.2  964.71   385.3   967.2   415.6  988.25
#Mann= 3 , 0 , 0
       0      .1       0   199.1    .045       0   229.1     .06       0
Bank Sta=199.1,229.1
XS Rating Curve= 0 ,0
Exp/Cntr=0.3,0.1

Type RM Length L Ch R = 1 ,14002.7 ,20.3,22.3,24.3
XS GIS Cut Line= 4
     1693948.757      208853.758      1693821.89      208949.574
     1693685.093      209067.095     1693619.016      209156.252
#Sta/Elev= 30
     9.9  982.06    39.7  966.53    49.7  965.43    59.6  960.69    69.6  955.22
    79.5  951.48    89.4   949.1   109.3   943.6     169  925.57     189  922.53
   199.1  921.35   209.1  920.79   224.1  918.13   229.1  917.27   239.1  916.98
   249.2  918.05   254.1  919.04   259.2  920.08   279.2   922.2   309.3  927.06
   319.3  929.31   339.3  934.47   349.4  936.62   359.5  941.74   379.7  949.44
   389.8  952.12   409.9  955.38     420  959.53   440.2  972.94   450.3   977.4
#Mann= 3 , 0 , 0
     9.9     .06       0   224.1    .045       0   254.1     .06       0
#XS Ineff= 2 , 0
       0     189             279       0
Permanent Ineff=
       F       F
Bank Sta=224.1,254.1
XS Rating Curve= 0 ,0
Exp/Cntr=0.3,0.1

Type RM Length L Ch R = 1 ,13980.4 ,19.6,18.3,17
XS GIS Cut Line= 4
     1693940.833      208847.919     1693790.281      208953.848
     1693678.253      209032.274     1693593.688      209136.737
#Sta/Elev= 30
     9.7  982.87    38.8  968.39    58.1  962.28    67.8  956.82   135.6  937.14
     155   930.3   174.4  925.99   184.1  924.42   193.9  923.18   213.4  921.66
   217.9  920.69   232.9  916.97   242.7  918.35   247.9  919.97   252.5   921.4
   262.2  921.87     272  921.31   281.8  921.51   311.1  924.83   320.8  926.99
     340   934.1   359.2  942.01   368.8  943.29     388  949.47   397.6  951.65
   416.8  955.02   426.4  959.78     436  974.21   445.6  986.56   455.2  993.21
#Mann= 3 , 0 , 0
     9.7     .06       0   217.9    .045       0   247.9     .06       0
Bank Sta=217.9,247.9
XS Rating Curve= 0 ,0
Exp/Cntr=0.3,0.1

Type RM Length L Ch R = 1 ,13962.1 ,23,22.9,22.7
XS GIS Cut Line= 4
     1693924.221      208836.294     1693765.328      208946.706
     1693660.221      209030.409     1693586.208      209131.108
#Sta/Elev= 30
     9.7  984.44      29  974.72    48.4  962.26      58  958.55    77.4  955.46
    87.1  952.99   116.1  943.83   135.4  935.44   154.8  930.17   174.1  925.68
   203.1  922.29  216.03  917.96   222.3  916.13   231.9  916.28   241.5  917.82
   251.1  920.35   260.7  921.28   279.9   921.2   289.5  922.01   318.3  926.44
   327.9  929.41   356.7  941.36   366.3   942.9   385.5  949.09   404.8  952.92
   414.4  955.52     424  963.31   433.6  975.79   443.2  987.17   452.8  994.01
#Mann= 3 , 0 , 0
     9.7     .06       0  216.03    .045       0   241.5     .06       0
Bank Sta=216.03,241.5
XS Rating Curve= 0 ,0
Exp/Cntr=0.3,0.1

Type RM Length L Ch R = 1 ,13939.2 ,160,164.4,168.8
XS GIS Cut Line= 4
     1693917.618      208828.179     1693774.155      208909.919
     1693667.392      208996.108     1693567.858      209116.772
#Sta/Elev= 30
     9.7  987.35    19.4  982.66    29.1  976.89    38.9  970.48    48.6  965.68
    58.3  961.54      68   958.2    87.4  952.15   106.8  947.41   116.6   942.2
   145.7  932.68   165.1  927.07   174.9  924.68   218.7  916.91   223.9  916.18
   233.7  916.08   248.7  918.02   282.7  920.03   312.1  923.27   321.9  924.76
   331.7  927.48   341.4  931.28   370.8  943.85   380.5   947.2   390.3  948.57
   400.1  951.31   419.6  954.53   429.4  960.92     449  985.37   458.7  994.55
#Mann= 3 , 0 , 0
     9.7     .06       0   218.7    .045       0   248.7     .06       0
#XS Ineff= 2 , 0
       0     204             254       0
Permanent Ineff=
       F       F
Bank Sta=218.7,248.7
XS Rating Curve= 0 ,0
Exp/Cntr=0.3,0.1

Type RM Length L Ch R = 1 ,13774.8 ,214.7,215.9,217.2
XS GIS Cut Line= 4
     1693816.045      208718.358     1693706.316      208778.412
     1693537.275      208862.191     1693407.529      208977.109
#Sta/Elev= 30
       0  987.17     9.6  987.17    19.2  977.74    28.9  969.39    48.1  957.33
    57.7  951.89    67.4  947.56    86.6  940.94   105.8  935.54   164.8  923.15
   174.7  920.87   184.7  917.32   194.6  914.95   199.5  914.23   204.5   913.5
   214.5  913.27   229.5  914.62   264.1  918.44     333   920.3   342.6  921.03
   352.3  923.49   381.2   936.5   390.8  940.43     410  946.45   419.7  948.88
   429.3  950.02   438.9  957.27   458.2  983.92   467.8  995.58   487.1 1017.07
#Mann= 3 , 0 , 0
       0     .06       0   199.5    .045       0   229.5     .06       0
Bank Sta=199.5,229.5
XS Rating Curve= 0 ,0
Exp/Cntr=0.3,0.1

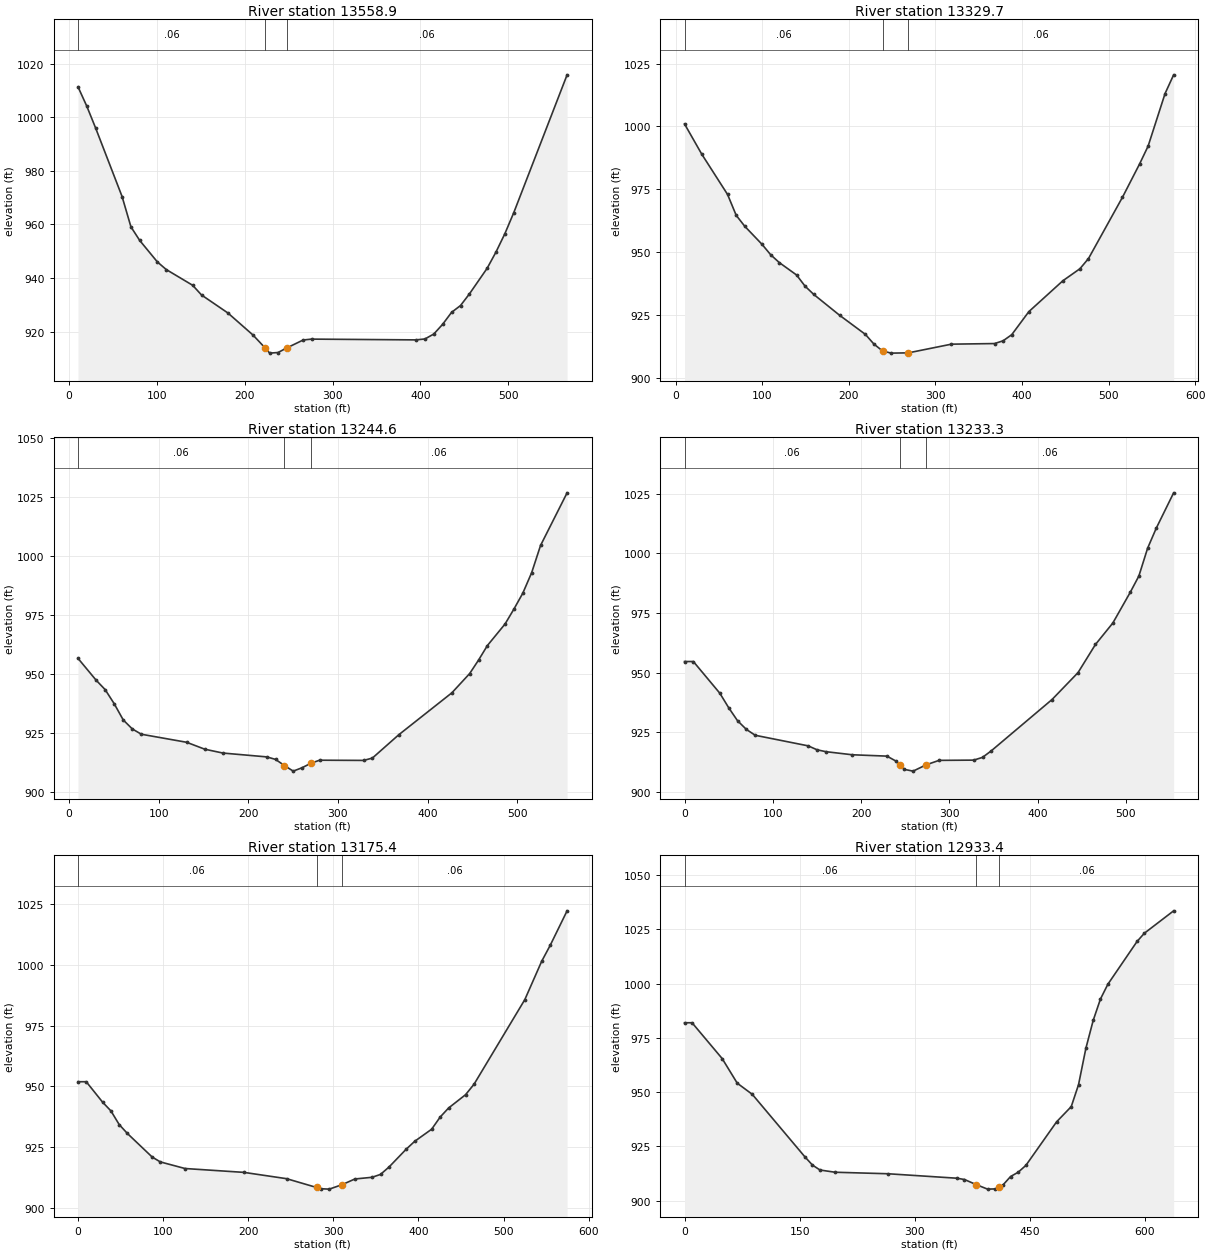
Type RM Length L Ch R = 1 ,13558.9 ,230.5,229.2,227.9
XS GIS Cut Line= 4
     1693785.647       208593.06     1693604.744      208596.026
      1693481.67      208647.183     1693288.904      208811.034
#Sta/Elev= 30
    10.1 1011.34    20.1 1004.12    30.2  995.94    60.3   970.4    70.4  959.08
    80.4     954   100.5  945.99   110.6  943.15   140.7  937.27   150.8  933.65
   180.9  926.92   209.5  918.68  222.87  914.02   228.5  911.95     238  912.18
   247.6  913.84   266.6  916.85   276.1  917.18   395.2  916.89   405.3  917.24
   415.4  919.09   425.5  922.73   435.6  927.16   445.8  929.71   455.9  934.03
   476.1   943.6   486.2  949.67   496.4  956.58   506.5   964.4   567.2 1015.81
#Mann= 3 , 0 , 0
    10.1     .06       0  222.87    .045       0   247.6     .06       0
Bank Sta=222.87,247.6
XS Rating Curve= 0 ,0
Exp/Cntr=0.3,0.1

Type RM Length L Ch R = 1 ,13329.7 ,92.4,85.1,77.8
XS GIS Cut Line= 4
     1693673.072      208295.642     1693518.242      208385.803
     1693323.617      208485.914     1693164.435       208563.64
#Sta/Elev= 30
      10    1001    29.9  988.96    59.7  972.93    69.7  964.61    79.6  960.25
    99.5  953.08   109.5  948.93   119.4  945.82   139.4  940.87   149.3   936.4
   159.3  933.12   189.1  924.84     219   917.2   228.9  913.33   238.9  910.59
   248.8  909.74   268.7  909.85   318.4  913.31   368.2  913.55   378.1  914.64
   388.1  917.08   407.9  926.27   447.2  938.56   466.9  943.34   476.8   947.4
   516.1  971.83   535.8  985.03   545.7  992.17   565.3 1013.12   575.2 1020.56
#Mann= 3 , 0 , 0
      10     .06       0   238.9    .045       0   268.7     .06       0
Bank Sta=238.9,268.7
XS Rating Curve= 0 ,0
Exp/Cntr=0.3,0.1

Type RM Length L Ch R = 1 ,13244.6 ,11.3,11.3,11.3
XS GIS Cut Line= 4
     1693578.053      208206.786     1693439.895        208308.7
     1693306.206      208452.337      1693148.89      208554.935
#Sta/Elev= 30
    10.1  956.48    30.3  947.24    40.4  943.23    50.5  937.25    60.6  930.37
    70.7  926.57    80.8  924.33   131.3  920.92   151.5  917.99   171.7  916.36
   220.7  914.73   230.5  913.66   240.4  911.06   250.2   908.7     260  910.13
   269.8  912.01   279.6  913.33   328.7  913.24   338.5  914.23   367.9   924.1
   427.2  941.89     447  950.03   456.9  955.73   466.8  961.91   486.5  971.04
   496.4  977.37   506.3  984.09   516.2  992.81   526.1 1004.32   555.7 1026.61
#Mann= 3 , 0 , 0
    10.1     .06       0   240.4    .045       0   269.8     .06       0
Bank Sta=240.4,269.8
XS Rating Curve= 0 ,0
Exp/Cntr=0.3,0.1

Type RM Length L Ch R = 1 ,13233.3 ,58,57.8,57.7
XS GIS Cut Line= 4
     1693574.205      208201.127     1693427.458      208305.591
     1693299.988      208442.388      1693145.78      208548.095
#Sta/Elev= 30
       0  954.63      10  954.63      40  941.31      50  935.24      60  929.79
    70.1  926.11    80.1  923.66   140.1  919.22   150.1  917.57   160.1  916.78
     190  915.48   229.3  914.91   239.2  912.89   243.9  911.19     249  909.34
   258.9  908.61   273.9  911.28   288.4  913.13   327.7  913.23   337.6  914.39
   347.4   917.1   416.3  938.66   445.8  949.98   465.5  961.78   485.2  970.79
   504.9  983.66   514.7  990.52   524.6 1002.19   534.4 1010.61   554.1 1025.46
#Mann= 3 , 0 , 0
       0     .06       0   243.9    .045       0   273.9     .06       0
Bank Sta=243.9,273.9
XS Rating Curve= 0 ,0
Exp/Cntr=0.3,0.1

Type RM Length L Ch R = 1 ,13175.4 ,242.5,242,241.5
XS GIS Cut Line= 4
     1693568.608      208173.768     1693422.484      208224.756
     1693252.731      208409.432     1693143.915      208538.768
#Sta/Elev= 30
       0  951.94     9.7  951.94      29  943.48    38.7  939.92    48.4   934.3
      58  930.64    87.1  920.94    96.7  918.92   125.7   916.2   194.9  914.61
   245.1  912.01   280.2   908.4   285.2  907.87   295.2  907.71   310.2  909.54
   325.3  911.89   345.4  912.58   355.4  913.77   365.5  916.85   385.5  924.13
   395.6  927.41   415.5  932.39   425.5   937.4   435.4  941.13   455.3  946.59
   465.3  950.92   524.9  985.73   544.8 1001.58   554.7 1008.07   574.6 1022.32
#Mann= 3 , 0 , 0
       0     .06       0   280.2    .045       0   310.2     .06       0
Bank Sta=280.2,310.2
XS Rating Curve= 0 ,0
Exp/Cntr=0.3,0.1

Type RM Length L Ch R = 1 ,12933.4 ,171.3,177.6,183.8
XS GIS Cut Line= 4
     1693384.381      207836.124     1693243.932      208060.808
      1693099.12      208226.623     1692952.057      208267.129
#Sta/Elev= 30
       0  981.97     9.8  981.97    49.1  965.45    68.7  954.13    88.3  948.99
     157  920.15   166.8  916.39   176.6  914.12   196.3  913.09     265   912.4
     355  910.34     365  909.74   380.1  907.42   395.1  905.31   405.1  905.41
   410.1   906.3   415.1  907.19   425.1  911.12   435.1  913.11   445.1  916.27
   485.1  936.32   504.2  943.33   513.7  953.44   523.3  970.23   532.8  983.04
   542.3  992.92   551.9  999.69     590 1019.42   599.5 1023.21   637.7 1033.54
#Mann= 3 , 0 , 0
       0     .06       0   380.1    .045       0   410.1     .06       0
Bank Sta=380.1,410.1
XS Rating Curve= 0 ,0
Exp/Cntr=0.3,0.1

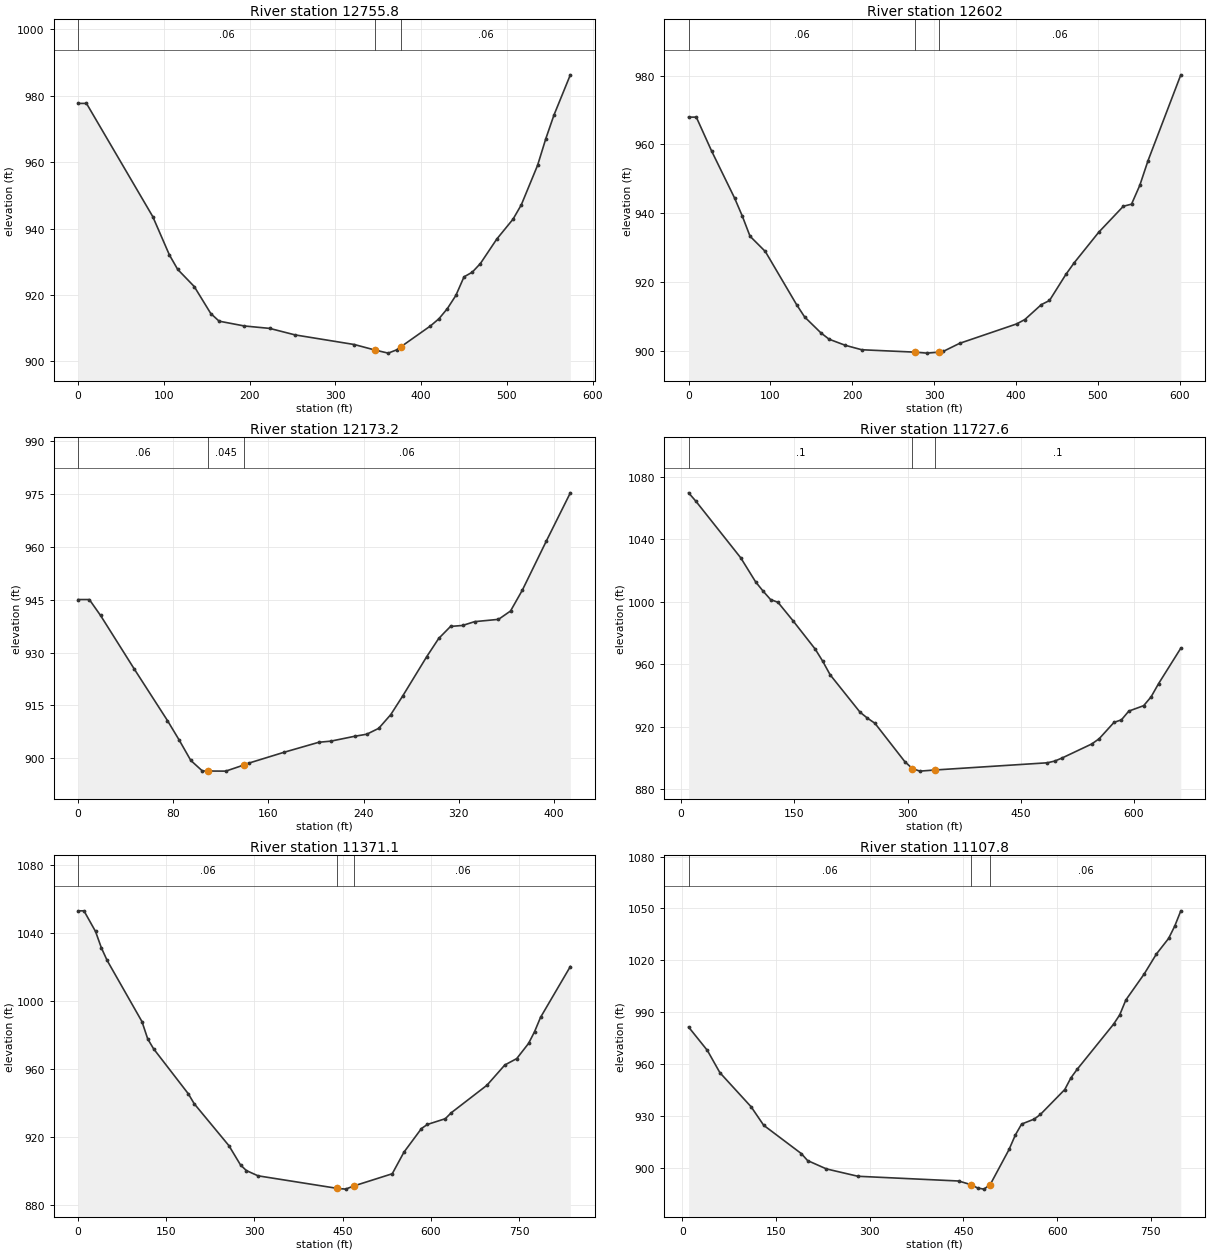
Type RM Length L Ch R = 1 ,12755.8 ,152.8,153.8,154.8
XS GIS Cut Line= 4
     1693342.285      207806.428     1693217.003      207927.289
     1692988.546      208064.362     1692897.164       208161.64
#Sta/Elev= 30
       0   977.7     9.7   977.7      87  943.61   106.4  932.06   116.1  927.69
   135.4  922.53   154.7  914.39   164.4   912.1   193.8  910.65   223.4  909.92
     253  907.96   322.1  905.06   346.6  903.37   361.6  902.47   371.4  903.45
   376.6  904.42   410.9  910.67   420.8  912.84   430.6  915.89   440.5  919.85
     450  925.45   459.6  926.85   469.1  929.46   488.2  936.83   507.2  942.84
   516.8  947.14   535.8  959.05   545.4  967.08   554.9  974.19     574  986.31
#Mann= 3 , 0 , 0
       0     .06       0   346.6    .045       0   376.6     .06       0
Bank Sta=346.6,376.6
XS Rating Curve= 0 ,0
Exp/Cntr=0.3,0.1

Type RM Length L Ch R = 1 ,12602   ,450.4,428.8,406.1
XS GIS Cut Line= 4
     1693243.911      207734.294     1693145.057      207805.469
      1692898.58      207935.957     1692803.679      208112.577
#Sta/Elev= 30
       0  967.93     9.4  967.93    28.1  958.09    56.2  944.42    65.6   939.2
      75  933.37    93.7  928.93   131.8  913.54   141.7  909.93   161.7  905.29
   171.6  903.47   191.5  901.69   211.5  900.41   276.1  899.72   291.1  899.43
   306.1  899.72   311.1  899.94     331  902.27   400.7  907.91   410.7  909.18
   430.8   913.5   440.8  914.71   460.8  922.27   470.9  925.63   500.9  934.51
     531  942.06     541  942.67   551.1  948.13   561.1  955.26   601.2  980.21
#Mann= 3 , 0 , 0
       0     .06       0   276.1    .045       0   306.1     .06       0
Bank Sta=276.1,306.1
XS Rating Curve= 0 ,0
Exp/Cntr=0.3,0.1

Type RM Length L Ch R = 1 ,12173.2 ,438.3,445.6,453
XS GIS Cut Line= 4
     1692724.033      207633.142     1692722.715      207708.272
     1692709.535      207834.806     1692650.222      208037.787
#Sta/Elev= 30
       0  945.01     9.4  945.01    18.8  940.52      47  925.43    75.1  910.72
    84.9  905.24    94.7  899.44   104.5  896.44   109.1  896.44   124.1  896.41
   139.1  898.12   143.6  898.69     173  901.74   202.4  904.59   212.4   904.9
   232.6  906.29   242.6  906.86   252.7  908.53   262.8  912.41   272.8  917.66
     293   928.8   303.1  933.98   313.1   937.4   323.2  937.67   333.3  938.75
   353.4   939.4   363.5  941.76   373.5  947.71   393.7  961.64   413.8  975.24
#Mann= 3 , 0 , 0
       0     .06       0   109.1    .045       0   139.1     .06       0
Bank Sta=109.1,139.1
XS Rating Curve= 0 ,0
Exp/Cntr=0.3,0.1

Type RM Length L Ch R = 1 ,11727.6 ,347.7,356.5,365.3
XS GIS Cut Line= 4
     1692517.098       207302.31     1692376.066      207480.248
     1692264.031      207701.682     1692180.993      207869.075
#Sta/Elev= 30
     9.9 1069.68    19.7 1064.21      79 1028.06    98.7 1012.69   108.6 1006.77
   118.5 1001.37   128.3  999.61   148.1  987.89   177.7  969.62   187.6   961.9
   197.4  953.24     237   929.3   246.9  925.45   256.8  922.17   296.5  897.55
   306.5  893.15   316.4  891.55   336.2  892.27     485  896.88   494.9  897.96
   504.7  899.94   544.1  908.94   553.9  912.28   573.6  922.75   583.4  924.37
   593.2  929.97   612.9  933.45   622.7  939.07   632.6  947.52   662.1  970.25
#Mann= 3 , 0 , 0
     9.9      .1       0   306.5    .045       0   336.2      .1       0
Bank Sta=306.5,336.2
XS Rating Curve= 0 ,0
Exp/Cntr=0.3,0.1

Type RM Length L Ch R = 1 ,11371.1 ,259.4,263.3,267.2
XS GIS Cut Line= 4
     1692405.626      207205.752     1692120.925      207317.787
     1691906.082      207494.407     1691665.694       207574.18
#Sta/Elev= 30
       0 1053.19     9.9 1053.19    29.6 1041.04    39.5 1031.43    49.3 1024.03
   108.6  988.04   118.4  977.83   128.3  972.09   187.5  945.57   197.4  939.79
   256.6  915.06   276.3  903.74   286.2  900.46     306  897.37   439.9  890.04
   454.9  889.54   469.9   891.5   534.4  898.58   554.3  911.27   584.1  925.18
   594.2  927.58   624.6  930.94   634.7  934.42   695.5  950.62   725.9  962.53
   746.2   966.3   766.4  975.26   776.6  982.19   786.7  990.55   837.4 1020.45
#Mann= 3 , 0 , 0
       0     .06       0   439.9    .045       0   469.9     .06       0
Bank Sta=439.9,469.9
XS Rating Curve= 0 ,0
Exp/Cntr=0.3,0.1

Type RM Length L Ch R = 1 ,11107.8 ,318.4,317.3,316.2
XS GIS Cut Line= 4
     1692259.321      207102.944     1692080.065      207122.715
     1691746.597      207311.197      1691554.16      207445.639
#Sta/Elev= 30
      10   981.4    40.1  967.84    60.1     955   110.2  935.22   130.2  924.58
   190.4  908.21   200.5  904.16   230.7  899.32   281.1  895.07   442.4  892.33
   462.6  890.15   472.7  888.28   482.8  887.63   492.8  890.19   523.1  910.57
   533.2  918.98   543.2  925.27   563.4  928.16   573.2  930.81   612.3  945.25
   622.1  951.99   631.9  956.85   690.5  983.09   700.3  988.46   710.1  997.07
   739.5 1012.13     759 1023.65   778.6  1032.7   788.4 1039.82   798.1 1048.65
#Mann= 3 , 0 , 0
      10     .06       0   462.6    .045       0   492.8     .06       0
Bank Sta=462.6,492.8
XS Rating Curve= 0 ,0
Exp/Cntr=0.3,0.1

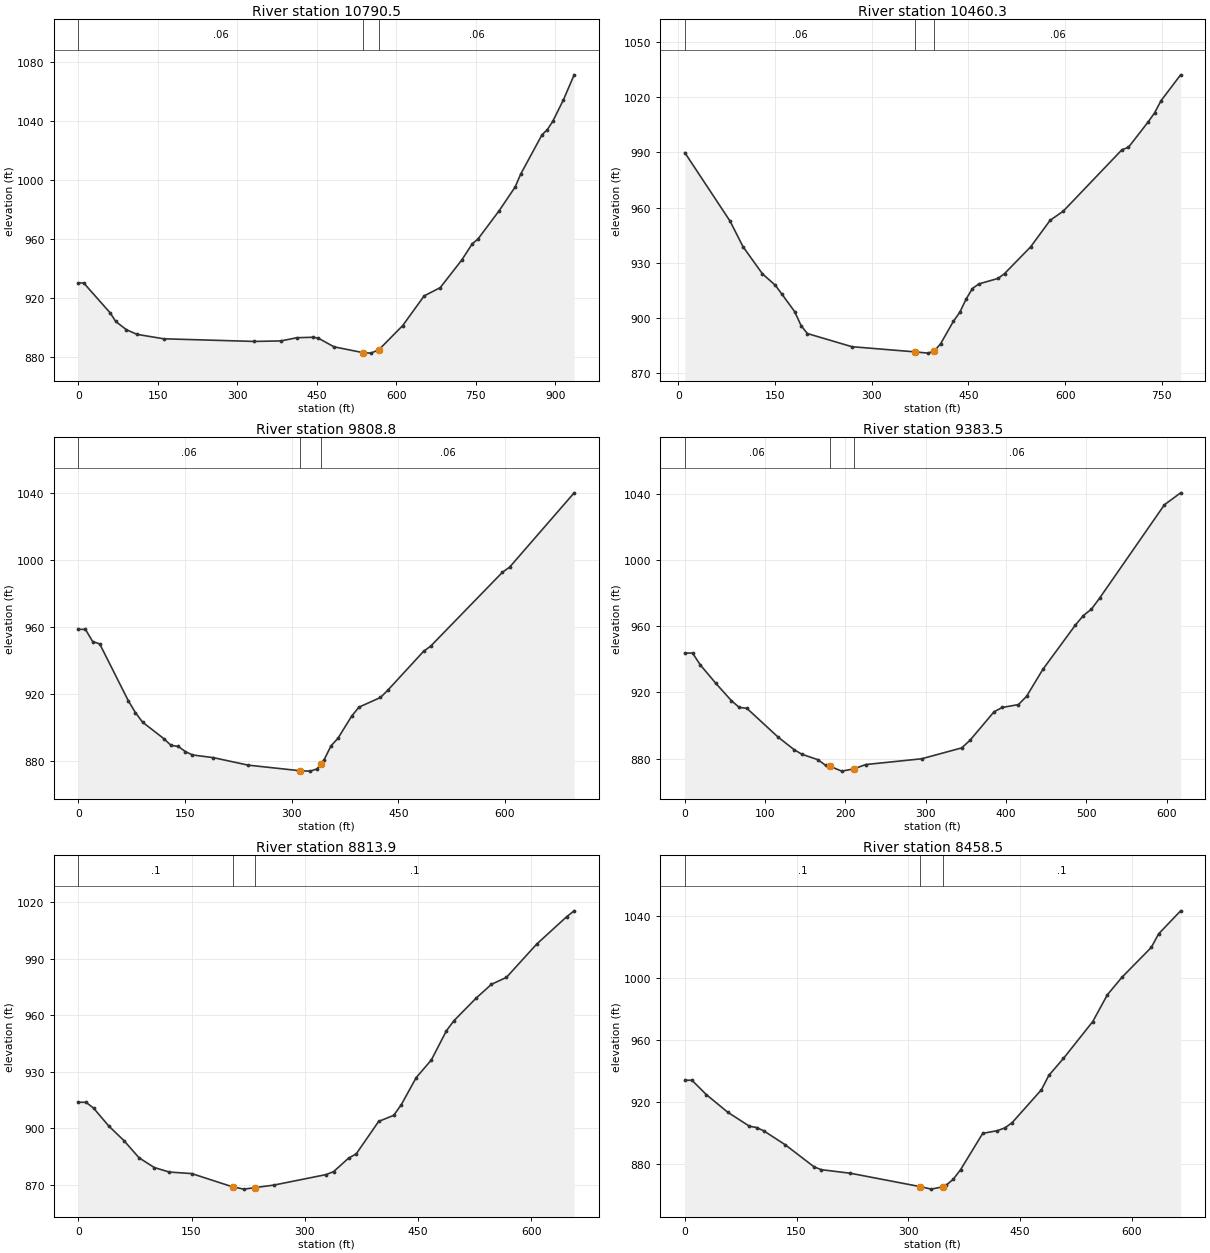
Type RM Length L Ch R = 1 ,10790.5 ,329.5,330.2,330.9
XS GIS Cut Line= 4
     1692191.599       207024.55     1691781.353       206922.73
     1691622.198      207025.538     1691380.005      207240.052
#Sta/Elev= 30
       0  930.23    10.1  930.23    60.4  909.79    70.4  904.14    90.6   898.5
   110.7  895.33     161  892.32   332.1  890.52   382.4  890.88   412.6  893.04
   442.6  893.36   452.6   892.8   482.5  886.87   537.3   882.9   552.3  882.58
   567.3  884.93   612.2  901.32   652.6  921.44   682.9  927.04   723.4  945.71
   743.6  956.93   753.7  959.85   794.2   979.3   824.5  995.48   834.6 1004.01
     875 1030.83   885.1 1034.34   895.3 1039.96   915.5 1054.63   935.7 1071.55
#Mann= 3 , 0 , 0
       0     .06       0   537.3    .045       0   567.3     .06       0
Bank Sta=537.3,567.3
XS Rating Curve= 0 ,0
Exp/Cntr=0.3,0.1

Type RM Length L Ch R = 1 ,10460.3 ,660.9,651.4,642
XS GIS Cut Line= 4
     1691779.376      206511.495     1691645.923      206633.086
      1691382.97      206788.288     1691280.162      207063.103
#Sta/Elev= 30
      10  989.92    80.2  952.73   100.3  938.85   130.4  924.11   150.4  917.89
   160.5  913.14   180.5  903.54   190.4  895.96   200.2  891.65   269.2  884.51
   367.7  881.67   387.4  881.01   397.2  882.14   407.1  886.22   426.8  898.33
   436.6  903.14   446.5  910.39   456.3  916.11   466.2   918.6     496  921.58
   506.1  924.21   546.6  938.75   576.9  953.19   597.2  958.12   688.2  991.46
   698.4  992.84   728.7  1006.5   738.8 1011.46   748.9 1018.14   779.3 1032.18
#Mann= 3 , 0 , 0
      10     .06       0   367.7    .045       0   397.2     .06       0
Bank Sta=367.7,397.2
XS Rating Curve= 0 ,0
Exp/Cntr=0.3,0.1

Type RM Length L Ch R = 1 ,9808.8  ,429.4,425.4,421.3
XS GIS Cut Line= 4
     1691262.038      206027.823      1691186.47      206180.717
     1691072.238      206361.731     1690885.952      206613.041
#Sta/Elev= 30
       0   958.5      10   958.5    20.1  951.24    30.1  949.78    70.2  915.93
    80.3  908.76    90.3  903.07   120.4  893.14   130.4  889.16   140.5  888.56
   150.5  885.49   160.5  883.46     190  881.84   238.7  877.38   311.2  874.05
   326.2  873.79   335.9  875.13   341.2  878.08   345.7  880.58   355.4  888.89
   365.1  893.39   384.6  906.74   394.7  912.01     425  917.81     435     922
   485.5  945.33   495.6  948.48   596.5   992.6   606.6  995.65   697.4 1040.07
#Mann= 3 , 0 , 0
       0     .06       0   311.2    .045       0   341.2     .06       0
Bank Sta=311.2,341.2
XS Rating Curve= 0 ,0
Exp/Cntr=0.3,0.1

Type RM Length L Ch R = 1 ,9383.5  ,571.2,569.5,567.8
XS GIS Cut Line= 4
     1690882.437      205840.878      1690840.26      205948.959
     1690766.448      206144.032     1690650.459      206412.915
#Sta/Elev= 30
       0  943.79     9.7  943.79    19.3  936.66    38.7   925.5      58   915.1
    67.7  911.03    77.3  910.45     116  893.17   135.9   885.6   145.8  882.73
   165.7  879.47   175.6  875.97   180.5  875.51   195.5  872.56   210.5  873.91
   225.3  876.53   294.8     880   344.8  886.58   354.9  891.06   385.2  908.43
   395.3  910.97   415.5  912.72   425.6  917.72   445.8  933.92   486.2  960.58
   496.3  966.43   506.3  970.26   516.4  976.85   597.2 1033.26   617.4 1040.47
#Mann= 3 , 0 , 0
       0     .06       0   180.5    .045       0   210.5     .06       0
Bank Sta=180.5,210.5
XS Rating Curve= 0 ,0
Exp/Cntr=0.3,0.1

Type RM Length L Ch R = 1 ,8813.9  ,339,355.4,371.9
XS GIS Cut Line= 4
     1690384.211      205644.707     1690312.157      205715.003
     1690247.133      205943.467     1689999.338      206143.812
#Sta/Elev= 30
       0   913.8    10.1   913.8    20.1  910.75    40.3  901.22    60.4  893.48
    80.5  884.31   100.7  879.16   120.5  876.77   150.2  875.97   204.4  868.92
   219.4  867.71   234.4  868.53     259  869.85   328.3  875.43   338.2  877.01
   358.1  884.18   368.1  886.39   397.9  903.65   417.9  906.88   427.8  912.49
   447.7  926.93   467.7  936.25   487.6  951.72   497.5  957.04   527.4  969.22
   547.3   976.4   567.2  980.09   607.1  997.68   646.9 1012.25   656.9  1015.4
#Mann= 3 , 0 , 0
       0      .1       0   204.4    .045       0   234.4      .1       0
Bank Sta=204.4,234.4
XS Rating Curve= 0 ,0
Exp/Cntr=0.3,0.1

Type RM Length L Ch R = 1 ,8458.5  ,624.1,626.2,628.2
XS GIS Cut Line= 4
     1690280.524       205479.51     1690138.174      205609.559
     1689900.923       205730.82     1689702.336      205787.057
#Sta/Elev= 30
       0  934.26     9.6  934.26    28.9     925    57.8  913.56    86.8  904.59
    96.4  903.75     106  901.61     135  892.58   173.5   878.4   183.2  876.55
   222.4  874.24     316  865.62     331     864     346  865.47   350.7  866.39
   360.6  870.48   370.4  876.65     400  899.98   419.8  901.74   429.7   903.5
   439.5  906.89   478.9  928.17   488.7  937.36   508.4  948.34   547.7   972.1
   567.4  989.44     587 1000.73   626.3 1019.95   636.2 1028.73   665.7 1043.56
#Mann= 3 , 0 , 0
       0      .1       0     316    .045       0     346      .1       0
Bank Sta=316,346
XS Rating Curve= 0 ,0
Exp/Cntr=0.3,0.1

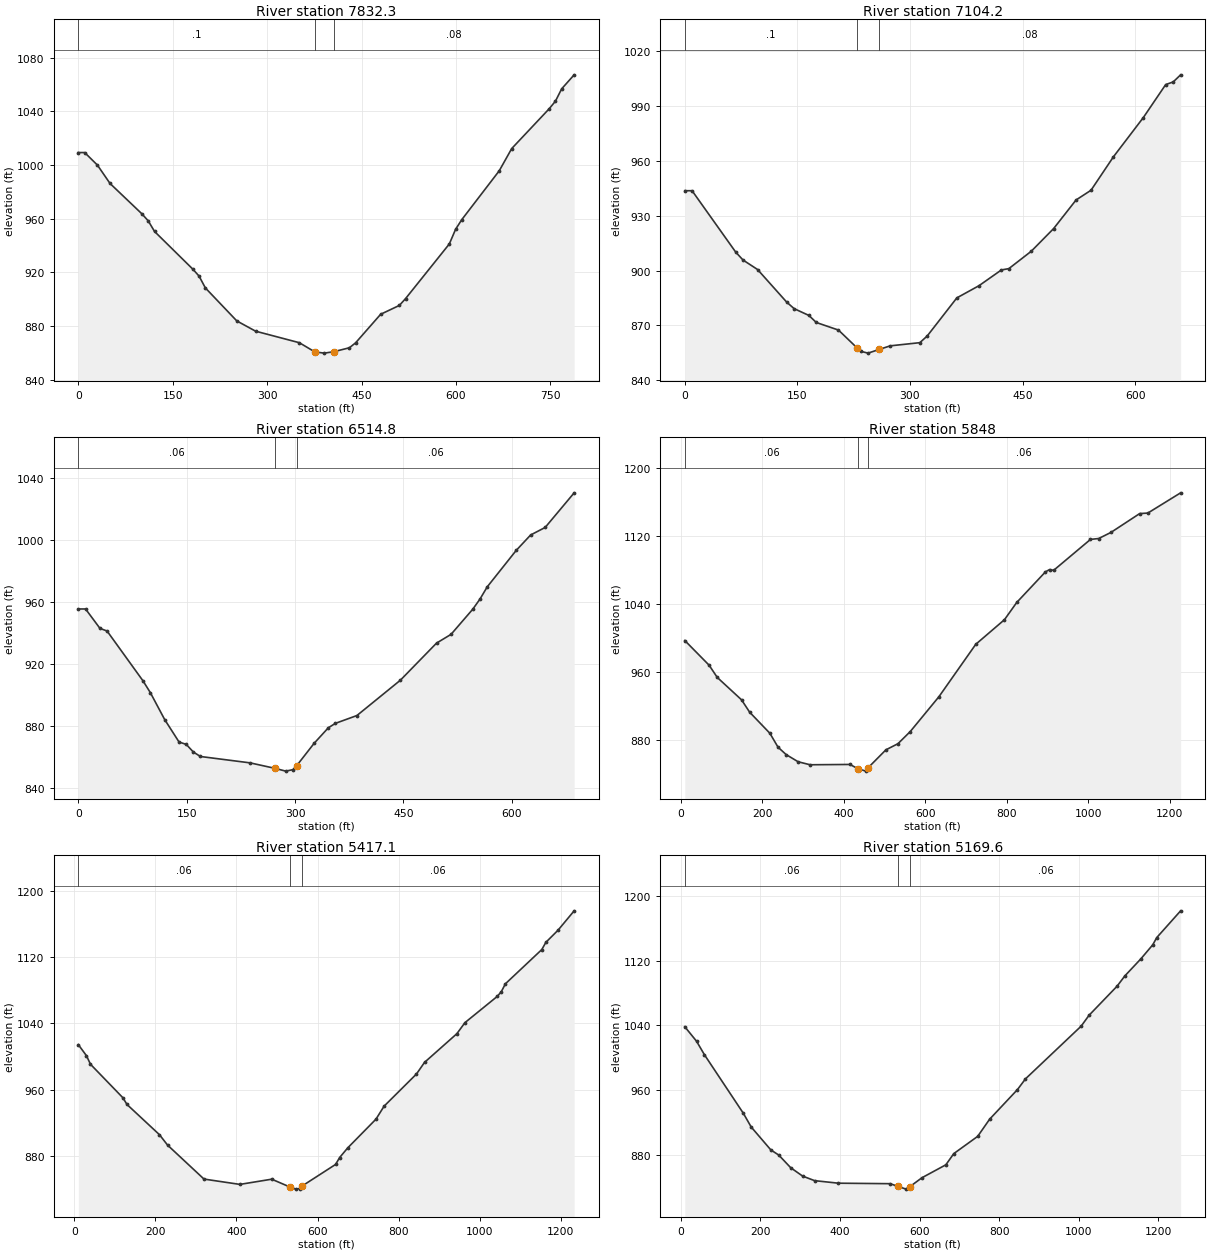
Type RM Length L Ch R = 1 ,7832.3  ,741.5,728.1,714.8
XS GIS Cut Line= 4
     1690162.778      205017.311     1689943.101      205048.944
     1689693.549      205147.359     1689440.481      205303.769
#Sta/Elev= 30
       0 1009.27    10.1 1009.27    30.3  999.93    50.4  986.22   100.9  963.66
     111  958.41   121.1  950.47   181.6  922.54   191.7   917.3   201.8  908.43
   251.7  883.86   281.6  876.19   351.1   867.6   375.8  860.73   390.8  859.84
   405.8  860.89   430.6  863.83   440.5  867.51   480.3  888.79     510  895.38
   519.9  900.48   589.4  941.19   599.3  952.05   609.2  959.31   668.7   995.7
   688.5 1012.25     748 1041.88     758 1047.59   767.9 1056.77   787.7 1067.18
#Mann= 3 , 0 , 0
       0      .1       0   375.8    .045       0   405.8     .08       0
Bank Sta=375.8,405.8
XS Rating Curve= 0 ,0
Exp/Cntr=0.3,0.1

Type RM Length L Ch R = 1 ,7104.2  ,587.9,589.4,590.8
XS GIS Cut Line= 4
     1689514.204       204364.55     1689443.456      204480.497
     1689315.717      204702.567     1689180.384      204934.713
#Sta/Elev= 30
       0  943.56     9.7  943.56    67.9  910.02    77.6  905.73      97  900.54
   135.8  882.74   145.7  879.19   165.4  875.48   175.2  871.64   204.8  867.49
   229.2   857.9   234.4   855.9   244.2  854.91   259.2  856.95   273.8  858.89
   313.2  860.62     323  864.25   362.5  885.06     392  891.71   421.9  900.32
   431.8  901.03   461.7  910.53   491.5  922.91   521.4  938.52   541.3  943.82
   571.2   962.1     611  983.49   640.8  1001.5   650.8 1002.94   660.7 1006.82
#Mann= 3 , 0 , 0
       0      .1       0   229.2    .045       0   259.2     .08       0
Bank Sta=229.2,259.2
XS Rating Curve= 0 ,0
Exp/Cntr=0.3,0.1

Type RM Length L Ch R = 1 ,6514.8  ,652.9,666.8,680.8
XS GIS Cut Line= 4
      1689021.29      204052.736     1688958.024      204188.057
     1688829.733      204374.343     1688613.571      204597.534
#Sta/Elev= 30
       0  955.44      10  955.44    29.9  942.94    39.8   941.2    89.6     909
    99.6  901.52   119.5   884.1   139.4   869.6   149.4  868.06   159.2  863.14
     169  860.25   237.9  856.13   272.1  852.61   287.1  850.81   296.9  851.74
   302.1  854.25   326.4  868.78   346.1  878.81   355.9  881.65   385.6  886.68
   445.7  909.45   495.8  933.41   515.9  939.06     546  955.31     556  961.87
     566  969.72   606.1  993.24   626.1 1003.19   646.2 1008.05   686.3 1030.38
#Mann= 3 , 0 , 0
       0     .06       0   272.1    .045       0   302.1     .06       0
Bank Sta=272.1,302.1
XS Rating Curve= 0 ,0
Exp/Cntr=0.3,0.1

Type RM Length L Ch R = 1 ,5848    ,417.5,430.8,444.2
XS GIS Cut Line= 4
     1688941.376      203715.069     1688683.037      203722.099
     1688428.212      203792.395     1688043.339      204381.128
#Sta/Elev= 30
     9.9  997.04    69.6  968.05    89.5  953.75   149.1  927.45     169  912.93
   218.7  888.14   238.6  871.86   258.4  863.22   287.8  854.77   317.2  851.23
   415.1  851.59   434.7  846.57   454.2  843.76  459.13  847.49   503.2  868.74
   532.8  875.96     563  890.22   633.3   931.1   723.7  992.64   794.1 1021.52
   824.2 1041.74   894.6 1077.63   904.6  1080.3   914.7 1079.42  1005.1 1115.73
  1025.2 1116.76  1055.3 1123.93  1125.7 1146.01  1145.8 1146.65  1226.2 1170.39
#Mann= 3 , 0 , 0
     9.9     .06       0   434.7    .045       0  459.13     .06       0
#XS Ineff= 2 , 0
       0     405                       0
Permanent Ineff=
       F       F
Bank Sta=434.7,459.13
XS Rating Curve= 0 ,0
Exp/Cntr=0.3,0.1

Type RM Length L Ch R = 1 ,5417.1  ,242.3,247.5,252.7
XS GIS Cut Line= 4
     1688954.509      203586.363     1688679.035      203444.013
     1688379.835      203318.797     1687902.698      202957.649
#Sta/Elev= 30
      10 1014.13      30 1000.82      40  990.46     120  949.98     130  941.94
   210.1  905.45   230.1  892.88   319.9   851.9   408.4  845.48     487  851.76
     531  842.49     546  839.77   555.8  840.45     561  843.25   644.4  869.56
   654.4  877.86   674.3  889.51   744.1  924.25   764.1   939.9   843.9   978.7
   863.8  992.74   943.6 1027.38   963.5 1040.71  1043.3 1072.41  1053.3  1078.2
  1063.3  1087.6    1153 1128.88    1163 1137.59  1192.9 1152.18  1232.8 1175.63
#Mann= 3 , 0 , 0
      10     .06       0     531    .045       0     561     .06       0
#XS Ineff= 2 , 0
       0     487                       0
Permanent Ineff=
       F       F
Bank Sta=531,561
XS Rating Curve= 0 ,0
Exp/Cntr=0.3,0.1

Type RM Length L Ch R = 1 ,5169.6  ,380.9,387.9,394.8
XS GIS Cut Line= 4
     1689032.762       203490.12     1688872.837      203360.072
     1688500.266      203073.614     1687962.498      202855.695
#Sta/Elev= 30
     9.8 1038.24    39.3 1020.33    58.9  1003.8     157  931.12   176.7  914.17
   226.1  885.81   246.1   879.4   276.1  863.75   306.1  853.39   336.1  847.77
   396.1  844.62   526.1  844.01   546.1  840.62   566.1  837.28   576.1  840.52
   606.1   851.4   666.1  867.38   686.1  881.26   746.1  902.57   776.1  923.79
   846.2  960.51   866.2   973.7  1006.2 1038.94  1026.2 1052.48  1096.3 1088.29
  1116.3 1101.26  1156.3 1122.22  1186.3 1139.67  1196.3 1148.57  1256.3 1181.68
#Mann= 3 , 0 , 0
     9.8     .06       0   546.1    .045       0   576.1     .06       0
Bank Sta=546.1,576.1
XS Rating Curve= 0 ,0
Exp/Cntr=0.3,0.1

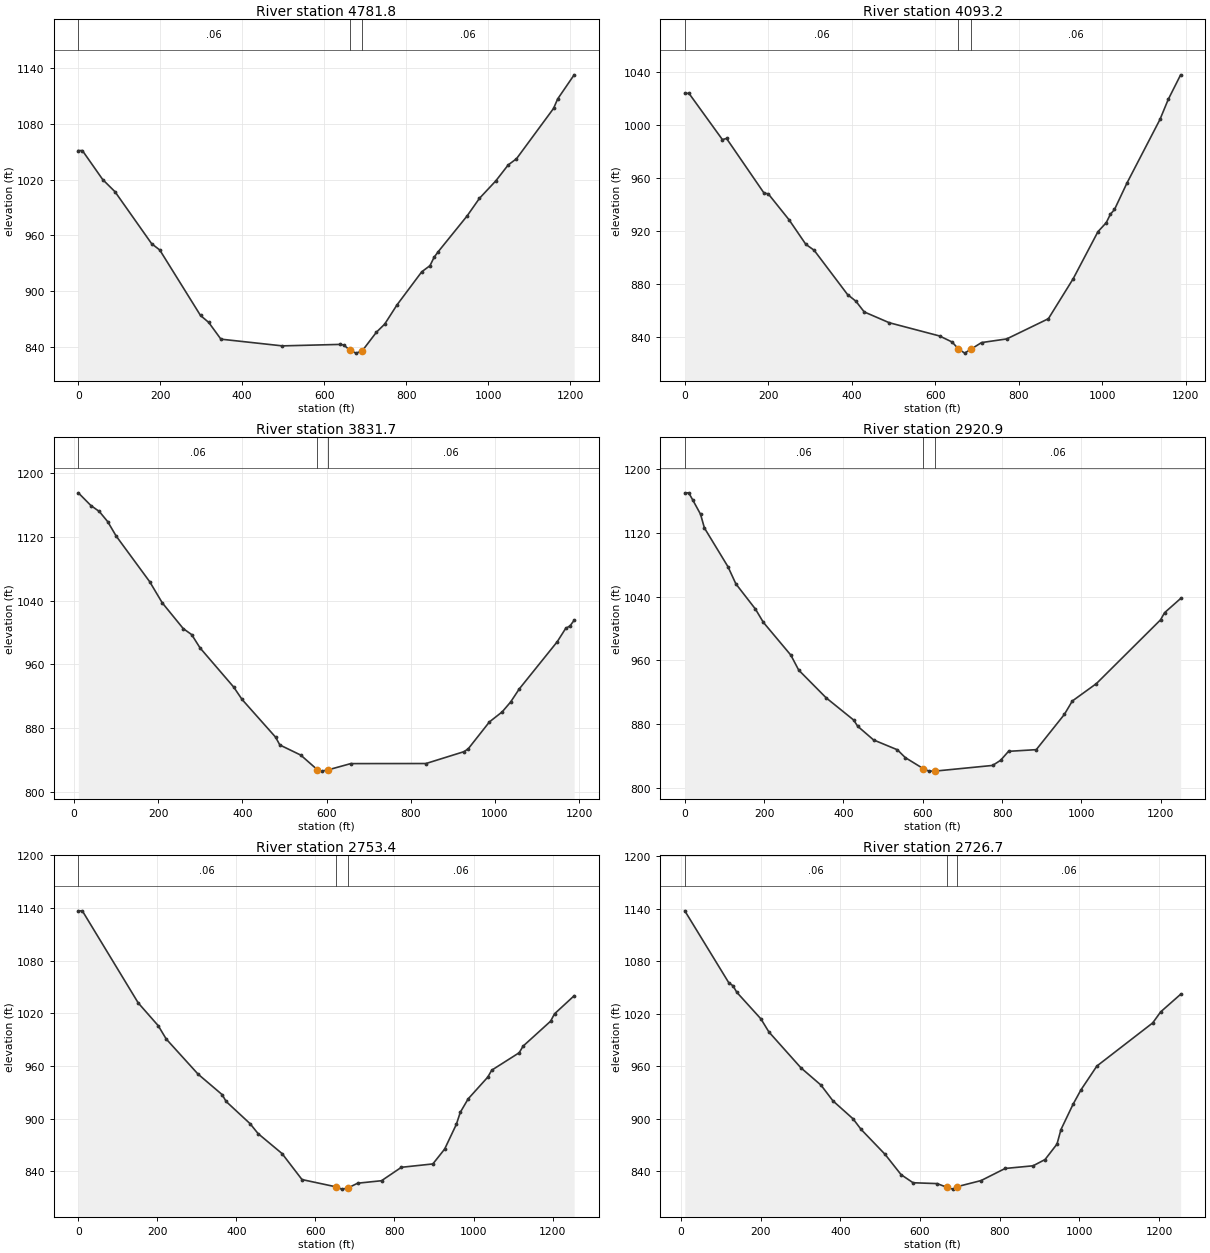
Type RM Length L Ch R = 1 ,4781.8  ,678.4,688.5,698.7
XS GIS Cut Line= 4
      1689122.39      203439.155     1689008.158      203121.064
     1688781.452      202767.824     1688412.396       202505.97
#Sta/Elev= 30
       0 1051.24     9.9 1051.24    59.6 1020.05    89.5 1007.03   178.9  951.21
   198.8  944.39   298.2  874.07   318.1  866.67     348  848.62   497.9   841.4
   637.8  842.97   647.8   842.4   662.8  836.69   677.8  833.61   692.8  835.99
   727.7  856.16   747.7  864.75   777.8  885.43   838.2     921   858.3  927.59
   868.3  936.54   878.4   942.6   948.8  980.95   978.9  999.84  1019.2  1018.8
  1049.3 1035.86  1069.4 1042.42  1159.9 1096.52    1170 1106.75  1210.2 1132.62
#Mann= 3 , 0 , 0
       0     .06       0   662.8    .045       0   692.8     .06       0
Bank Sta=662.8,692.8
XS Rating Curve= 0 ,0
Exp/Cntr=0.3,0.1

Type RM Length L Ch R = 1 ,4093.2  ,265.1,261.5,257.8
XS GIS Cut Line= 4
     1689419.392      203284.503     1689470.969       202747.18
     1689453.282      202466.154     1689159.296      202247.631
#Sta/Elev= 30
       0 1023.75      10 1023.75      90  988.89     100  989.72   189.9  948.47
   199.9  947.97   249.9  928.31   289.9  909.88   309.9  905.36   389.9  871.97
   409.8  866.98   429.8  858.87   489.8  850.72   610.2  840.74   640.4  836.16
   655.5  830.94   670.5  827.79   685.5  830.78   710.8  835.75   771.1   838.5
   870.9  853.74   930.3  883.89   989.7  919.43  1009.5  926.17  1019.4  932.52
  1029.3  936.14    1059     956  1138.2 1004.06    1158 1019.16  1187.7 1037.73
#Mann= 3 , 0 , 0
       0     .06       0   655.5    .045       0   685.5     .06       0
Bank Sta=655.5,685.5
XS Rating Curve= 0 ,0
Exp/Cntr=0.3,0.1

Type RM Length L Ch R = 1 ,3831.7  ,942.9,910.8,878.7
XS GIS Cut Line= 4
     1690168.002      202974.564     1689742.708      202695.136
     1689670.654       202406.92     1689391.274      202145.701
#Sta/Elev= 30
      10 1175.59    39.9  1159.6    59.9 1152.14    79.8 1139.39    99.8  1121.4
   179.6 1063.95   209.5 1037.38   259.4 1005.02   279.4  997.48   299.3  980.77
   379.2  931.63   399.1  916.07   478.9   868.6   488.9  858.86   538.6  846.16
   578.2  827.73   588.1  826.01   603.1  827.52   657.4  835.46   836.2  835.56
   926.7  850.48   936.8  854.16   987.1  887.88  1017.3  900.42  1037.5  912.89
  1057.6  929.04  1148.2  988.56  1168.3 1005.35  1178.4 1008.34  1188.4 1015.52
#Mann= 3 , 0 , 0
      10     .06       0   578.2    .045       0   603.1     .06       0
Bank Sta=578.2,603.1
XS Rating Curve= 0 ,0
Exp/Cntr=0.3,0.1

Type RM Length L Ch R = 1 ,2920.9  ,175.5,167.5,159.6
XS GIS Cut Line= 4
     1690630.249      201662.412     1690217.257        201766.1
     1689764.431      201893.122     1689428.179       202003.35
#Sta/Elev= 30
       0 1169.95     9.9 1169.95    19.8 1161.23    39.6 1143.24    49.5 1125.88
   108.9 1077.36   128.7 1055.98   178.2 1024.25   198.1  1007.7   267.4  966.62
   287.2   947.9   356.5  913.12   425.8  885.33   435.8  877.62   475.8  860.47
   535.9  848.11   555.9   838.3   600.9  824.58   615.9  821.37   630.9   821.4
     776   828.5     796  834.88   816.1  846.15   886.1  848.27   956.8  892.34
     977  909.22  1037.7  931.02  1199.4 1010.87  1209.5  1019.8    1250  1037.6
#Mann= 3 , 0 , 0
       0     .06       0   600.9    .045       0   630.9     .06       0
Bank Sta=600.9,630.9
XS Rating Curve= 0 ,0
Exp/Cntr=0.3,0.1

Type RM Length L Ch R = 1 ,2753.4  ,25.8,26.7,27.6
XS GIS Cut Line= 4
     1690566.715      201533.103     1690017.315      201618.221
     1689803.967      201786.247     1689423.698      201980.803
#Sta/Elev= 30
       0 1136.76    10.1 1136.76   151.6 1031.81   202.2 1005.88   222.4  990.73
   303.2  950.62   363.9  927.38     374  919.56   434.7  894.25   454.9  882.95
   515.5  860.24     566   830.6   651.6  822.36   666.6  819.71   681.6  820.89
   706.8  826.46   767.2  829.29   817.5  844.58   897.1  848.41   926.9   865.3
   956.7  893.63   966.6  907.28   986.5  922.56  1036.1  947.32  1046.1  955.22
  1115.6  975.09  1125.5  982.63  1195.1 1011.02    1205 1019.41  1254.7 1040.01
#Mann= 3 , 0 , 0
       0     .06       0   651.6    .045       0   681.6     .06       0
Bank Sta=651.6,681.6
XS Rating Curve= 0 ,0
Exp/Cntr=0.3,0.1

Type RM Length L Ch R = 1 ,2726.7  ,73.3,73,72.6
XS GIS Cut Line= 4
     1690560.082      201509.888     1690013.999      201593.901
      1689786.28      201758.611     1689419.276      201963.116
#Sta/Elev= 30
      10 1137.84   120.5 1055.51   130.6 1052.28   140.6 1044.64   200.9 1014.33
     221  999.35   301.4  958.32   351.6  938.61   381.7  920.57     432  900.09
   452.1  888.03   512.3  859.49   552.5  836.25   582.6  826.99   642.8  826.03
     668  821.73     683   819.7     693  822.49   753.3  829.51   813.5  843.32
   883.6  846.37   913.6  853.51   943.6  871.21   953.6  887.84   983.6  916.46
  1003.6  933.09  1043.6   960.4  1183.7 1009.72  1203.7 1022.37  1253.7 1042.44
#Mann= 3 , 0 , 0
      10     .06       0     668    .045       0     693     .06       0
Bank Sta=668,693
XS Rating Curve= 0 ,0
Exp/Cntr=0.3,0.1