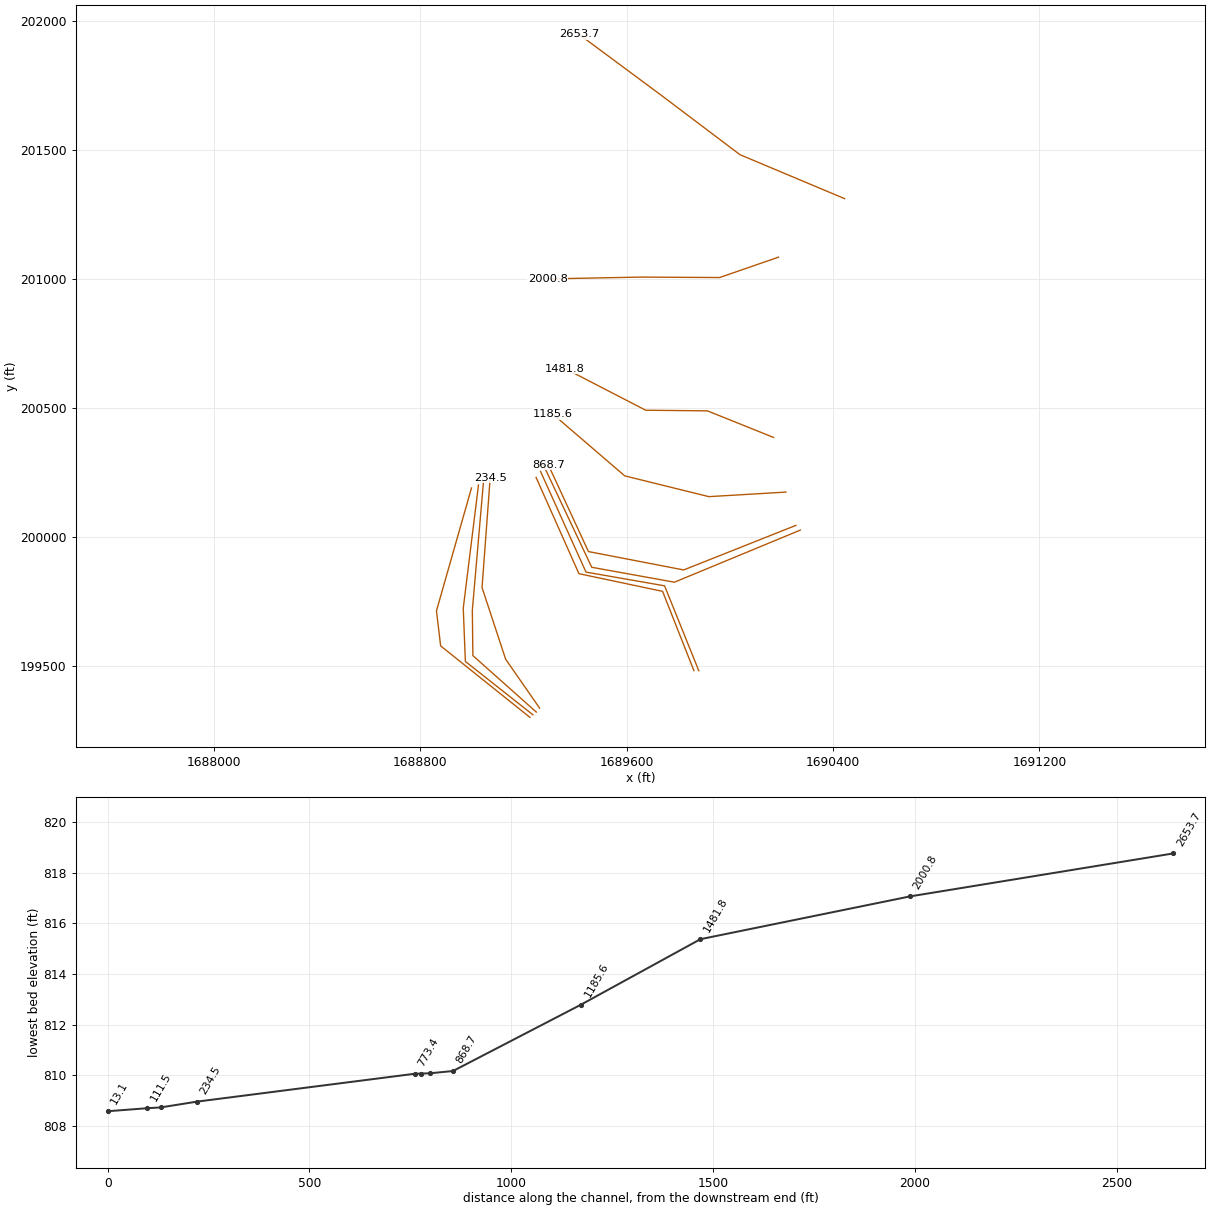
HEC-RAS study bncrk.prj: bncrk

--- bncrk.g01 (geometry) --- (continued)

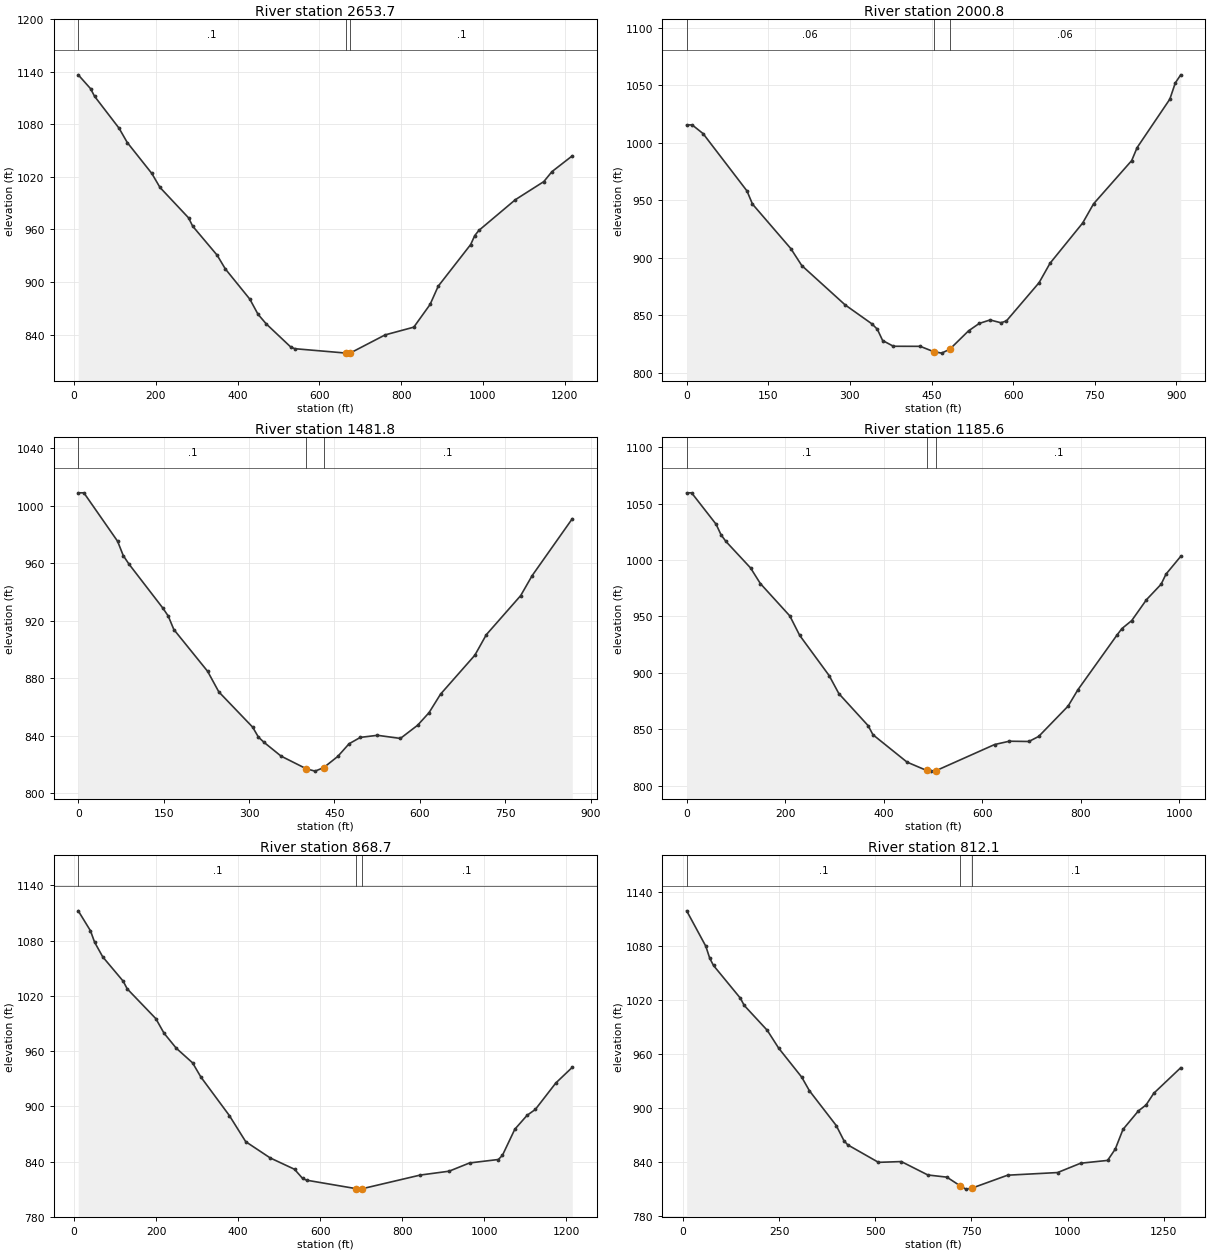
Type RM Length L Ch R = 1 ,2653.7  ,640.2,652.9,665.6
XS GIS Cut Line= 4
     1690445.117      201312.016     1690039.679      201482.376
     1689735.409      201712.029      1689415.96      201948.745
#Sta/Elev= 30
      10 1136.64      40  1120.9      50 1112.08   109.9 1075.62   129.9 1059.33
   189.9 1024.05   209.9 1008.06   279.9  973.27   289.9  963.81   349.8  930.63
   369.8  914.97   429.8  880.41   449.8  863.16   469.9  852.18   530.1  825.64
   540.1  823.81  664.61  818.85   670.5  818.77  675.98  819.04   760.8   839.6
   830.9  848.43   870.7  874.33   890.6  895.19   970.1  942.83     980     953
     990  958.89  1079.4  994.03    1149 1014.69  1168.9 1026.08  1218.6 1044.09
#Mann= 3 , 0 , 0
      10      .1       0  664.61    .045       0  675.98      .1       0
#XS Ineff= 2 , 0
       0     580             690       0
Permanent Ineff=
       F       F
Bank Sta=664.61,675.98
XS Rating Curve= 0 ,0
Exp/Cntr=0.3,0.1

Type RM Length L Ch R = 1 ,2000.8  ,519.1,519,518.9
XS GIS Cut Line= 4
     1690189.091      201085.347     1689960.627      201006.264
     1689654.837      201008.021     1689294.568      201000.991
#Sta/Elev= 30
       0 1015.53    10.1 1015.53    30.2 1007.94   110.8  958.11   120.9  946.69
   191.4  907.96   211.5  893.23   291.1  859.05   340.4  842.52   350.3  837.91
   360.1  828.04   379.9  823.04   429.2  822.98   453.6   818.4   468.6  817.07
   483.6  820.51     518  836.46   537.7   842.9   557.6  845.92   577.6  843.47
   587.6  845.07   647.7  878.39   667.7   895.2   727.7  930.21   747.7  946.88
   817.8   984.5   827.8  995.81   887.9 1037.92   897.9    1052   907.9 1059.08
#Mann= 3 , 0 , 0
       0     .06       0   453.6    .045       0   483.6     .06       0
Bank Sta=453.6,483.6
XS Rating Curve= 0 ,0
Exp/Cntr=0.3,0.1

Type RM Length L Ch R = 1 ,1481.8  ,300.6,296.2,292
XS GIS Cut Line= 4
     1690169.807      200386.532     1689913.177      200489.584
     1689674.217      200491.976     1689361.398      200653.658
#Sta/Elev= 30
       0 1008.94     9.9 1008.94    69.1  975.27      79  965.35    88.9  959.48
   148.2  928.98     158   923.3   167.9  913.87   227.2  884.82   246.9   870.5
   306.4  845.94   316.4  839.08   326.3  835.41   356.2  825.83   400.9  816.95
   415.9  815.38   430.9  817.77   455.8  825.59   475.7  834.42   495.6  838.86
   525.6  840.29   565.8  838.12     596  847.27   616.1  856.03   636.3   868.9
   696.6  896.01   716.7  910.26   777.1  937.46   797.2  951.34   867.7  990.92
#Mann= 3 , 0 , 0
       0      .1       0   400.9    .045       0   430.9      .1       0
Bank Sta=400.9,430.9
XS Rating Curve= 0 ,0
Exp/Cntr=0.3,0.1

Type RM Length L Ch R = 1 ,1185.6  ,316.1,316.8,317.5
XS GIS Cut Line= 4
      1690217.75      200174.716     1689919.037      200157.029
     1689592.812      200237.603     1689313.752      200477.359
#Sta/Elev= 30
       0 1059.58      10 1059.58    59.8 1031.69    69.8 1022.33    79.8 1016.42
   129.7  992.98   149.6  979.13   209.5  950.39   229.4  933.22   289.3  897.51
   309.1  881.48   368.4  853.14   378.3  845.05   447.5  820.77     487  813.44
   496.9  812.79   506.8  813.29   625.4  836.39   655.2  839.32   694.9  839.07
   714.8  843.56   774.5  870.45   794.4  884.93   873.9  933.52   883.9  939.24
   903.7  946.28   933.6  964.77   963.4  978.52   973.3  987.48  1003.2 1003.23
#Mann= 3 , 0 , 0
       0      .1       0     487    .045       0   506.8      .1       0
Bank Sta=487,506.8
XS Rating Curve= 0 ,0
Exp/Cntr=0.3,0.1

Type RM Length L Ch R = 1 ,868.7   ,56.5,56.7,56.9
XS GIS Cut Line= 4
     1690256.312      200045.618     1689821.352      199872.953
     1689452.296      199944.128     1689296.765      200280.233
#Sta/Elev= 30
      10 1112.47    39.8 1090.81    49.8 1078.45    69.7 1062.46   119.5 1036.08
   129.4  1027.7   199.1  995.38   219.1  979.54   248.9  963.26   288.8   947.3
   308.7  932.08   378.4  890.06   418.2  861.72   477.9  844.06   537.2  831.73
     557  821.73   566.9  819.85  688.24  810.62   695.5  810.17  700.95  810.49
   843.8  825.46   913.9  829.64   963.9  838.61    1034  842.35    1044  846.92
  1074.1  875.19  1104.1  890.38  1124.1  896.69  1174.1  925.47  1214.2  942.47
#Mann= 3 , 0 , 0
      10      .1       0  688.24    .045       0  700.95      .1       0
#XS Ineff= 2 , 0
       0     626             754       0
Permanent Ineff=
       F       F
Bank Sta=688.24,700.95
XS Rating Curve= 0 ,0
Exp/Cntr=0.3,0.1

Type RM Length L Ch R = 1 ,812.1   ,21.8,22,22.1
XS GIS Cut Line= 4
     1690273.446      200027.385     1689785.372      199825.426
     1689465.037      199883.278     1689277.042      200281.087
#Sta/Elev= 30
      10 1118.93    59.8 1079.56    69.8 1066.41    79.7 1058.27   149.5 1021.99
   159.5 1013.95   219.3  986.36   249.2  966.44     309  934.31   328.9  919.27
   398.6  880.67   418.6  863.89   428.5  859.21   508.3  839.81   567.7  840.66
   636.7  825.77     686  823.39   720.4  813.83   735.4  810.08   750.4  811.07
   843.9  825.54   973.7  828.47  1033.7  838.84  1103.7  841.95  1123.7  854.57
  1143.7  876.36  1183.7  896.87  1203.7  903.52  1223.7  916.46  1293.7  944.79
#Mann= 3 , 0 , 0
      10      .1       0   720.4    .045       0   750.4      .1       0
#XS Ineff= 2 , 0
       0     712             788       0
Permanent Ineff=
       F       F
Bank Sta=720.4,750.4
XS Rating Curve= 0 ,0
Exp/Cntr=0.3,0.1

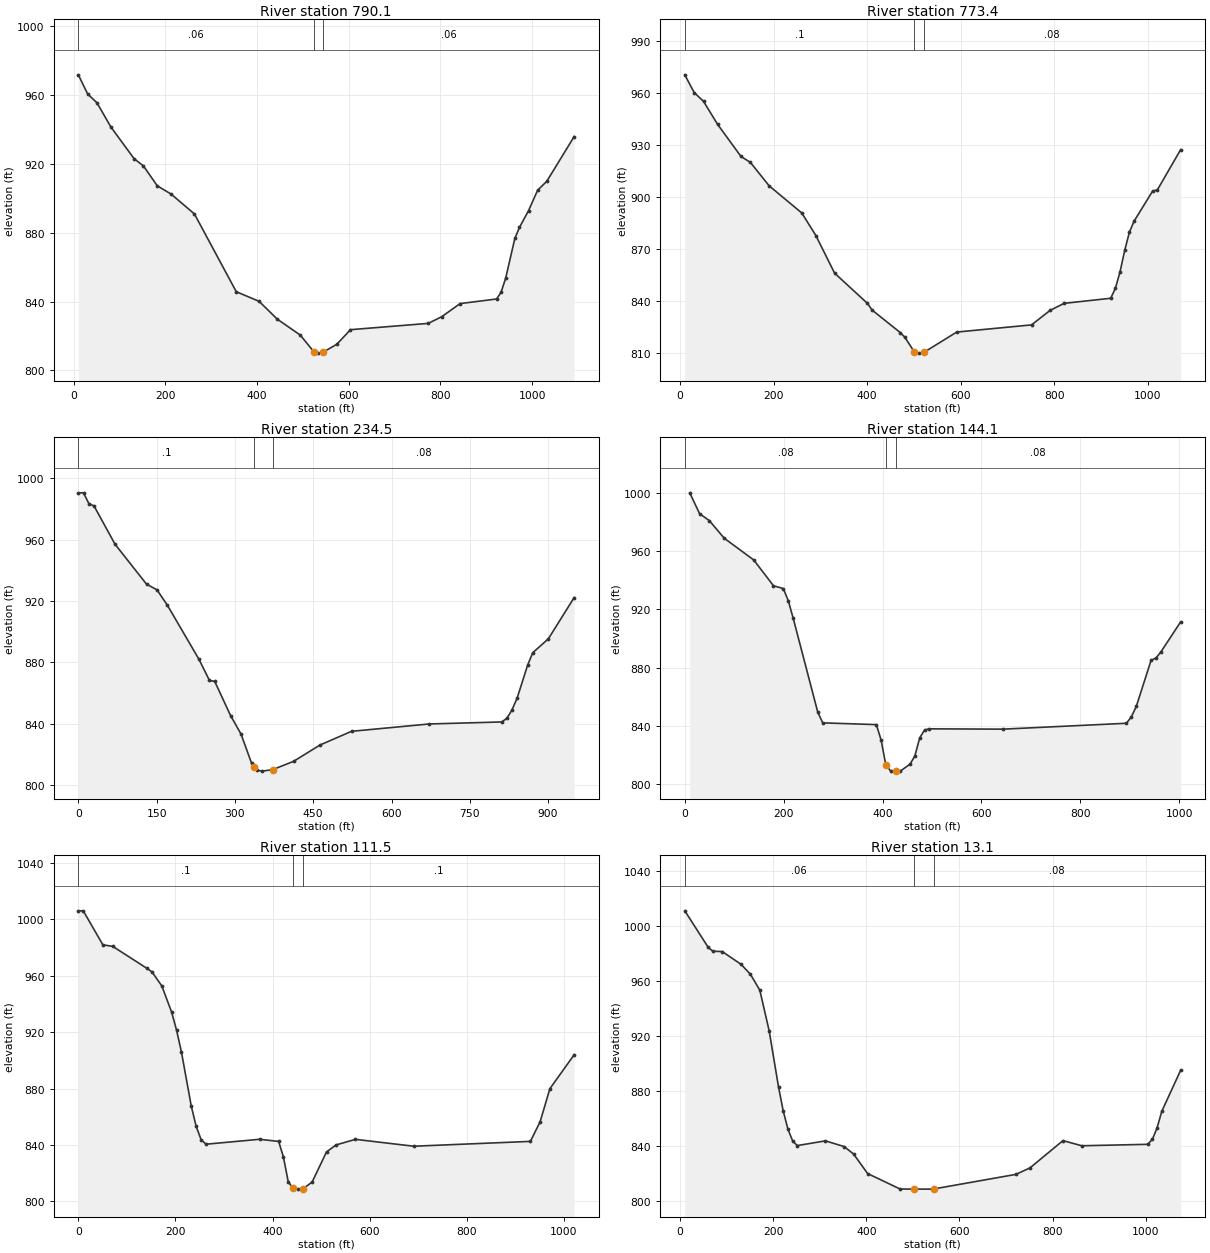
Type RM Length L Ch R = 1 ,790.1   ,17.4,16.7,16
XS GIS Cut Line= 4
     1689879.786      199482.588     1689747.235      199811.436
     1689442.757        199864.6     1689266.498      200254.726
#Sta/Elev= 30
    10.1  971.62    30.4  960.52    50.7   955.4      81  941.38   131.7  922.94
     152  918.77   182.3  907.19   212.7  902.35   263.4  890.85   354.6  845.73
   404.4  840.14   444.3  829.75   494.1  820.57   524.1  810.81     534  810.07
     544  810.59   573.9   815.2   603.8  823.68   773.2  827.33     803  831.23
   842.8  838.82   922.5  841.49   932.4  845.49   942.4   853.7   962.3  876.62
   972.3     883   992.2  892.79  1012.1  904.67    1032  909.81  1091.7  935.79
#Mann= 3 , 0 , 0
    10.1     .06       0   524.1    .045       0     544     .06       0
#XS Ineff= 2 , 0
       0     514             570       0
Permanent Ineff=
       F       F
Bank Sta=524.1,544
XS Rating Curve= 0 ,0
Exp/Cntr=0.3,0.1

Type RM Length L Ch R = 1 ,773.4   ,560,538.9,517.7
XS GIS Cut Line= 4
     1689860.894      199482.807     1689739.632      199789.915
      1689415.39      199858.454     1689249.315      200231.465
#Sta/Elev= 30
      10  970.31      30  960.12      50  955.05      80  941.83   130.1   923.3
   150.1  919.92   190.1  906.45   260.1  890.76   290.2  877.76   330.2  856.11
   400.5   838.7   410.5  834.83   470.8  821.86   480.8  819.07   500.9  810.62
   510.9  810.06     521  810.48   591.3  822.19   751.2  826.32   791.1  834.72
   820.9  838.72   920.5  841.66   930.5  847.42   940.4  856.87   950.4  869.27
   960.4  879.67   970.3  886.01  1010.1   903.4  1020.1     904  1069.9  927.22
#Mann= 3 , 0 , 0
      10      .1       0   500.9    .045       0     521     .08       0
#XS Ineff= 2 , 0
       0     486             560       0
Permanent Ineff=
       F       F
Bank Sta=500.9,521
XS Rating Curve= 0 ,0
Exp/Cntr=0.3,0.1

Type RM Length L Ch R = 1 ,234.5   ,96.5,90.4,84.3
XS GIS Cut Line= 4
     1689262.983      199337.357     1689131.177      199527.157
     1689039.792      199804.829     1689071.425      200230.122
#Sta/Elev= 30
       0  990.51      10  990.51    20.1  983.53    30.1  981.93    70.3  956.99
   130.6  930.94   150.7  927.21   170.8  917.07   231.1   881.9   251.2  868.12
   261.3  867.49   291.6  845.24   311.7  833.13   331.9  814.09     337  811.82
     342  809.59     352  808.96   372.2  809.91   412.5  815.37   462.9  825.98
   523.4  834.93   672.2  839.72     811  841.04   820.9  843.35   830.9  848.95
   840.8  856.71   860.6  877.95   870.5   886.2   900.3  895.18   949.9  922.19
#Mann= 3 , 0 , 0
       0      .1       0     337    .045       0   372.2     .08       0
#XS Ineff= 2 , 0
       0     326             432       0
Permanent Ineff=
       F       F
Bank Sta=337,372.2
XS Rating Curve= 0 ,0
Exp/Cntr=0.3,0.1

Type RM Length L Ch R = 1 ,144.1   ,32,32.5,33.1
XS GIS Cut Line= 4
      1689249.98       199322.16     1689004.316      199540.887
     1689002.161      199716.515      1689045.26       200213.23
#Sta/Elev= 30
      10 1000.23    29.9  985.89    49.8  981.06    79.7  969.02   139.5  954.02
   179.4   936.3   199.3  934.35   209.3  926.01   219.3  913.94   269.1  849.18
   279.1  841.94   387.5  840.73   397.2  830.09   406.7  812.92   416.7  808.73
   426.7  808.79   436.3  808.79   455.8  813.58   465.5  819.23   475.3  831.64
   485.1  837.04   494.8  837.83   644.2  837.62   893.5  841.66   903.4  846.08
   913.4  853.22   943.3  884.94   953.3  886.62   963.3  890.81  1003.1  911.41
#Mann= 3 , 0 , 0
       0     .08       0   406.7     .05       0   426.7     .08       0
Bank Sta=406.7,426.7
XS Rating Curve= 0 ,0
Exp/Cntr=0.3,0.1

Type RM Length L Ch R = 1 ,111.5   ,96.8,98.5,100.1
XS GIS Cut Line= 4
      1689237.05      199311.385     1688975.224       199518.26
     1688966.989      199725.046     1689026.032       200201.88
#Sta/Elev= 30
       0 1006.02    10.1 1006.02    50.6  981.89    70.8  980.84   141.6  965.15
   151.7  962.69   171.9  952.79   192.1  934.24   202.2   921.5   212.3  906.02
   232.6  867.53   242.7  853.15   252.8  843.83   262.9  840.55   373.1  844.04
   412.5  842.53   422.4  831.42   432.2  814.05   441.9  809.26   451.9   808.7
   461.9  808.72   481.5  813.74   511.1  835.07   530.8  840.04   570.7     844
   690.8  839.12     931  842.55     951  856.48   971.1  879.92  1021.1  903.98
#Mann= 3 , 0 , 0
       0      .1       0   441.9    .045       0   461.9      .1       0
Bank Sta=441.9,461.9
XS Rating Curve= 0 ,0
Exp/Cntr=0.3,0.1

Type RM Length L Ch R = 1 ,13.1    ,17.2,13.1,8.9
XS GIS Cut Line= 4
     1689225.198      199301.688     1688879.329      199578.598
     1688863.167       199714.36     1688998.929      200190.603
#Sta/Elev= 30
    10.1 1011.06    60.4  984.48    70.5  981.64    90.6  981.43   130.9  972.13
     151  964.93   171.2  953.35   191.3  923.73   211.5  882.71   221.5  865.41
   231.6  852.22   241.7  843.64   251.7  840.27   312.2   843.7   352.4  839.52
   372.6  834.13   402.8   819.9   472.4  808.68   501.7   808.6   540.7  808.58
  544.36  808.69   721.3  819.31   751.6  824.06   822.3  843.87   862.8  840.13
  1004.3  841.18  1014.4  844.88  1024.5  853.18  1034.6  865.25    1075  895.01
#Mann= 3 , 0 , 0
    10.1     .06       0   501.7     .05       0  544.36     .08       0
#XS Ineff= 2 , 0
       0     452             589       0
Permanent Ineff=
       F       F
Bank Sta=501.7,544.36
XS Rating Curve= 0 ,0
Exp/Cntr=0.3,0.1

Chan Stop Cuts=-1
Use User Specified Reach Order=0